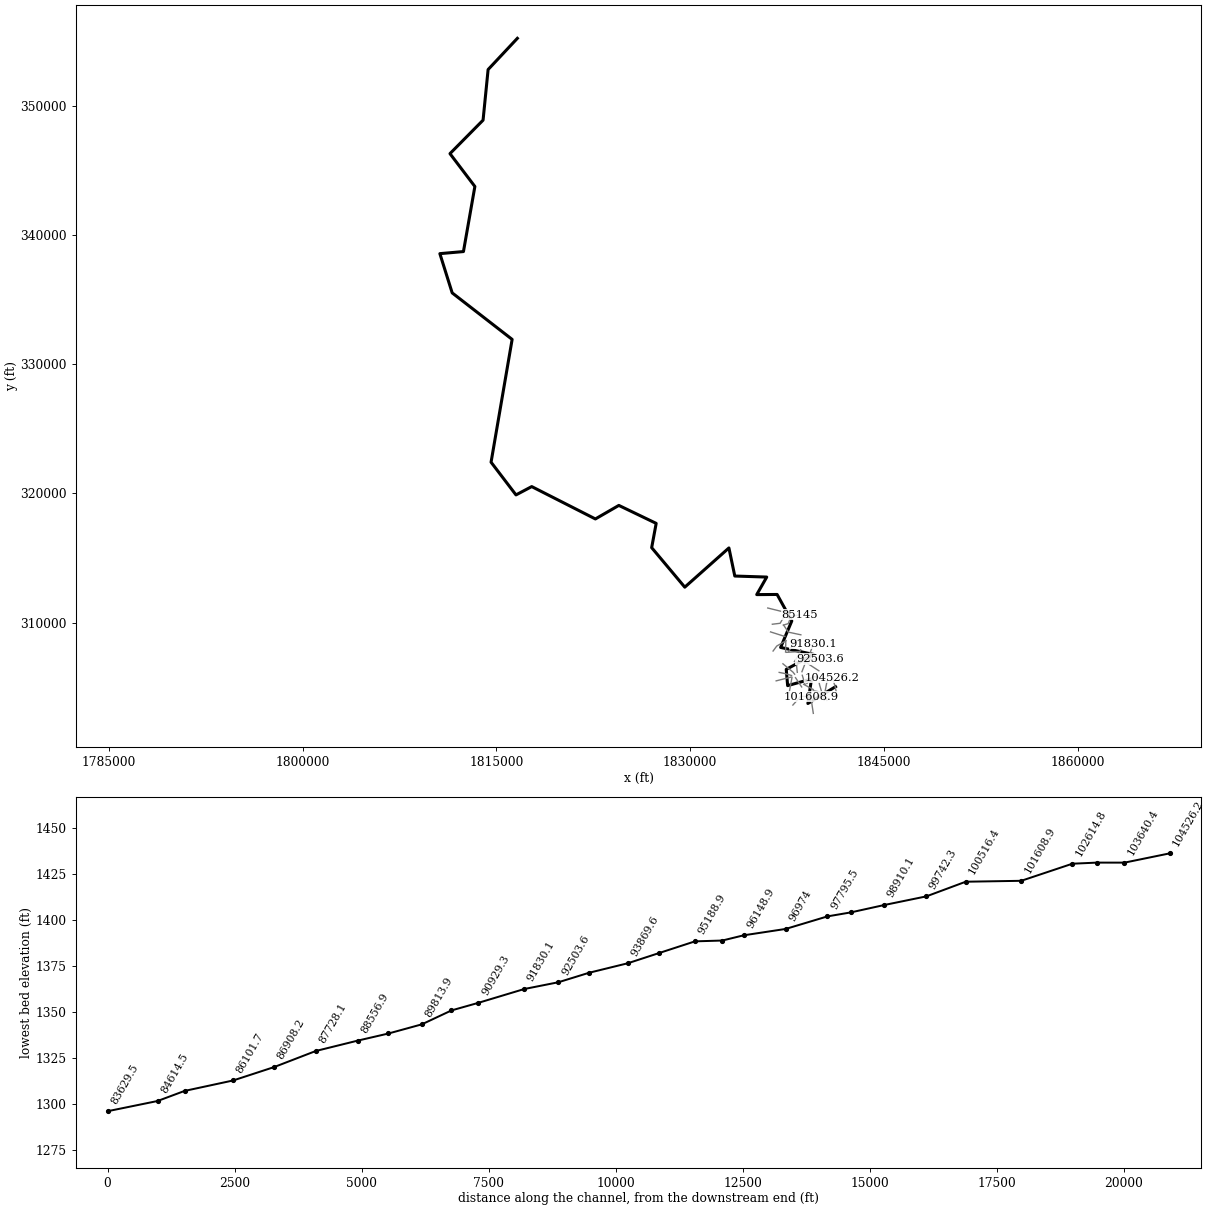
--- MrshFrk1.prj (project) ---

Proj Title=MrshFrk1
Current Plan=p01
Default Exp/Contr=0,0
English Units
Geom File=g01
Flow File=f01
Plan File=p01
BEGIN DESCRIPTION:
END DESCRIPTION:
DSS Export Rating Curves= 0
DSS Export Rating Curve Sorted= 0
DSS Export Volume Flow Curves= 0
DXF OffsetX= 0
DXF OffsetY= 0
DXF ScaleX= 0
DXF ScaleY= 0

--- MrshFrk1.p01 (plan) ---

Plan Title=Floodplain
Program Version=4.00
Geom File=g01
Flow File=f01
K Sum by GR=0
Std Step Tol=0.01
Critical Tol=0.01
Num of Std Step Trials=20
Max Error Tol=0.3
Flow Tol Ratio=0.001
Split Flow NTrial=30
Split Flow Tol=0.02
Split Flow Ratio=0.02
Log Output Level=0
Friction Slope Method=1
Unsteady Friction Slope Method=2
Unsteady Bridges Friction Slope Method=1
Global Log Level=0
CheckData=False
Run HTab=0
Run UNet=0
Run PostProcess=0
UNET Theta=0
UNET Theta Warmup=0
UNET ZTol=0
UNET ZSATol=0
UNET MxIter=0
UNET MaxInSteps=0
UNET DtIC=0
UNET DtMin=0
UNET MaxCRTS=0
UNET WFStab=0
UNET SFStab=0
UNET WFX=0
UNET SFX=0
UNET DSS MLevel=0
UNET DZMax Abort=0
UNET Convert EG Bridges=0
UNET Use Existing IB Tables=0
UNET Froude Limit=0
UNET Froude Power=0
Write IC File=0
Echo Input=False
Echo Output=False
Write Detailed=0

--- MrshFrk1.f01 (steady flow) ---

Flow Title=NFF Regression Equation
Program Version=4.00
Number of Profiles=1
Profile Names=P100yr
River Rch & RM=MrshFrk1,Main      ,104526.2
10831.61
River Rch & RM=MrshFrk1,Main      ,90929.3
11192.40
River Rch & RM=MrshFrk1,Main      ,76754.3
12434.13
River Rch & RM=MrshFrk1,Main      ,66126.6
13673.62
River Rch & RM=MrshFrk1,Main      ,58298.2
14332.61
River Rch & RM=MrshFrk1,Main      ,37279.4
15539.79
River Rch & RM=MrshFrk1,Main      ,2959.1
17261.05
River Rch & RM=MrshFrk1,Main      ,2126
21545.92
River Rch & RM=MrshFrk1,Main      ,73
21643.20
Boundary for River Rch & Prof#=MrshFrk1,Main      ,1
Up Type=0
Dn Type=3
Dn Slope=0.001434

--- MrshFrk1.g01 (geometry) ---

Geom Title=USGS 3m DEM
Program Version=4.10

River Reach=MrshFrk1        ,Main
Reach XY= 30
     1841244.124      305041.628      1839107.19      303740.904
     1839385.391      305640.137     1837540.339      305124.512
     1837431.901      306381.726     1839557.266      307538.574
     1836998.672      308080.241     1837860.651      310128.418
     1836725.234      312181.804     1835147.925      312170.137
     1835921.849      313528.157     1833449.622      313607.934
     1832994.989      315782.715     1829578.539      312746.034
     1827015.599      315804.199     1827364.557      317684.408
     1824473.932      319075.033     1822658.828      318026.855
     1817731.578      320531.909     1816512.995      319887.533
     1814584.416      322419.242     1816214.818      331925.293
     1811574.751      335525.132     1810621.068      338563.314
     1812446.589       338723.47     1813330.704      343760.936
      1811403.62      346304.199     1813964.709      348894.815
     1814355.443      352813.314     1816618.989      355228.625

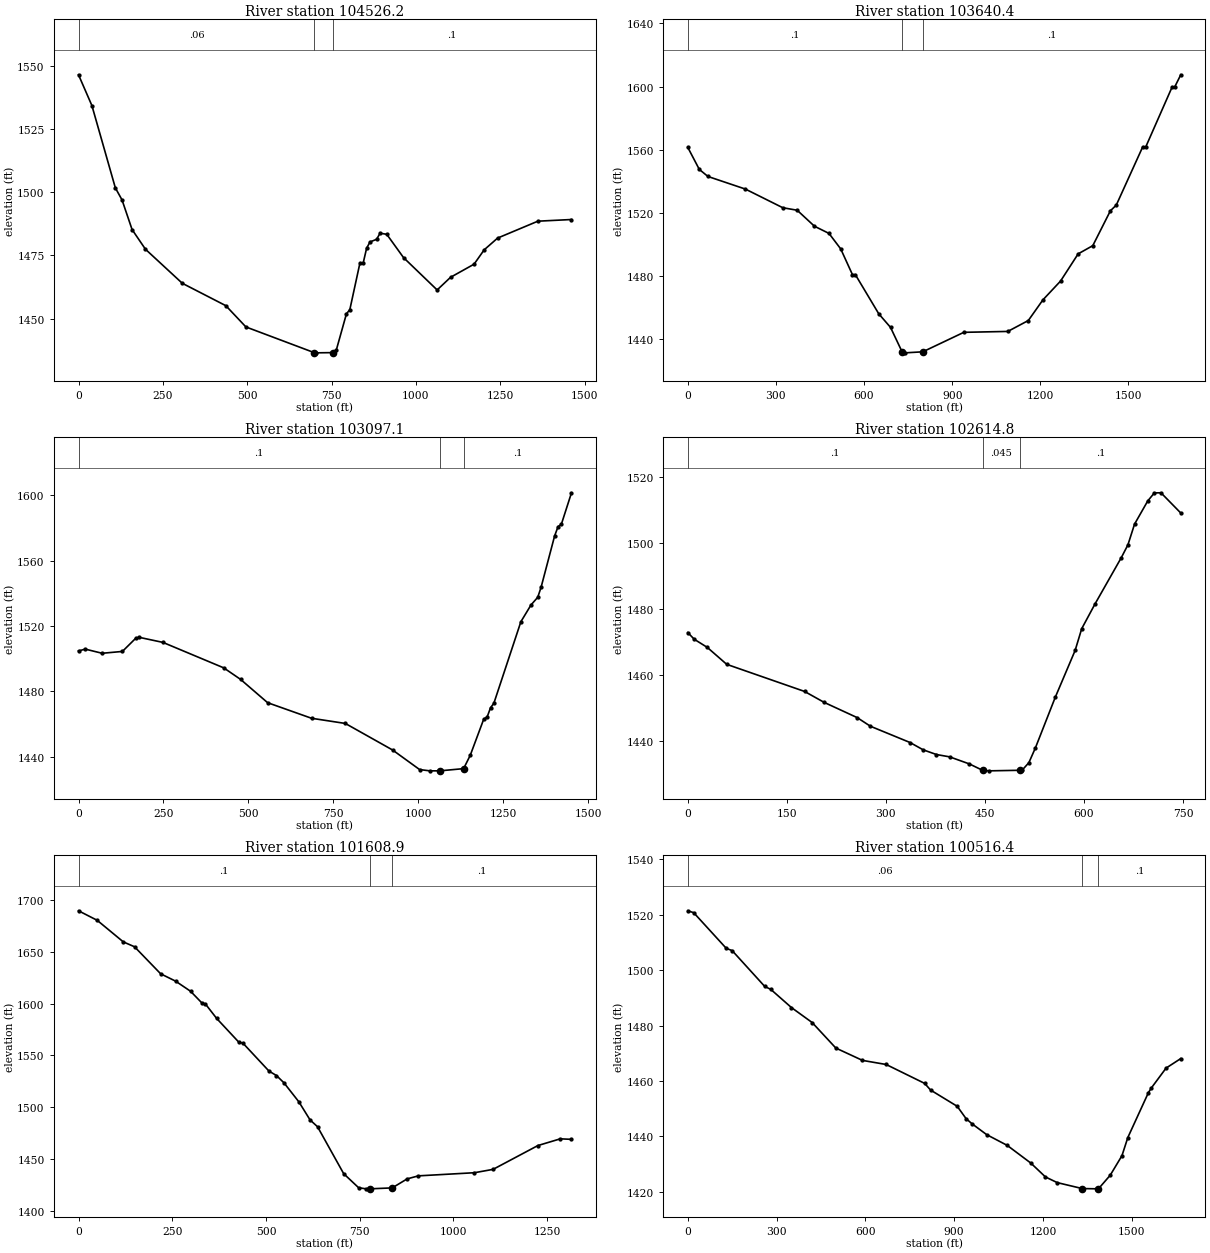
Type RM Length L Ch R = 1 ,104526.2,906.6,885.8,861.7
XS GIS Cut Line= 3
     1841374.966      304319.654     1841218.362      305037.148
     1841009.168      305733.083
#Sta/Elev= 30
       0 1546.51    39.7 1534.32   109.2 1501.73     129 1496.96   158.8 1485.22
   198.5 1477.42   307.6 1463.95   436.7 1455.08   496.2 1446.66   699.4 1436.45
   704.6 1436.41   754.3  1436.5   764.2 1437.58   794.1 1451.86   804.1 1453.49
   833.9 1471.86   843.9 1472.06   853.8 1477.78   863.8 1480.31   883.7 1481.38
   893.7 1483.79   913.6 1483.34   963.3 1474.12  1062.9 1461.31  1102.7 1466.32
  1172.4 1471.52  1202.3 1477.19  1242.1 1481.85  1361.5 1488.54  1461.1  1489.2
#Mann= 3 , 0 , 0
       0     .06       0   699.4    .045       0   754.3      .1       0
Bank Sta=699.4,754.3
XS Rating Curve= 0 ,0
Exp/Cntr=0.3,0.1

Type RM Length L Ch R = 1 ,103640.4,518.3,543.3,567.6
XS GIS Cut Line= 3
     1840585.032      303978.732     1840385.223      304393.761
     1840611.809      305589.853
#Sta/Elev= 30
       0 1561.51    39.2 1547.57    68.6 1543.09     196 1535.11   323.4 1523.29
   372.4  1521.7   431.2 1511.57   480.6 1507.03   520.5 1497.24   560.4 1480.95
   570.4 1480.91   650.2 1456.07   690.1 1447.51   729.9 1431.86     740 1431.39
   799.9 1432.04   939.6 1444.38  1089.3 1444.95  1159.1 1451.86    1209 1464.98
  1268.9 1476.86  1328.7 1494.07  1378.6 1499.28  1438.5 1521.36  1458.5 1524.95
  1548.3 1561.77  1558.2 1561.54    1648 1599.51    1658 1600.01    1678 1607.49
#Mann= 3 , 0 , 0
       0      .1       0   729.9    .045       0   799.9      .1       0
Bank Sta=729.9,799.9
XS Rating Curve= 0 ,0
Exp/Cntr=0.3,0.1

Type RM Length L Ch R = 1 ,103097.1,427.3,482.3,537.4
XS GIS Cut Line= 3
     1840372.835      303988.577     1840015.941      305168.677
     1839975.518      305383.425
#Sta/Elev= 30
       0 1504.75    19.9 1505.85    69.6 1503.31   129.2 1504.43     169  1512.6
     179 1513.05   248.6 1509.96   427.5  1494.4   477.2 1487.33   556.8 1473.08
     686 1463.56   785.5 1460.39   924.7 1444.15  1004.2 1432.18    1034  1431.4
  1063.8  1431.4  1133.8 1432.75  1153.4 1440.94  1193.1 1463.06  1203.1 1464.35
    1213 1469.96  1222.9 1472.76  1302.4 1522.61  1332.2 1532.86  1352.1 1537.58
    1362 1543.77  1401.7 1575.06  1411.7 1580.71  1421.6 1582.23  1451.4 1601.48
#Mann= 3 , 0 , 0
       0      .1       0  1063.8    .045       0  1133.8      .1       0
Bank Sta=1063.8,1133.8
XS Rating Curve= 0 ,0
Exp/Cntr=0.3,0.1

Type RM Length L Ch R = 1 ,102614.8,1069.5,1005.9,942.2
XS GIS Cut Line= 3
     1840174.862      304469.485     1840065.276      304632.699
     1839523.285       304726.55
#Sta/Elev= 30
       0 1472.85     9.8 1470.81    29.5 1468.34      59 1463.18   176.9 1454.94
   206.6 1451.61   256.6 1446.98   276.6 1444.36   336.6 1439.41   356.6 1437.18
   376.6 1435.76   396.6 1435.05   426.6 1432.89   446.6 1430.95   456.6  1430.8
   503.3 1430.97   506.6 1431.06   516.6 1433.29   526.6 1437.85   556.6  1453.2
   586.6  1467.4   596.6 1474.03   616.6  1481.5   656.6 1495.65   666.6 1499.53
   676.6 1505.82   696.6 1512.87   706.6 1515.31   716.6 1515.35   746.6  1509.2
#Mann= 3 , 0 , 0
       0      .1       0   446.6    .045       0   503.3      .1       0
Bank Sta=446.6,503.3
XS Rating Curve= 0 ,0
Exp/Cntr=0.3,0.1

Type RM Length L Ch R = 1 ,101608.9,1182.3,1092.5,1002.7
XS GIS Cut Line= 2
     1839527.305      302977.289     1839329.825      304277.077
#Sta/Elev= 30
       0 1689.43    49.8 1680.26   119.5 1659.45   149.4 1654.75   219.1  1628.7
     259 1621.61   298.8 1611.89   328.7 1600.74   338.6 1599.56   368.5 1585.68
   428.3 1562.52   438.2    1562     508 1534.95   527.9 1530.68   547.8  1523.7
   587.6 1505.38   617.5 1487.92   637.4 1481.36   707.2  1436.1     747 1422.58
   766.9  1421.5   776.7  1421.5   836.6 1422.41   876.5  1431.1   906.4 1434.01
  1055.8 1437.03  1105.6 1440.27  1225.1 1463.21  1284.8 1469.68  1314.7  1469.2
#Mann= 3 , 0 , 0
       0      .1       0   776.7    .045       0   836.6      .1       0
Bank Sta=776.7,836.6
XS Rating Curve= 0 ,0
Exp/Cntr=0.3,0.1

Type RM Length L Ch R = 1 ,100516.4,798,774.2,750.3
XS GIS Cut Line= 3
     1837946.458      303621.325     1838553.049      304300.102
     1839307.368      304263.602
#Sta/Elev= 30
       0 1521.47      20 1520.78     130  1507.9     150 1507.07   260.1 1494.12
   280.1  1493.1   350.1 1486.51   420.2 1481.09   500.2 1471.87   590.2 1467.41
   670.2 1465.93   800.3  1459.1   820.3 1456.69   910.3 1450.82   940.1 1446.38
     960 1444.53  1009.7 1440.59  1079.2  1436.7  1158.8 1430.32  1208.4 1425.29
  1248.2 1423.25  1332.5  1421.1  1387.3    1421    1427 1425.89  1466.8 1432.97
  1486.7 1439.55  1556.2 1455.76  1566.2 1457.46  1615.8 1464.62  1665.5 1468.07
#Mann= 3 , 0 , 0
       0     .06       0  1332.5    .045       0  1387.3      .1       0
Bank Sta=1332.5,1387.3
XS Rating Curve= 0 ,0
Exp/Cntr=0.3,0.1

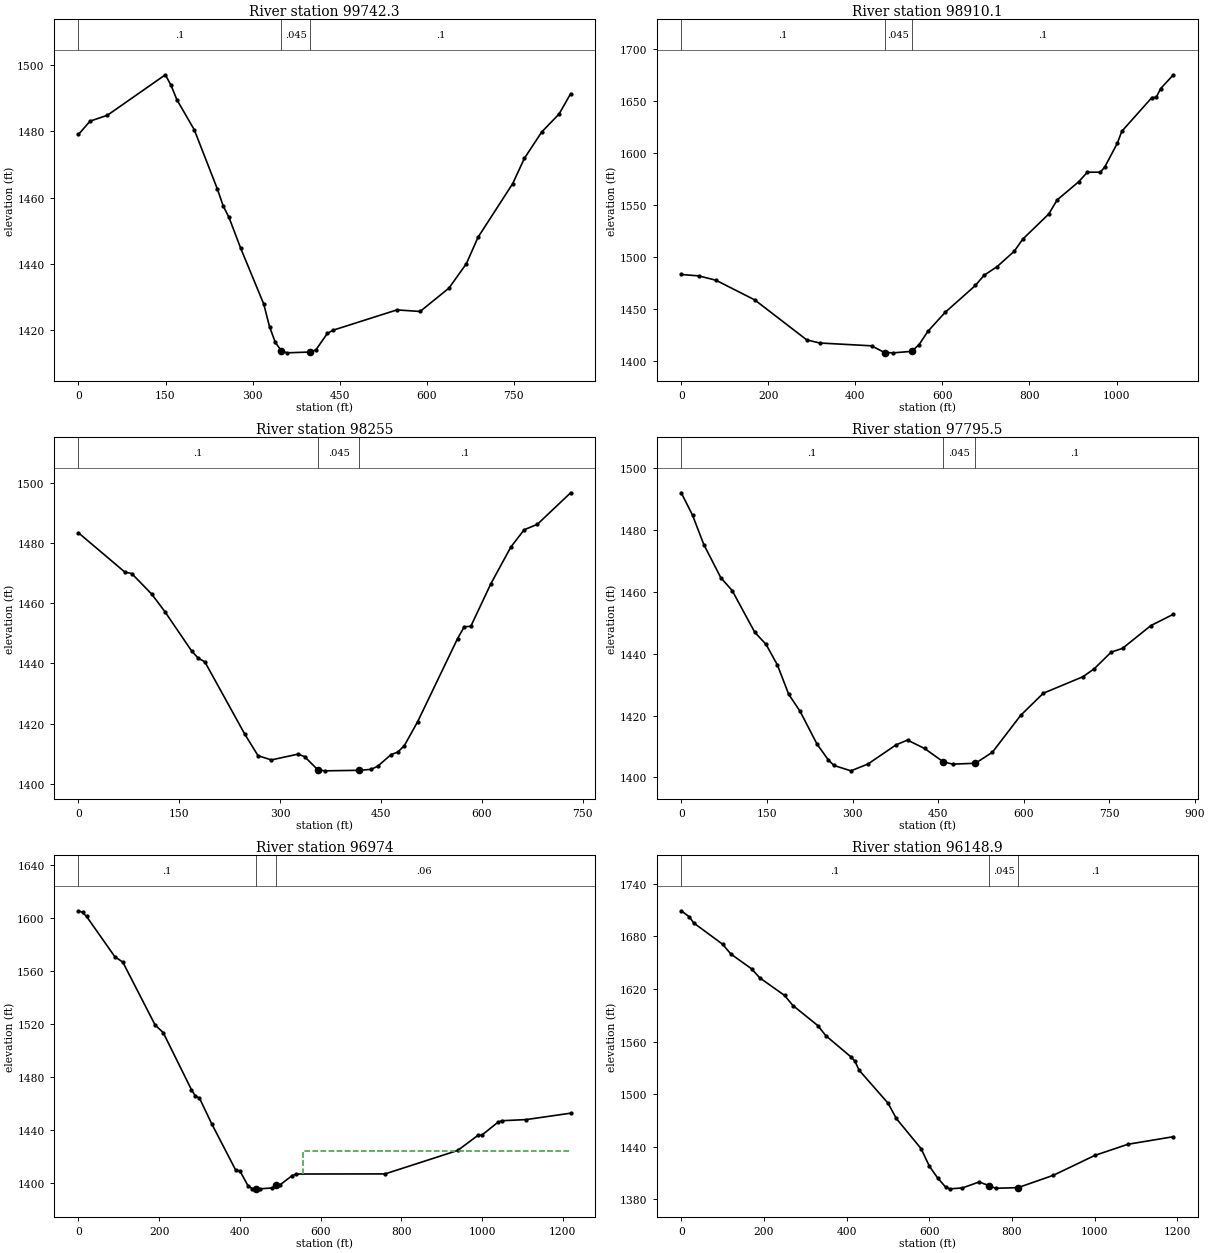
Type RM Length L Ch R = 1 ,99742.3 ,764.4,832.1,899.8
XS GIS Cut Line= 2
     1838781.868      305224.773     1839527.449      304820.543
#Sta/Elev= 30
       0 1479.08      20 1483.12    49.9  1484.9   149.7 1497.14   159.6 1493.92
   169.6  1489.6   199.6 1480.49   239.5 1462.52   249.4 1457.47   259.4 1453.98
   279.4 1444.73   319.3 1427.78   329.3 1420.89   339.2  1416.2   349.2 1413.72
   359.2 1413.03   399.1 1413.28   409.1 1413.92     429 1418.94     439 1419.89
   548.8 1426.02   588.7 1425.54   638.6 1432.64   668.5 1440.03   688.5 1447.98
   748.3 1464.23   768.3 1471.83   798.2 1479.82   828.2 1485.29   848.1 1491.41
#Mann= 3 , 0 , 0
       0      .1       0   349.2    .045       0   399.1      .1       0
Bank Sta=349.2,399.1
XS Rating Curve= 0 ,0
Exp/Cntr=0.3,0.1

Type RM Length L Ch R = 1 ,98910.1 ,604.1,655.1,706.1
XS GIS Cut Line= 3
     1839028.898      305287.654     1839509.483      305817.645
     1839922.697      305777.222
#Sta/Elev= 30
       0 1483.41    39.8  1482.1    79.5 1477.95   168.9 1459.05   288.2 1420.74
     318 1417.73   437.2 1415.03     467  1408.6   486.9  1408.3   529.5 1409.73
   546.5 1416.25   566.4 1428.82   606.1 1447.03   675.7 1472.86   695.6 1482.62
   725.3 1490.84   764.9 1505.64   784.6 1517.32     844 1541.27   863.7 1554.93
   913.2 1572.36   932.9 1581.46   962.6 1581.47   972.5 1586.09  1002.1 1609.49
    1012 1620.64  1081.2 1653.05  1091.1 1653.18    1101 1661.49  1130.6 1674.86
#Mann= 3 , 0 , 0
       0      .1       0     467    .045       0   529.5      .1       0
Bank Sta=467,529.5
XS Rating Curve= 0 ,0
Exp/Cntr=0.3,0.1

Type RM Length L Ch R = 1 ,98255   ,444.8,459.5,474.2
XS GIS Cut Line= 2
     1838885.171      305224.773     1838674.073       305925.44
#Sta/Elev= 30
       0 1483.41    69.2 1470.32    79.1 1469.89   108.8 1463.07   128.6 1457.18
   168.1  1444.2     178 1441.76   187.9 1440.54   247.2 1416.53     267 1409.33
   286.8 1407.93   326.3 1409.84   336.2 1409.04     356 1404.62   365.9  1404.3
   417.6 1404.48   435.1 1404.79     445 1405.84   464.8  1409.7   474.7 1410.51
   484.6  1412.7   504.3 1420.63   563.7 1448.26   573.6 1452.18   583.4 1452.35
   613.1 1466.45   642.8 1478.65   662.6 1484.41   682.3 1486.24   731.8 1496.72
#Mann= 3 , 0 , 0
       0      .1       0     356    .045       0   417.6      .1       0
Bank Sta=356,417.6
XS Rating Curve= 0 ,0
Exp/Cntr=0.3,0.1

Type RM Length L Ch R = 1 ,97795.5 ,860.6,821.5,782.5
XS GIS Cut Line= 2
     1838624.667      305022.658     1838148.573      305741.291
#Sta/Elev= 30
       0 1491.97    19.8 1484.73    39.6 1475.22    69.4 1464.51    89.2 1460.39
   128.8  1446.9   148.6 1442.98   168.4 1436.34   188.3 1426.84   208.1 1421.38
   237.8 1410.78   257.6 1405.66   267.5 1403.87   297.2 1402.13     327 1404.33
   376.5 1410.55   396.3 1412.07   426.1 1409.36   459.1 1405.02   475.6  1404.3
   515.2 1404.57     545 1408.13   594.5 1420.06   634.1  1427.2   703.5 1432.53
   723.3  1435.1     753 1440.48   772.9  1441.7   822.4 1449.04     862 1452.73
#Mann= 3 , 0 , 0
       0      .1       0   459.1    .045       0   515.2      .1       0
Bank Sta=459.1,515.2
XS Rating Curve= 0 ,0
Exp/Cntr=0.3,0.1

Type RM Length L Ch R = 1 ,96974   ,883.1,825,766.9
XS GIS Cut Line= 2
     1837659.004      304569.022     1837879.086      305768.239
#Sta/Elev= 30
       0 1605.09      10  1603.9      20 1600.82    89.9 1570.53   109.9 1566.32
   189.9  1518.9   209.9 1513.17   279.8 1470.15   289.8 1465.23   299.8 1463.72
   329.8 1444.54   389.8 1409.24   399.8  1408.9   419.7 1397.79   429.7 1395.49
   439.7 1395.35   449.7  1395.3   479.7    1396   489.7 1398.04   499.7 1398.41
   529.7 1405.36   539.7 1406.48   759.5 1406.56   939.4 1424.26   989.4 1435.62
   999.4 1435.85  1039.4 1445.62  1049.4 1446.69  1109.3 1447.56  1219.2 1452.38
#Mann= 3 , 0 , 0
       0      .1       0   439.7    .045       0   489.7     .06       0
#XS Ineff= 2 , 0
                          555.28         1424.08
Permanent Ineff=
       F       F
Bank Sta=439.7,489.7
XS Rating Curve= 0 ,0
Exp/Cntr=0.3,0.1

Type RM Length L Ch R = 1 ,96148.9 ,447.2,422.6,392.9
XS GIS Cut Line= 2
     1836652.919      305494.261     1837807.223      305786.205
#Sta/Elev= 30
       0 1709.27      20 1702.22      30 1695.43     100 1671.14   120.1 1659.89
   170.1 1643.03   190.1 1632.66   250.1 1612.58   270.2 1601.11   330.2 1578.29
   350.2 1566.49   410.2 1542.62   420.2 1537.62   430.2 1527.34   500.3 1489.62
   520.3 1472.14   580.3 1437.68   600.3  1417.7   620.3 1404.21   640.4 1393.47
   650.4 1391.84   680.4 1392.88   720.4 1399.64   744.7 1395.54   760.4 1392.49
   814.7 1393.21   900.5 1407.36  1000.6 1430.01  1080.6 1442.72  1190.6 1451.36
#Mann= 3 , 0 , 0
       0      .1       0   744.7    .045       0   814.7      .1       0
Bank Sta=744.7,814.7
XS Rating Curve= 0 ,0
Exp/Cntr=0.3,0.1

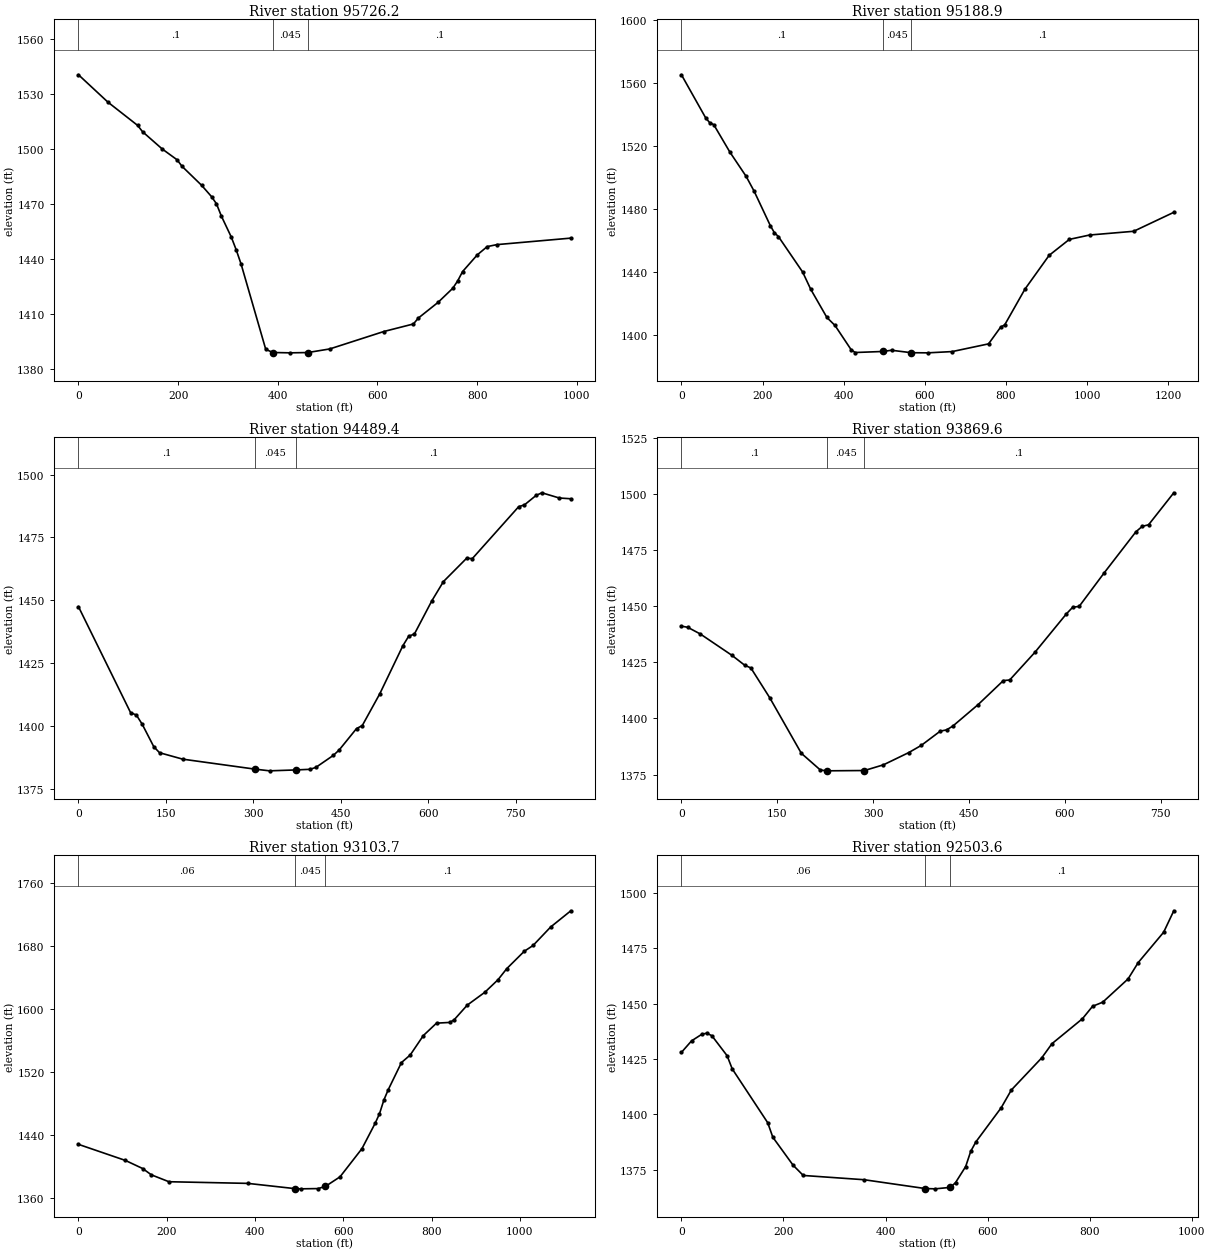
Type RM Length L Ch R = 1 ,95726.2 ,543.7,537.3,535.4
XS GIS Cut Line= 3
     1836885.975      306148.548      1837303.06      306065.643
     1837843.154      305907.475
#Sta/Elev= 30
       0 1540.41    59.3 1525.46   118.7 1512.84   128.6  1509.4   168.1 1499.99
   197.8 1494.13   207.7 1490.59   247.2 1480.19     267 1474.05   276.9 1470.16
   286.8 1463.43   306.6 1452.08   316.5  1445.1   326.4 1437.26   375.8 1390.89
   390.2 1389.17   425.2 1388.99   460.2 1389.15   504.2 1391.11   612.8 1400.61
   672.1 1404.71     682 1407.93   721.4 1416.43   751.1 1424.15   760.9 1428.15
   770.8 1433.25   800.4 1442.37   820.2 1446.85   839.9 1447.93     988 1451.46
#Mann= 3 , 0 , 0
       0      .1       0   390.2    .045       0   460.2      .1       0
Bank Sta=390.2,460.2
XS Rating Curve= 0 ,0
Exp/Cntr=0.3,0.1

Type RM Length L Ch R = 1 ,95188.9 ,760,699.5,639.1
XS GIS Cut Line= 3
     1837176.626      306814.907     1837950.949       306172.47
     1838081.201      306010.778
#Sta/Elev= 30
       0 1565.25    59.8 1537.84    69.7 1534.79    79.7 1533.53   119.5 1516.08
   159.4 1500.73   179.3 1491.22   219.2 1469.34   229.1  1464.9   239.1 1462.43
   298.8 1439.89   318.8 1428.91   358.6 1411.01   378.5 1405.96   418.4 1390.51
   428.4 1388.75   496.7 1389.41     518 1390.18   566.7 1388.62   607.7 1388.54
   667.4 1389.34   757.1 1394.24     787  1404.9   796.9  1406.3   846.7 1428.97
   906.5  1450.5   956.3 1460.64  1006.1 1463.41  1114.9 1465.79  1213.8 1477.84
#Mann= 3 , 0 , 0
       0      .1       0   496.7    .045       0   566.7      .1       0
Bank Sta=496.7,566.7
XS Rating Curve= 0 ,0
Exp/Cntr=0.3,0.1

Type RM Length L Ch R = 1 ,94489.4 ,642.6,619.8,597.5
XS GIS Cut Line= 2
     1838197.979      306994.406     1838287.808      306154.504
#Sta/Elev= 30
       0 1447.48    89.4 1405.38    99.4  1404.4   109.3 1400.78   129.2 1391.83
   139.1 1389.44   178.9 1386.88     303 1382.91   327.9 1382.24     373  1382.6
   397.5 1382.85   407.4 1383.63   437.2 1388.38   447.2 1390.51     477 1399.03
   486.9 1400.24   516.8  1412.8   556.5 1431.94   566.4  1435.7   576.4 1436.65
   606.2 1449.79   626.1 1457.45   665.8  1466.7   675.8 1466.62   755.2 1487.22
   765.2 1487.95   785.1  1491.7     795 1492.75   824.8 1490.68   844.7 1490.37
#Mann= 3 , 0 , 0
       0      .1       0     303    .045       0     373      .1       0
Bank Sta=303,373
XS Rating Curve= 0 ,0
Exp/Cntr=0.3,0.1

Type RM Length L Ch R = 1 ,93869.6 ,698,765.9,833.3
XS GIS Cut Line= 2
     1838925.594      306922.543     1838647.124       306203.91
#Sta/Elev= 30
       0 1441.15     9.9 1440.62    29.6 1437.64      79 1428.14    98.8 1423.77
   108.7  1422.5   138.3 1409.18   187.7 1384.45   217.4 1377.02   227.3 1376.64
   228.4 1376.65   286.5 1376.78   316.2 1379.32   355.7 1384.76   375.5    1388
   405.1 1394.33     415  1394.9   424.9 1396.61   464.4 1406.17   503.9 1416.87
   513.8 1417.14   553.3 1429.48   602.7 1446.66   612.6 1449.61   622.5 1449.92
     662    1465   711.4 1483.21   721.3 1485.63   731.2 1486.33   770.7  1500.6
#Mann= 3 , 0 , 0
       0      .1       0   228.4    .045       0   286.5      .1       0
Bank Sta=228.4,286.5
XS Rating Curve= 0 ,0
Exp/Cntr=0.3,0.1

Type RM Length L Ch R = 1 ,93103.7 ,569.9,600.1,630.3
XS GIS Cut Line= 4
     1839023.459      306886.657     1839134.968      306809.994
      1839925.99      306294.262     1839957.352      306276.839
#Sta/Elev= 30
       0 1427.97   106.3 1407.55   145.3 1397.28   165.1 1389.25   204.9 1380.48
   383.8 1378.37   489.6 1371.76   503.1 1371.44   542.9 1371.77   559.6 1374.58
   592.6 1386.72   642.3 1422.56   672.1 1454.69     682 1466.86     692 1484.43
   701.9 1497.53   731.7 1531.88   751.6 1541.54   781.4 1566.28   811.2 1582.02
   841.1 1582.92     851  1586.2   880.8 1604.91   920.6 1621.23   950.4 1637.14
   970.3 1651.27    1010 1673.37  1029.9 1680.71  1069.7 1704.17  1115.5 1724.83
#Mann= 3 , 0 , 0
       0     .06       0   489.6    .045       0   559.6      .1       0
Bank Sta=489.6,559.6
XS Rating Curve= 0 ,0
Exp/Cntr=0.3,0.1

Type RM Length L Ch R = 1 ,92503.6 ,612.4,673.6,734.7
XS GIS Cut Line= 2
     1839064.829      307165.081       1840029.5      307188.439
#Sta/Elev= 30
       0    1428    19.9 1433.22    39.8 1436.17    49.7 1436.69    59.7 1435.52
    89.5  1426.5    99.5 1420.56   169.1  1396.2   179.1 1389.64   218.9 1376.96
   238.8 1372.35   358.1 1370.42   477.5 1366.44   497.4  1366.3   527.2 1366.97
   537.2 1369.11   557.1 1376.39     567 1383.26     577  1387.5   626.7 1402.97
   646.6 1410.99   706.3 1425.56   726.2 1431.93   785.9 1443.21   805.8 1448.84
   825.7  1450.7   875.4 1461.22   895.3 1468.62   945.1 1482.33     965 1492.03
#Mann= 3 , 0 , 0
       0     .06       0   477.5    .045       0   527.2      .1       0
Bank Sta=477.5,527.2
XS Rating Curve= 0 ,0
Exp/Cntr=0.3,0.1

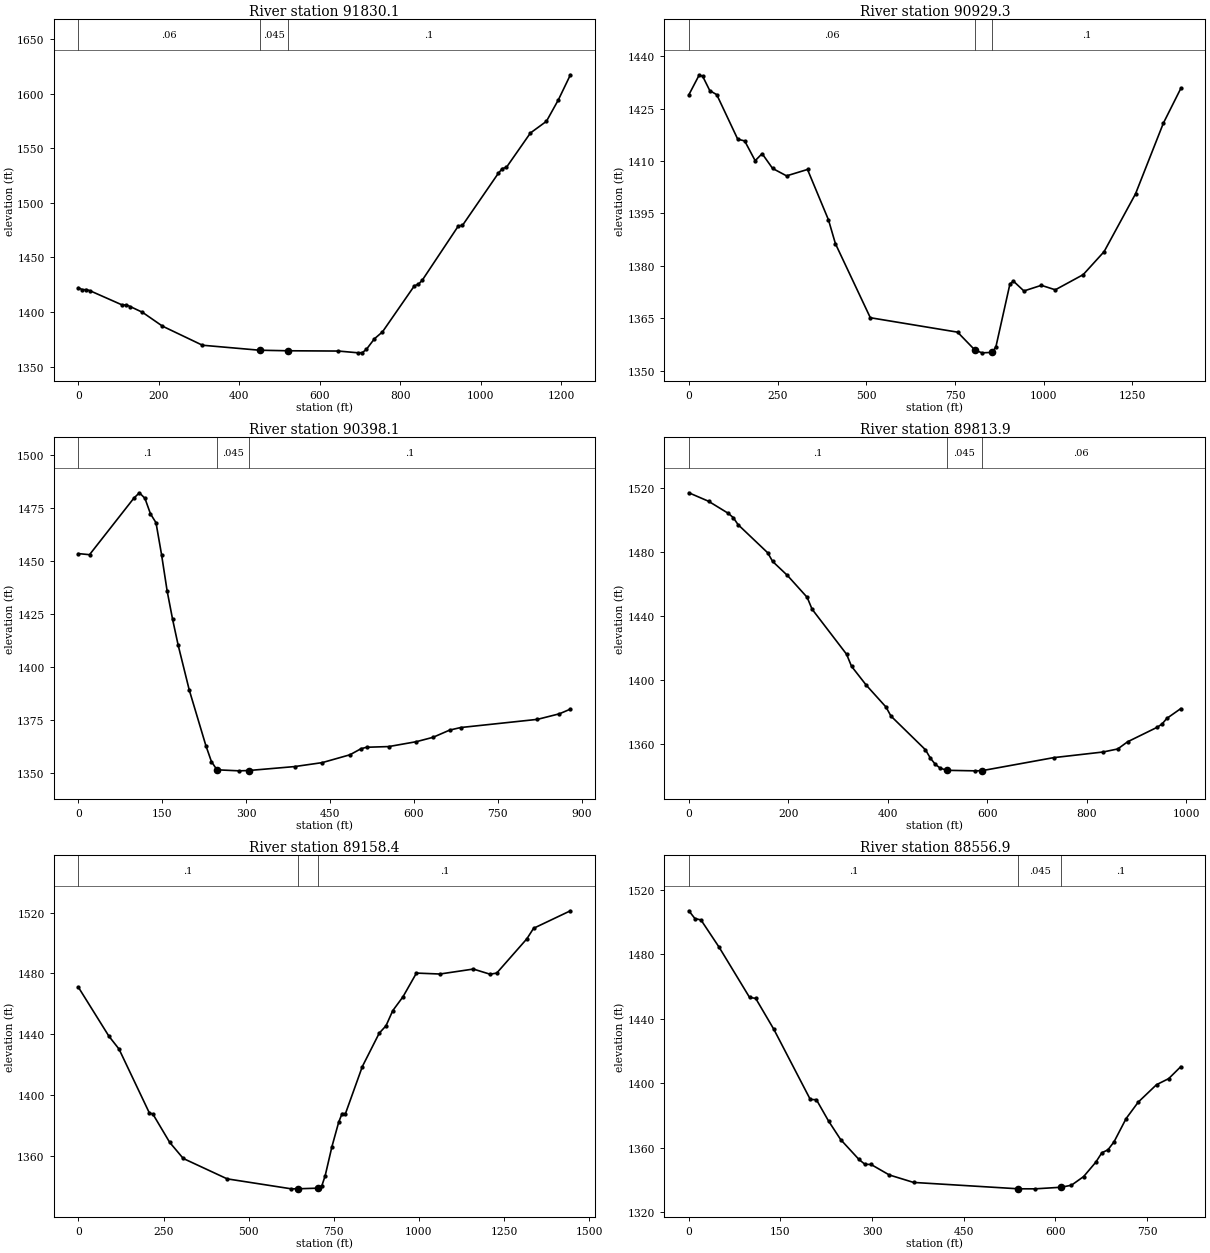
Type RM Length L Ch R = 1 ,91830.1 ,837.1,900.7,955.6
XS GIS Cut Line= 2
     1839105.252       307223.47     1839545.415      308364.299
#Sta/Elev= 30
       0 1422.27     9.9 1420.38    19.9 1420.56    29.8 1419.29   109.4 1406.33
   119.3 1406.55   129.2 1404.89   159.1 1399.73   208.8 1387.05   308.2 1369.57
   450.4 1364.99   520.4  1364.5   646.2 1364.24   695.9  1362.6   705.8 1362.86
   715.8 1365.84   735.7 1375.49   755.6 1381.77   835.1 1424.06     845  1425.4
     855 1429.36   944.4  1478.9   954.4 1479.26  1043.8 1527.14  1053.8 1531.41
  1063.7 1532.43  1123.4 1563.95  1163.2 1574.65    1193 1594.43  1222.8 1617.25
#Mann= 3 , 0 , 0
       0     .06       0   450.4    .045       0   520.4      .1       0
Bank Sta=450.4,520.4
XS Rating Curve= 0 ,0
Exp/Cntr=0.3,0.1

Type RM Length L Ch R = 1 ,90929.3 ,607.3,531.2,462.8
XS GIS Cut Line= 5
     1838821.729      306866.961     1838984.801      307158.904
     1838599.402       307395.83      1838437.71      307581.102
     1838545.505      307917.961
#Sta/Elev= 30
       0 1428.95    29.5 1434.68    39.3 1434.19      59 1430.15    78.7 1428.98
   137.7 1416.26   157.4 1415.74   186.9 1410.09   206.5 1412.11     236 1407.88
   275.4 1405.75   334.4 1407.58   393.4 1393.18   413.1 1386.33   511.4 1365.15
   757.3 1361.02   806.5 1355.86   826.2  1355.1   855.6 1355.23   865.5 1356.91
   904.8 1374.79   914.7 1375.62   944.2 1372.81   993.4 1374.42  1032.7 1373.14
  1111.3 1377.48  1170.2 1384.06  1258.7 1400.59  1337.3 1420.85  1386.4 1430.78
#Mann= 3 , 0 , 0
       0     .06       0   806.5    .045       0   855.6      .1       0
Bank Sta=806.5,855.6
XS Rating Curve= 0 ,0
Exp/Cntr=0.3,0.1

Type RM Length L Ch R = 1 ,90398.1 ,630.7,584.1,537.5
XS GIS Cut Line= 3
     1838063.797       306988.23     1838424.236      307533.942
     1838434.342      307759.637
#Sta/Elev= 30
       0 1453.55    19.8 1453.04    99.1 1479.74     109 1482.28   118.9 1479.66
   128.8 1472.34   138.7 1468.14   148.6 1453.12   158.6 1435.93   168.4 1422.46
   178.4 1410.23   198.2  1389.1   227.9 1362.86   237.8 1355.34   247.7 1351.44
   287.4 1350.95   304.4  1351.1   386.5 1352.96     436 1354.83   485.6 1358.54
   505.4  1361.4   515.3 1362.09   554.9 1362.41   604.5 1364.73   634.2 1366.79
   663.8 1370.18   683.5  1371.4     821 1375.27   860.3  1377.9   879.9 1380.11
#Mann= 3 , 0 , 0
       0      .1       0   247.7    .045       0   304.4      .1       0
Bank Sta=247.7,304.4
XS Rating Curve= 0 ,0
Exp/Cntr=0.3,0.1

Type RM Length L Ch R = 1 ,89813.9 ,605.4,655.6,705.7
XS GIS Cut Line= 3
     1837454.082      307702.371     1838404.024      307759.637
     1838441.079      307766.375
#Sta/Elev= 30
       0 1516.97    39.6 1511.68    79.3 1504.14    89.2 1501.49    99.1 1497.05
   158.6  1479.5   168.5  1474.1   198.3 1465.34   237.9  1451.7   247.8  1444.3
   317.2 1416.15   327.1 1408.66   356.9 1396.81   396.5 1383.18   406.4 1377.57
   475.8 1356.51   485.8 1351.25   495.7 1347.39   505.6 1345.05   518.9  1343.7
     575 1343.37   588.9 1343.44   733.6 1351.61   832.7 1355.12   862.4 1357.02
   882.3 1361.51   941.8 1370.57   951.7 1372.65   961.1  1376.1   989.3 1382.24
#Mann= 3 , 0 , 0
       0      .1       0   518.9    .045       0   588.9     .06       0
Bank Sta=518.9,588.9
XS Rating Curve= 0 ,0
Exp/Cntr=0.3,0.1

Type RM Length L Ch R = 1 ,89158.4 ,575.6,601.2,626.7
XS GIS Cut Line= 3
     1837622.511        307752.9     1838114.326      308615.259
     1838566.173      308594.593
#Sta/Elev= 30
       0 1470.83    89.4 1438.75   119.1 1430.28   208.5 1388.17   218.4 1387.62
     268 1368.93   307.8 1358.36   436.8 1344.95   625.4 1338.39   645.3 1338.43
   704.8 1338.84   714.8 1340.31   724.7    1347   744.6 1366.16   764.4  1382.2
   774.3 1387.84   784.3 1387.84   833.9 1418.79   883.5 1440.72   903.4 1445.57
   923.2 1455.51     953 1464.54   992.8 1480.21  1061.6 1479.59  1159.9 1482.85
  1209.1 1479.46  1228.7 1480.23  1317.2 1502.76  1336.9 1509.65  1445.1 1521.16
#Mann= 3 , 0 , 0
       0      .1       0   645.3    .045       0   704.8      .1       0
Bank Sta=645.3,704.8
XS Rating Curve= 0 ,0
Exp/Cntr=0.3,0.1

Type RM Length L Ch R = 1 ,88556.9 ,880.7,828.7,776.8
XS GIS Cut Line= 2
     1837379.973      307725.952     1837396.816      308531.044
#Sta/Elev= 30
       0 1506.97     9.9 1502.17    19.9 1501.27    49.7 1484.29    99.4 1453.24
   109.4 1452.66   139.2 1433.42   198.8 1389.96   208.8 1389.82   228.7 1376.58
   248.5 1365.09   278.4 1352.79   288.3 1349.74   298.2 1349.66   328.1 1343.15
   367.8 1338.52   539.5 1334.56   566.7 1334.54   609.5 1335.53   626.3 1336.79
   646.2 1342.15   666.1 1351.04     676 1356.88     686 1358.74   695.9 1363.64
   715.8 1378.15   735.7 1388.36   765.5 1399.12   785.4 1402.87   805.3 1410.33
#Mann= 3 , 0 , 0
       0      .1       0   539.5    .045       0   609.5      .1       0
Bank Sta=539.5,609.5
XS Rating Curve= 0 ,0
Exp/Cntr=0.3,0.1

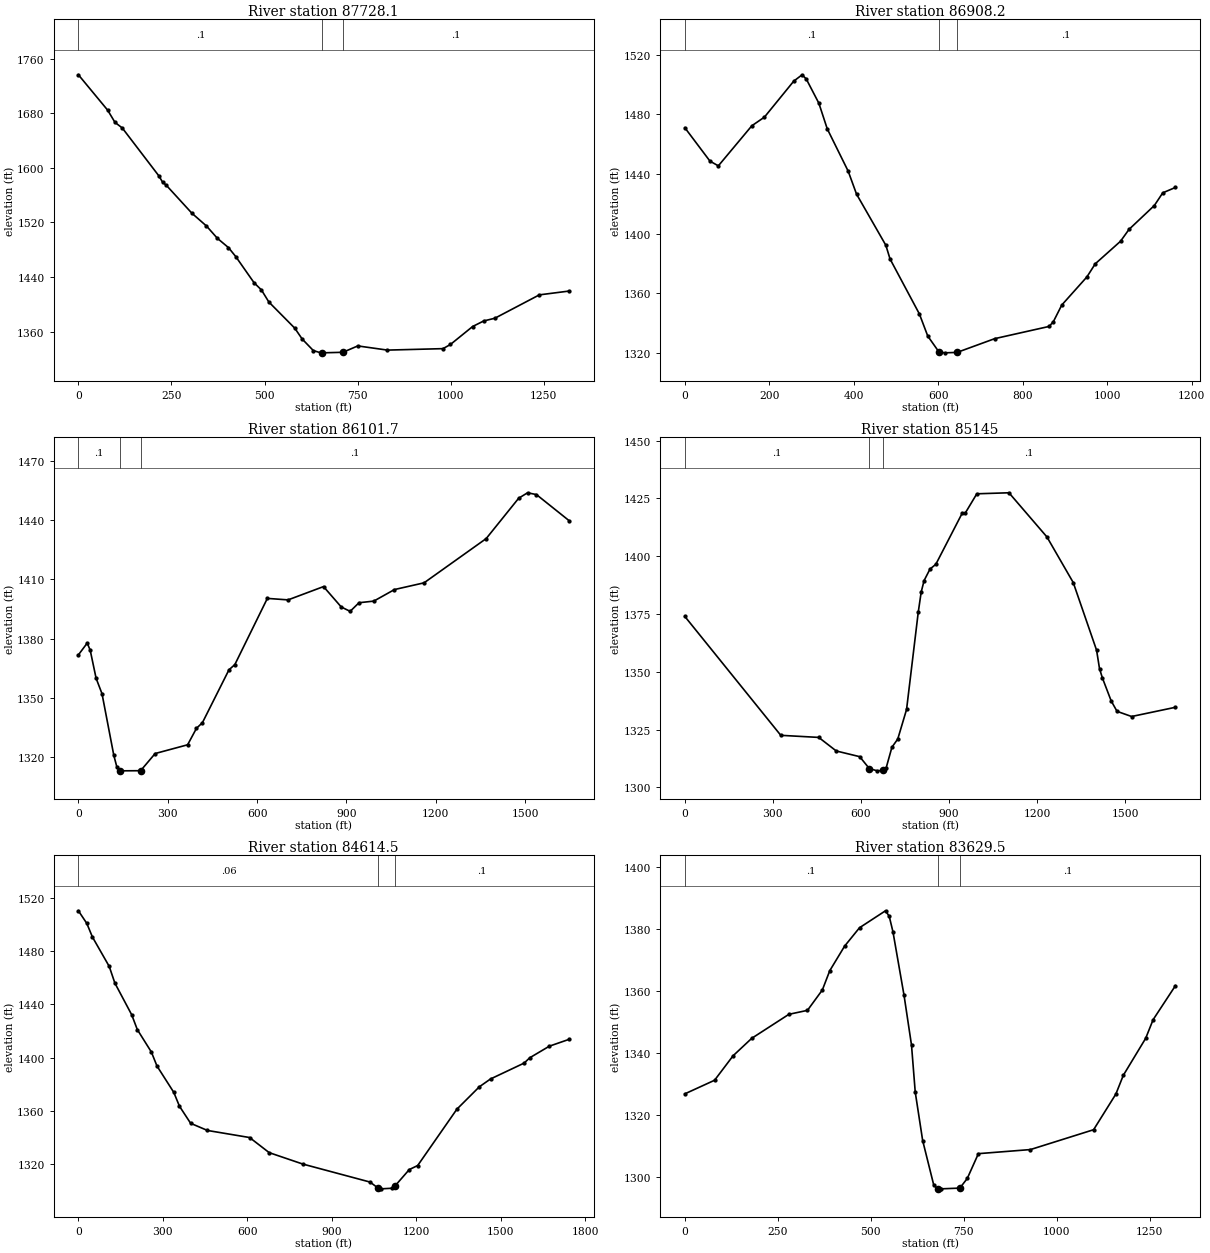
Type RM Length L Ch R = 1 ,87728.1 ,861.6,819.8,777.9
XS GIS Cut Line= 3
     1836413.188      307803.429     1836699.518      308190.817
     1837423.765      308608.522
#Sta/Elev= 30
       0 1736.59    78.6 1684.73    98.3 1666.79     118 1658.51   216.3 1588.26
   226.1  1579.2   235.9 1574.75   304.8 1533.65   344.1 1514.82   373.6 1496.67
   403.1  1483.2   422.7 1470.04   471.9 1431.66   491.7 1421.08   511.6 1403.43
   581.2 1365.06   601.2  1349.1     631 1332.24   650.9 1328.87   655.4 1328.88
   710.6 1329.68   750.5 1339.01   830.1 1332.89   979.4 1335.02   999.3  1341.1
    1059 1367.46  1088.9 1375.65  1118.7 1379.61  1238.2 1413.88  1317.8 1419.44
#Mann= 3 , 0 , 0
       0      .1       0   655.4    .045       0   710.6      .1       0
Bank Sta=655.4,710.6
XS Rating Curve= 0 ,0
Exp/Cntr=0.3,0.1

Type RM Length L Ch R = 1 ,86908.2 ,840,806.2,772.5
XS GIS Cut Line= 3
     1836216.375      309283.761     1837161.015      308982.436
     1837326.076      308942.012
#Sta/Elev= 30
       0 1471.06    59.5 1448.66    79.3  1445.5   158.6 1472.38   188.4 1478.17
   257.8 1502.29   277.6 1506.57   287.5 1503.73   317.3 1487.49   337.1 1470.35
   386.7 1441.94   406.5 1426.53   475.9 1392.24   485.8 1383.07   555.3 1346.19
   575.1 1331.38   600.9 1320.99   614.8 1320.12   644.5 1320.41   733.7 1329.64
   862.6 1337.84   872.6 1341.08   892.4 1352.18   951.9 1371.03   971.7 1379.83
  1031.5 1394.95  1051.5 1402.86  1111.5 1418.89  1131.5 1427.41  1161.5 1431.02
#Mann= 3 , 0 , 0
       0      .1       0   600.9    .045       0   644.5      .1       0
Bank Sta=600.9,644.5
XS Rating Curve= 0 ,0
Exp/Cntr=0.3,0.1

Type RM Length L Ch R = 1 ,86101.7 ,845.6,956.9,1067.9
XS GIS Cut Line= 3
     1837229.509      309809.986     1837592.194      309265.397
     1838563.471       309058.79
#Sta/Elev= 30
       0 1371.71    29.7 1377.72    39.7 1374.08    59.5 1359.82    79.3 1352.01
     119 1320.67   128.9 1314.95   138.8 1312.83   138.9 1312.83   208.9  1312.9
   257.8 1321.62   366.8 1326.06   396.6 1334.45   416.4 1337.26   505.6 1364.12
   525.4  1366.8   634.5  1400.4     704 1399.64   823.1 1406.39   882.7 1396.03
   912.5 1393.82   942.3  1398.2   991.9 1399.02  1061.4 1404.89  1160.7  1408.3
  1369.3 1430.77  1478.5 1451.28  1508.3 1454.03  1538.1 1453.11  1647.3 1439.92
#Mann= 3 , 0 , 0
       0      .1       0   138.9    .045       0   208.9      .1       0
Bank Sta=138.9,208.9
XS Rating Curve= 0 ,0
Exp/Cntr=0.3,0.1

Type RM Length L Ch R = 1 ,85145   ,536.3,530.4,524.4
XS GIS Cut Line= 4
     1837209.298      309806.617      1837586.58      309927.886
     1837811.487      310482.658     1838475.888       310611.71
#Sta/Elev= 30
       0  1373.9   326.9 1322.49   456.2 1321.59     516 1315.72   595.8 1313.26
   628.5 1308.13   655.7 1307.13   675.6 1307.32   685.6 1308.24   705.6 1317.34
   725.5 1320.88   755.5 1333.67   795.4  1375.8   805.4  1384.5   815.3 1389.44
   835.3 1394.39   855.2 1396.46     945 1418.55     955 1418.52   994.9 1426.96
  1104.4  1427.4  1233.8  1408.3  1323.4 1388.58    1403  1359.3    1413 1351.32
  1422.9 1347.28  1452.8 1337.36  1472.7 1332.86  1522.4 1330.63  1671.7 1334.62
#Mann= 3 , 0 , 0
       0      .1       0   628.5    .045       0   675.6      .1       0
Bank Sta=628.5,675.6
XS Rating Curve= 0 ,0
Exp/Cntr=0.3,0.1

Type RM Length L Ch R = 1 ,84614.5 ,1050.4,984.8,919
XS GIS Cut Line= 3
     1836357.045      309877.357     1836960.623      309951.127
     1837519.208      310938.463
#Sta/Elev= 30
       0 1510.28    29.9 1500.82    49.8 1490.62   109.6 1468.51   129.6 1456.03
   189.4 1432.24   209.3 1421.13   259.2 1404.32   279.1 1393.82   338.9 1374.02
   358.9 1363.68   398.7 1350.82   458.5 1345.45   608.1 1340.15   677.7 1328.81
   797.1 1320.24    1036 1306.73  1065.8    1302  1075.8 1301.65  1115.6 1302.12
  1125.5 1304.05  1175.3 1316.11  1205.1 1319.13  1344.4 1361.42    1424 1378.19
  1463.8 1384.08  1583.2    1396  1603.2 1399.99  1672.8 1408.69  1742.5 1413.79
#Mann= 3 , 0 , 0
       0     .06       0  1065.8    .045       0  1125.5      .1       0
Bank Sta=1065.8,1125.5
XS Rating Curve= 0 ,0
Exp/Cntr=0.3,0.1

Type RM Length L Ch R = 1 ,83629.5 ,678.4,679.8,681.4
XS GIS Cut Line= 3
     1835999.974      311133.841     1837114.977      310857.617
     1837283.407      310834.037
#Sta/Elev= 30
       0 1326.75    79.9 1331.14   129.8 1339.06   179.8 1344.68   279.7 1352.43
   329.6 1353.71   369.6 1360.28   389.6 1366.52   429.5 1374.45   469.5 1380.38
   539.4 1385.86   549.4 1384.08   559.4  1379.1   589.3 1358.52   609.3 1342.49
   619.3 1327.34   639.3 1311.67   669.2 1297.25   679.2 1296.13   689.2 1296.08
   739.2 1296.32   759.2 1299.43   789.1 1307.44     929 1308.76  1098.8 1315.17
  1158.7 1326.69  1178.7 1332.74  1238.8 1344.68  1258.8  1350.7  1318.8 1361.68
#Mann= 3 , 0 , 0
       0      .1       0   679.2    .045       0   739.2      .1       0
Bank Sta=679.2,739.2
XS Rating Curve= 0 ,0
Exp/Cntr=0.3,0.1