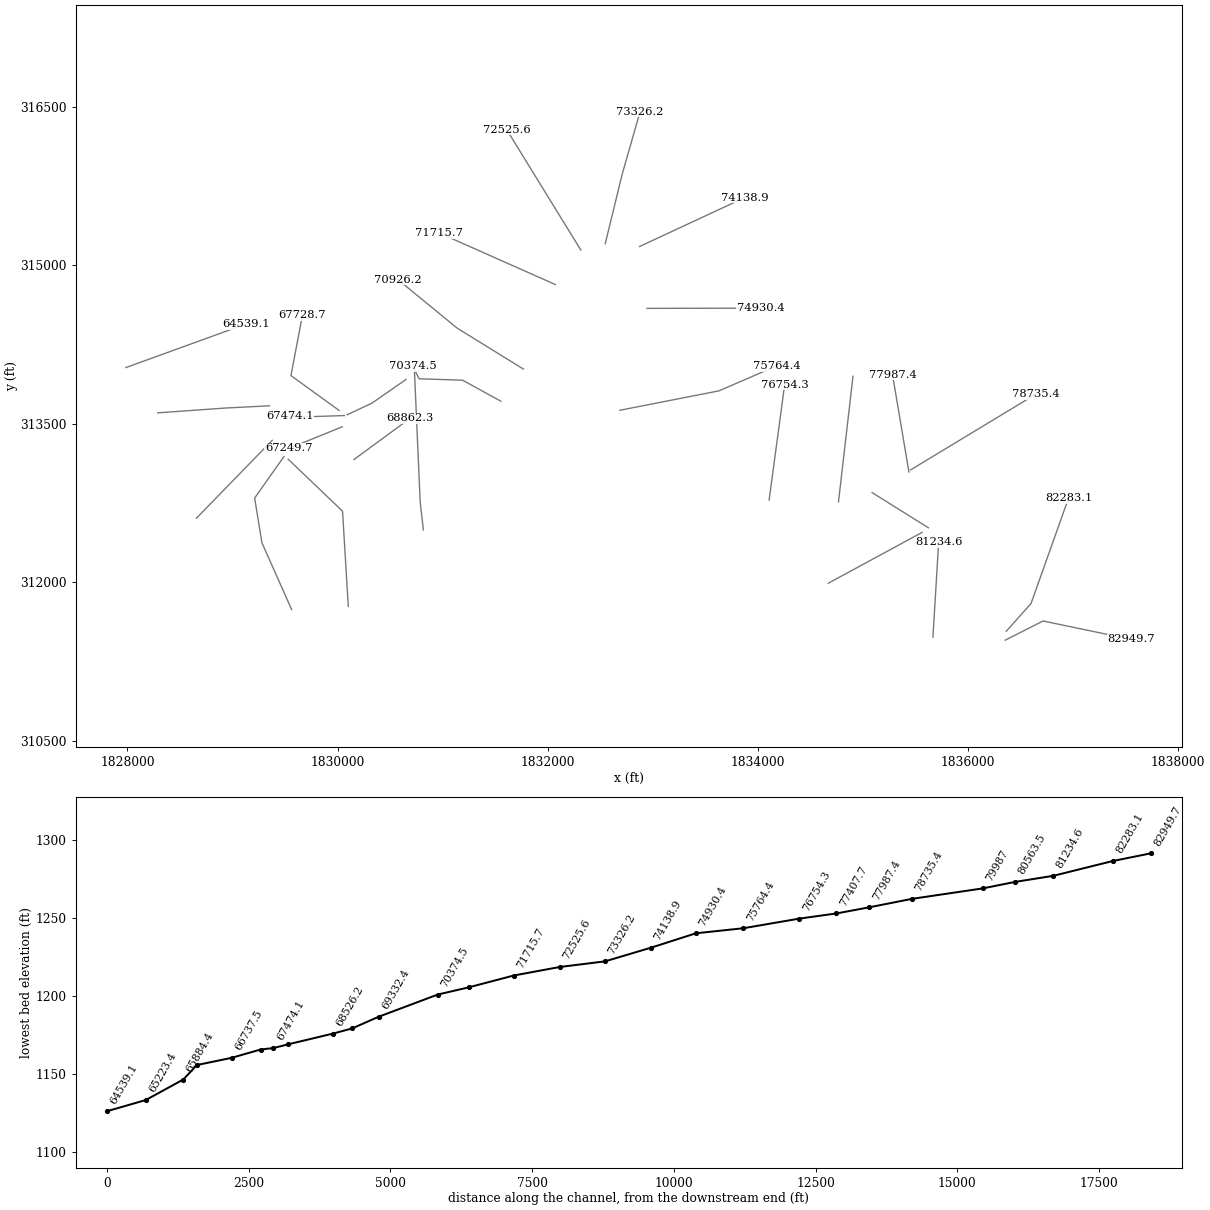
HEC-RAS study MrshFrk1.prj: MrshFrk1

--- MrshFrk1.g01 (geometry) --- (continued)

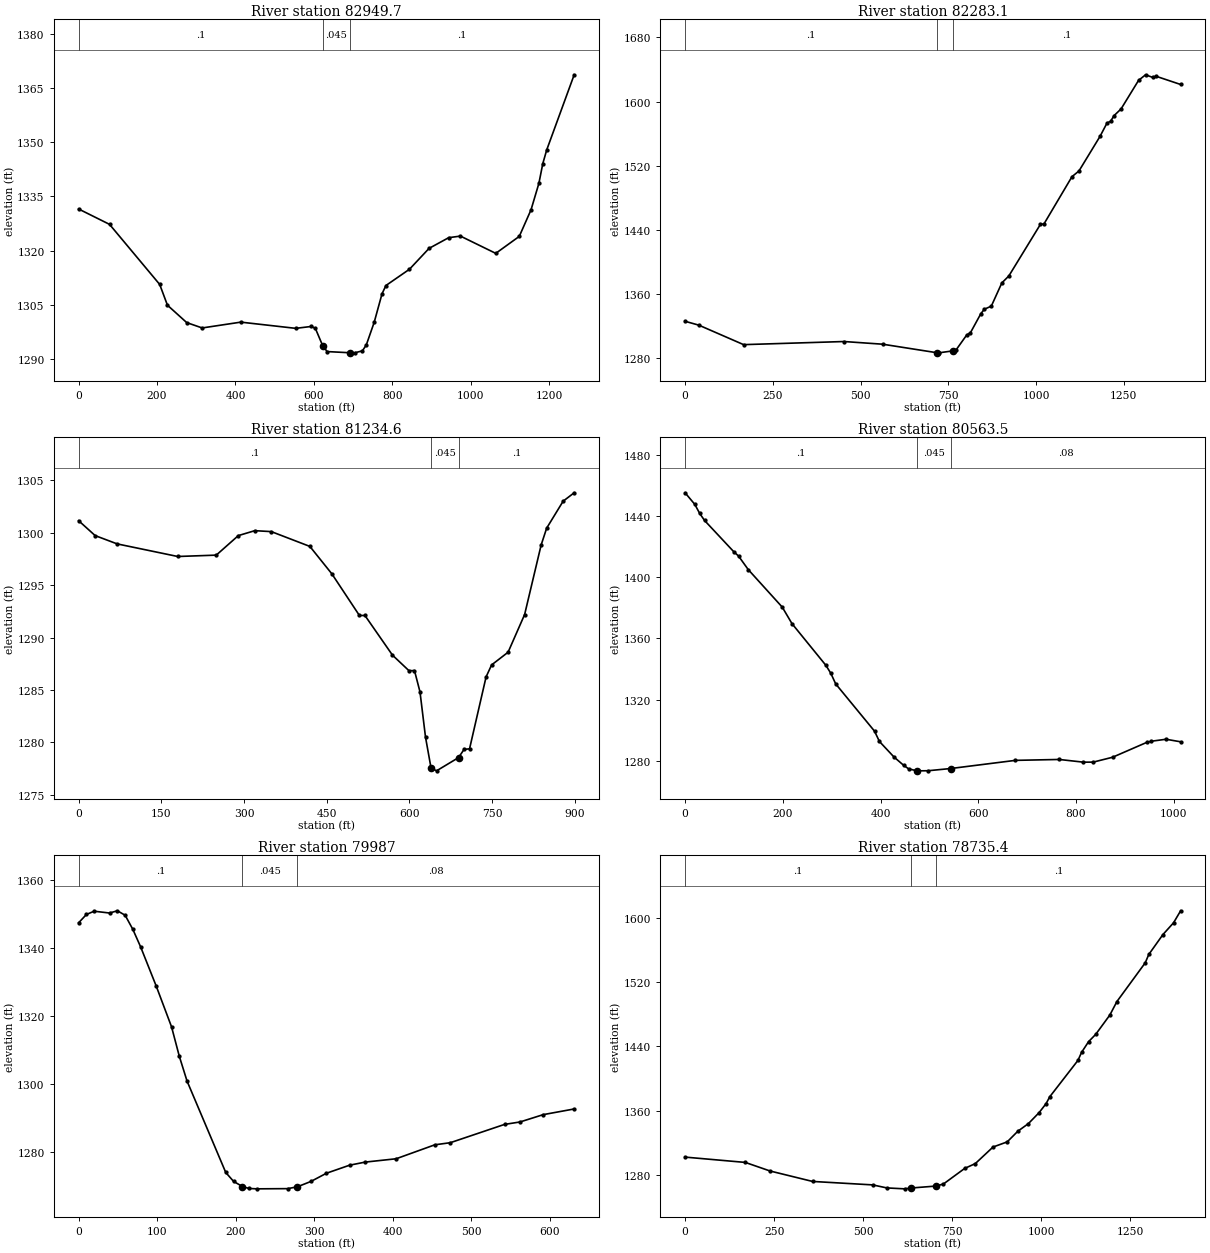
Type RM Length L Ch R = 1 ,82949.7 ,594.1,666.6,739
XS GIS Cut Line= 3
     1836353.676      311450.489     1836714.115      311632.393
     1837556.262      311457.226
#Sta/Elev= 30
       0 1331.52    78.8 1327.27   206.8 1310.63   226.5 1304.89   275.7 1300.07
   315.1 1298.59   413.7  1300.2   553.8 1298.48   593.8 1299.01   603.8 1298.47
   622.4  1293.7   633.8 1292.05   692.4 1291.72   703.8  1291.7   723.8 1292.25
   733.8 1293.91   753.8 1300.14   773.8 1308.04   783.8 1310.34   843.8 1314.84
   893.8 1320.62   943.8 1323.58   973.8 1324.02  1063.9 1319.24  1123.9 1323.94
  1153.9 1331.31  1173.9 1338.62  1183.9  1344.1  1193.9 1347.89  1263.9 1368.68
#Mann= 3 , 0 , 0
       0      .1       0   622.4    .045       0   692.4      .1       0
Bank Sta=622.4,692.4
XS Rating Curve= 0 ,0
Exp/Cntr=0.3,0.1

Type RM Length L Ch R = 1 ,82283.1 ,1035.1,1048.7,1062.3
XS GIS Cut Line= 3
     1836363.782      311534.704     1836599.583      311797.454
     1836956.102      312794.531
#Sta/Elev= 30
       0 1326.13    39.2  1321.3   166.7 1297.02   452.9  1300.9   562.8 1297.57
   718.8 1286.85   722.7  1286.8   762.6 1289.22   772.6 1290.79   802.6 1309.16
   812.6 1311.55   842.5 1335.49   852.5 1341.13   872.5 1345.02   902.5 1373.97
   922.4 1382.63  1012.4 1446.98  1022.4  1447.4  1102.3 1506.41  1122.2  1513.5
  1182.2 1556.63  1202.2 1573.35  1212.2 1575.35  1222.1 1582.45  1242.1 1590.82
  1292.1 1626.49    1312 1633.42    1332 1630.19    1342 1631.56  1411.9 1621.32
#Mann= 3 , 0 , 0
       0      .1       0   718.8    .045       0   762.6      .1       0
Bank Sta=718.8,762.6
XS Rating Curve= 0 ,0
Exp/Cntr=0.3,0.1

Type RM Length L Ch R = 1 ,81234.6 ,722.1,670.8,619.5
XS GIS Cut Line= 2
     1835666.016      311479.495     1835720.381      312376.851
#Sta/Elev= 30
       0 1301.13      30 1299.71    69.9 1298.92   179.8 1297.72   249.7 1297.85
   289.7 1299.71   319.6 1300.18   349.6 1300.09   419.5 1298.68   459.5 1296.06
   509.4  1292.1   519.4  1292.1   569.4 1288.32   599.3 1286.84   609.3 1286.85
   619.3 1284.82   629.3 1280.51   639.3 1277.58   649.3  1277.3   689.2 1278.56
   699.2 1279.34   709.2  1279.4   739.2 1286.25   749.2 1287.39   779.1  1288.6
   809.1 1292.19   839.1 1298.82   849.1 1300.42     879 1302.99     899 1303.79
#Mann= 3 , 0 , 0
       0      .1       0   639.3    .045       0   689.2      .1       0
Bank Sta=639.3,689.2
XS Rating Curve= 0 ,0
Exp/Cntr=0.3,0.1

Type RM Length L Ch R = 1 ,80563.5 ,629.7,576.5,523.4
XS GIS Cut Line= 2
     1834669.381      311989.463     1835562.057      312471.172
#Sta/Elev= 30
       0 1455.23    19.9 1447.64    29.8 1441.78    39.8 1437.13    99.4 1416.77
   109.4 1413.85   129.3 1404.99   198.9 1380.45   218.8 1369.66   288.4 1342.31
   298.3 1337.18   308.3 1330.24   387.8 1299.34   397.8 1292.61   427.6 1282.44
   447.5 1276.99   457.4 1274.74   473.8 1273.46   477.3  1273.4   497.2 1273.46
   543.8 1274.92   676.2 1280.25   765.7 1280.84   815.5 1279.07   835.4  1279.1
   875.1 1282.29   944.7 1291.96   954.7 1292.78   984.5 1294.05  1014.4 1292.39
#Mann= 3 , 0 , 0
       0      .1       0   473.8    .045       0   543.8     .08       0
Bank Sta=473.8,543.8
XS Rating Curve= 0 ,0
Exp/Cntr=0.3,0.1

Type RM Length L Ch R = 1 ,79987   ,1195.7,1251.6,1307.5
XS GIS Cut Line= 2
     1835087.086      312848.454     1835622.692      312514.963
#Sta/Elev= 30
       0 1347.51     9.9 1349.95    19.7 1350.91    39.4 1350.38    49.3 1351.04
    59.2 1349.73      69 1345.58    78.9 1340.43    98.6 1328.99   118.3 1316.88
   128.2  1308.2     138 1300.94   187.3 1274.02   197.2 1271.41   208.5 1269.88
   216.9 1269.31   226.8  1269.2   266.2 1269.26   278.5  1269.8   295.8 1271.38
   315.5 1273.79     345 1276.16   364.8 1277.07   404.2 1278.05   453.5 1282.16
   473.2 1282.78   542.2 1288.16   561.9 1288.88   591.5 1291.04   630.9 1292.71
#Mann= 3 , 0 , 0
       0      .1       0   208.5    .045       0   278.5     .08       0
Bank Sta=208.5,278.5
XS Rating Curve= 0 ,0
Exp/Cntr=0.3,0.1

Type RM Length L Ch R = 1 ,78735.4 ,686.9,747.9,809
XS GIS Cut Line= 2
     1835454.262      313064.043     1836646.743      313781.553
#Sta/Elev= 30
       0 1301.99     169 1295.38   238.6 1284.69   357.9 1271.68   526.9 1267.37
   566.6  1263.6   616.3 1262.46   635.7 1263.53   705.7 1265.95   725.7 1268.55
   785.3 1287.92   815.1 1293.93   864.8 1314.55   904.6 1320.95   934.4 1334.21
   964.2 1343.74   994.1 1357.34    1014 1368.72  1023.9 1377.03  1103.4 1422.53
  1113.4 1432.41  1133.2 1445.84  1153.1 1454.88  1192.9 1478.99  1212.8 1495.83
  1292.3 1544.06  1302.2 1554.41    1342 1579.25  1371.8  1593.9  1391.7 1608.86
#Mann= 3 , 0 , 0
       0      .1       0   635.7    .045       0   705.7      .1       0
Bank Sta=635.7,705.7
XS Rating Curve= 0 ,0
Exp/Cntr=0.3,0.1

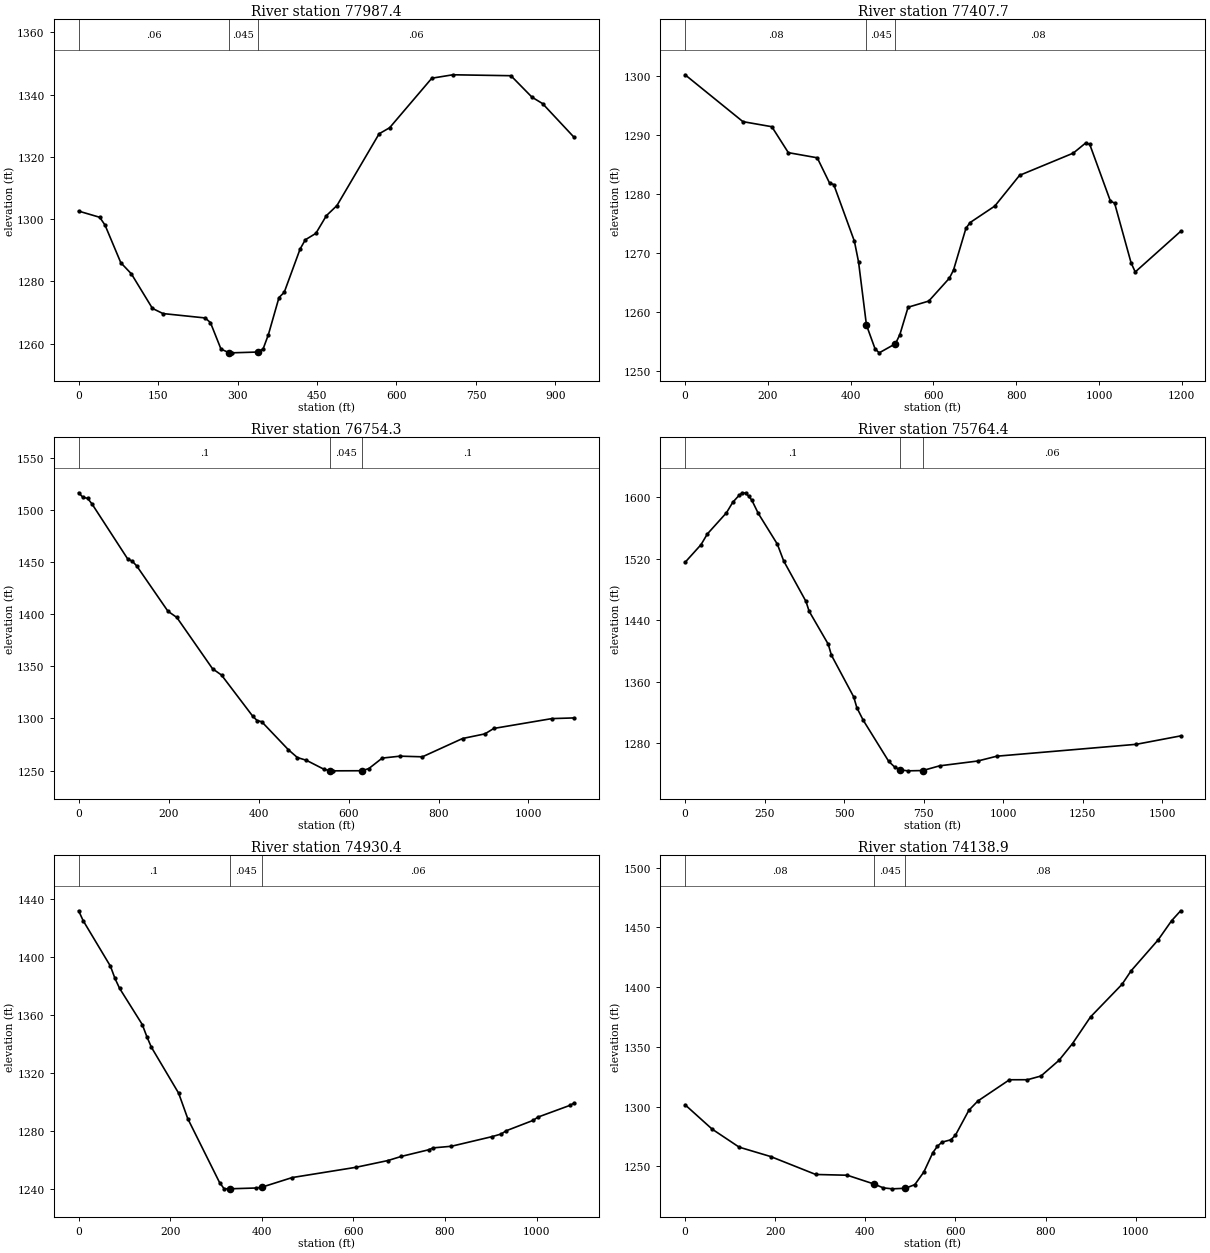
Type RM Length L Ch R = 1 ,77987.4 ,594.1,579.8,565.4
XS GIS Cut Line= 2
      1835437.42      313043.832     1835281.108      313966.105
#Sta/Elev= 30
       0  1302.6    39.8 1300.61    49.8 1298.11    79.6 1286.02    99.5 1282.45
   139.3 1271.34   159.2 1269.68   238.8 1268.27   248.8 1266.78   268.7 1258.27
   283.9 1257.09   288.6 1257.06   338.4 1257.32   348.3 1258.35   358.2 1262.91
   378.2 1274.82   388.1 1276.51     418  1290.4   427.9 1293.39   447.8 1295.44
   467.7 1301.14   487.6 1304.38   567.2 1327.44   587.1 1329.39   666.7  1345.3
   706.5  1346.4     816  1346.1   855.8  1339.2   875.7 1337.15   935.4 1326.28
#Mann= 3 , 0 , 0
       0     .06       0   283.9    .045       0   338.4     .06       0
Bank Sta=283.9,338.4
XS Rating Curve= 0 ,0
Exp/Cntr=0.3,0.1

Type RM Length L Ch R = 1 ,77407.7 ,654,653.2,652.4
XS GIS Cut Line= 2
      1834767.07      312760.871     1834905.182      313949.983
#Sta/Elev= 30
       0 1300.28   139.7 1292.33   209.5 1291.47   249.4 1287.07   319.2  1286.2
   349.2 1281.88   359.1 1281.66     409 1272.04     419 1268.54   438.1 1257.82
   458.9 1253.79   468.9 1253.11   508.1 1254.65   518.8  1256.2   538.7 1260.85
   588.6 1261.89   638.5 1265.78   648.4 1267.15   678.4 1274.23   688.3  1275.2
   748.2 1278.01     808 1283.22   937.7 1286.99   967.7 1288.71   977.6 1288.46
  1027.5 1278.84  1037.5 1278.52  1077.4 1268.38  1087.4 1266.83  1197.1 1273.72
#Mann= 3 , 0 , 0
       0     .08       0   438.1    .045       0   508.1     .08       0
Bank Sta=438.1,508.1
XS Rating Curve= 0 ,0
Exp/Cntr=0.3,0.1

Type RM Length L Ch R = 1 ,76754.3 ,1052.5,989.9,927.2
XS GIS Cut Line= 2
     1834106.826      312777.713     1834254.552      313869.411
#Sta/Elev= 30
       0 1516.26     9.9 1511.75    19.8 1511.02    29.8 1505.52   109.2 1452.77
   119.1 1450.77     129 1446.24   198.5 1402.77   218.3 1396.79   297.7 1347.63
   317.6  1341.6   387.1 1302.12     397  1297.9   406.9 1296.92   466.5 1269.92
   486.3 1262.54   506.2 1259.93   545.9  1251.2   559.9 1249.86   565.7  1249.8
   629.9  1249.9   645.1 1251.97   674.9 1262.02   714.6 1263.87   764.2 1263.24
   853.5 1280.78   903.2 1285.22     923 1290.44    1052 1299.86  1101.6 1300.52
#Mann= 3 , 0 , 0
       0      .1       0   559.9    .045       0   629.9      .1       0
Bank Sta=559.9,629.9
XS Rating Curve= 0 ,0
Exp/Cntr=0.3,0.1

Type RM Length L Ch R = 1 ,75764.4 ,843.6,834,824.5
XS GIS Cut Line= 3
     1832686.588      313628.305     1833628.487       313811.87
     1834177.567      314047.672
#Sta/Elev= 30
       0 1515.47      50 1538.48      70 1552.47     130 1580.08   149.9 1593.79
   169.9  1602.9   179.9 1606.13   189.9 1605.74   199.9 1601.76   209.9 1596.33
   229.9 1579.27   289.9 1539.14   309.9 1517.18   379.8 1464.52   389.8 1451.67
   449.8 1408.71   459.8  1394.4   529.8 1340.04   539.8 1325.84   559.8 1309.55
   639.8    1256   659.7 1248.09   676.8 1244.86   699.7  1243.6   746.8 1243.98
   799.7 1250.12   919.6 1256.41   979.5 1262.69  1417.8 1278.19  1557.2 1289.16
#Mann= 3 , 0 , 0
       0      .1       0   676.8    .045       0   746.8     .06       0
Bank Sta=676.8,746.8
XS Rating Curve= 0 ,0
Exp/Cntr=0.3,0.1

Type RM Length L Ch R = 1 ,74930.4 ,769.6,791.5,813.4
XS GIS Cut Line= 2
     1832944.663      314593.383      1834026.86      314595.414
#Sta/Elev= 30
       0  1431.6     9.9 1424.79    69.5 1393.47    79.4 1385.04    89.4 1378.29
     139 1353.35   148.9 1345.11   158.8 1337.81   218.4 1306.16   238.3 1288.68
   307.8  1244.7   317.7 1240.45   327.6 1240.38     330 1240.41   387.2 1240.95
     400 1241.52   466.6 1248.15   605.6 1255.19   675.1 1259.81   704.9 1262.69
   764.5 1267.25   774.4 1268.55   814.1 1269.66   903.5 1276.33   923.3 1278.15
   933.3 1280.26   992.8 1287.49  1002.8 1289.67  1072.3 1297.71  1082.2 1299.37
#Mann= 3 , 0 , 0
       0      .1       0     330    .045       0     400     .06       0
Bank Sta=330,400
XS Rating Curve= 0 ,0
Exp/Cntr=0.3,0.1

Type RM Length L Ch R = 1 ,74138.9 ,767.3,812.7,856.1
XS GIS Cut Line= 2
     1832873.923      315179.518     1833871.944      315641.294
#Sta/Elev= 30
       0 1301.52      60 1281.14     120 1266.04   189.9 1258.18   289.9 1243.17
   359.9 1242.53     419 1235.21   439.9 1231.94   459.9 1231.14     489 1231.63
   509.8 1234.67   529.8 1245.22   549.8 1261.46   559.8 1266.71   569.8 1270.18
   589.8 1272.23   599.8 1275.96   629.8 1296.96   649.8 1304.72   719.8 1322.47
   759.8 1322.51   789.8 1325.62   829.8 1338.76   859.8 1352.82   899.7 1375.09
   969.7 1402.41   989.7 1413.66  1049.7 1439.56  1079.7 1455.67  1099.7 1463.97
#Mann= 3 , 0 , 0
       0     .08       0     419    .045       0     489     .08       0
Bank Sta=419,489
XS Rating Curve= 0 ,0
Exp/Cntr=0.3,0.1

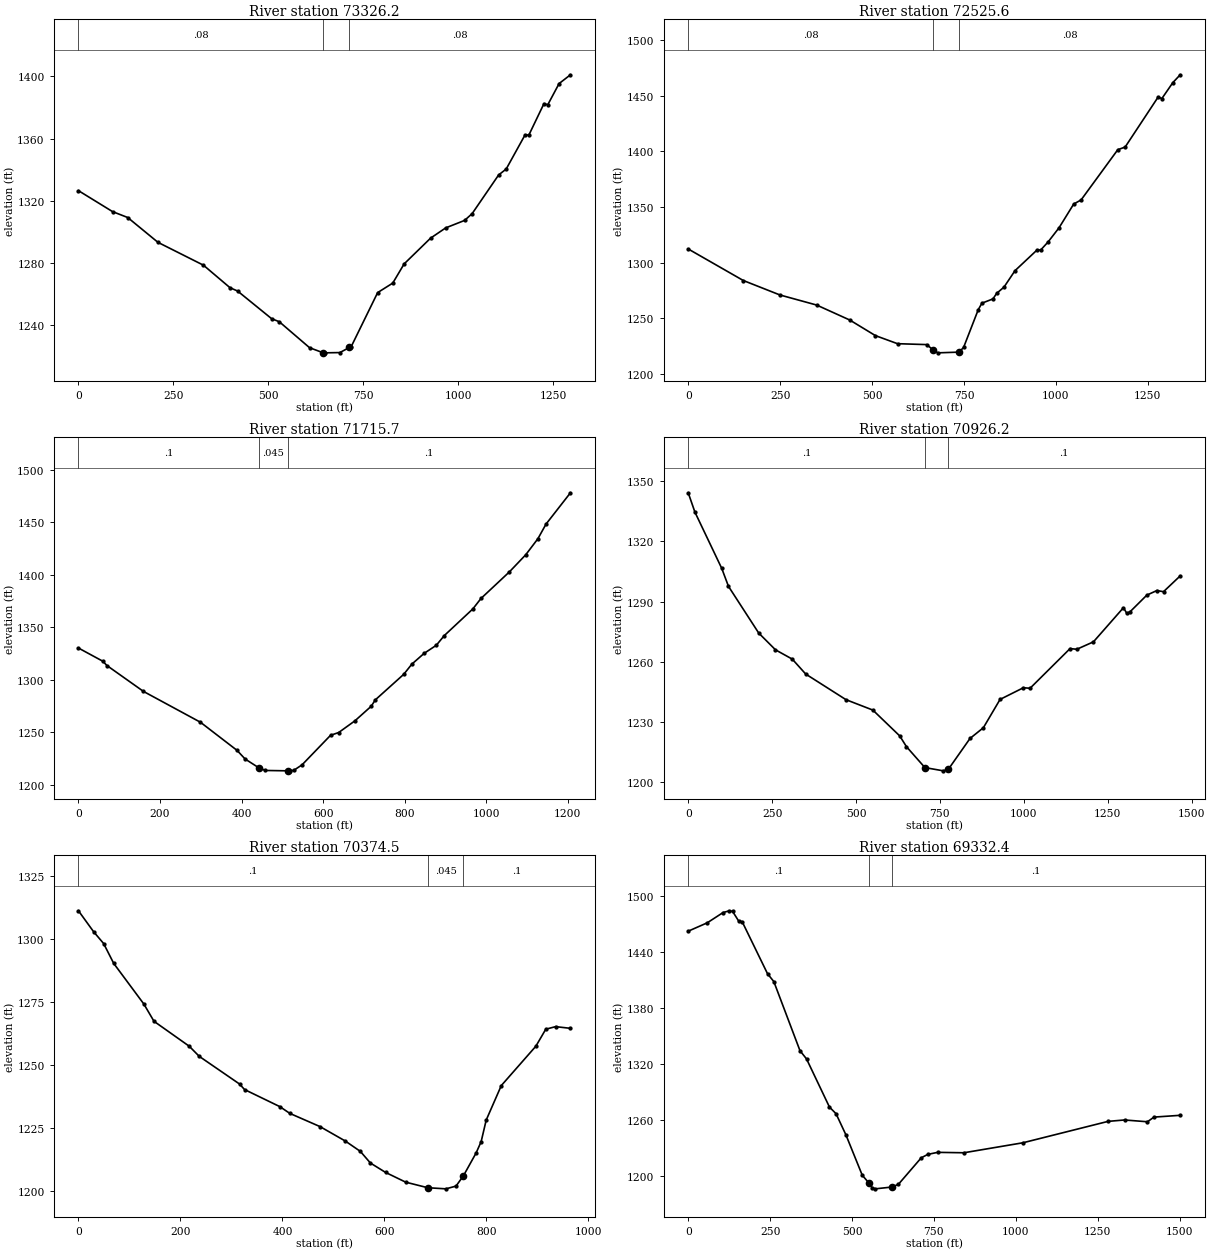
Type RM Length L Ch R = 1 ,73326.2 ,760.8,800.6,842.5
XS GIS Cut Line= 3
     1832547.169      315206.466     1832708.579      315865.006
     1832878.888      316457.756
#Sta/Elev= 30
       0 1326.51    89.7 1313.05   129.6 1309.26   209.4 1293.28     329 1278.62
   398.8 1264.17   418.8 1262.03   508.5 1244.24   528.5 1242.32   608.2 1225.63
     643 1222.46   648.1 1222.33     688  1222.5     713 1225.78   717.8 1226.32
   787.4 1261.02   827.2 1267.14   857.1 1279.46   926.7    1296   966.5 1302.59
  1016.2 1307.39  1036.1 1311.76  1105.8  1336.6  1125.7  1340.4  1175.4 1362.36
  1185.3  1362.2  1225.1 1382.42  1235.1 1381.68  1264.9 1395.29  1294.8 1400.94
#Mann= 3 , 0 , 0
       0     .08       0     643    .045       0     713     .08       0
Bank Sta=643,713
XS Rating Curve= 0 ,0
Exp/Cntr=0.3,0.1

Type RM Length L Ch R = 1 ,72525.6 ,779.5,809.9,840.2
XS GIS Cut Line= 2
     1832314.737      315145.832     1831610.619       316283.59
#Sta/Elev= 30
       0 1312.23   149.8 1283.83   249.6 1270.79   349.5 1261.71   439.4 1248.24
   509.2  1234.2   569.2 1226.94     649 1226.11   666.6 1221.06     679  1218.7
   736.6 1219.34   748.9 1223.55   788.8 1257.57   798.8 1263.43   828.8 1267.26
   838.8 1272.24   858.7 1277.84   888.7 1292.67   948.6 1311.28   958.6 1311.29
   978.6  1318.5  1008.5  1331.3  1048.4  1352.7  1068.4 1356.35  1168.3 1401.62
  1188.2 1403.97  1278.1 1449.07  1288.1 1447.65    1318 1462.02    1338 1469.06
#Mann= 3 , 0 , 0
       0     .08       0   666.6    .045       0   736.6     .08       0
Bank Sta=666.6,736.6
XS Rating Curve= 0 ,0
Exp/Cntr=0.3,0.1

Type RM Length L Ch R = 1 ,71715.7 ,796.1,789.4,776.1
XS GIS Cut Line= 2
     1832072.198      314819.079      1830968.57      315306.705
#Sta/Elev= 30
       0  1330.3    59.8 1317.71    69.8 1313.63   159.5 1288.93   299.2 1259.55
   388.9 1232.75   408.8 1224.49   442.8 1216.03   458.7 1213.59   512.8 1213.24
   518.5 1213.23   528.5 1213.83   548.4 1218.96   618.2 1247.09   638.2 1249.76
   678.1 1260.93     718 1274.81   727.9 1280.84   797.7 1305.24   817.7 1314.98
   847.6 1325.18   877.5  1332.9   897.4 1342.25   967.2 1367.58   987.2 1377.56
    1057 1402.95  1096.9  1419.2  1126.8 1434.53  1146.7 1448.46  1206.6 1478.31
#Mann= 3 , 0 , 0
       0      .1       0   442.8    .045       0   512.8      .1       0
Bank Sta=442.8,512.8
XS Rating Curve= 0 ,0
Exp/Cntr=0.3,0.1

Type RM Length L Ch R = 1 ,70926.2 ,525.7,551.8,584.6
XS GIS Cut Line= 3
      1831767.43      314018.875     1831136.893      314406.807
      1830574.37      314865.226
#Sta/Elev= 30
       0 1344.16      20 1334.53     100 1306.48     120 1297.55   210.1  1274.3
   260.1 1265.94   310.1 1261.31   350.2 1253.87   470.2 1241.11   550.2 1235.93
   630.3 1223.06   650.3 1217.71   705.3 1207.29   760.2 1205.67   775.3 1206.47
   839.7  1221.8   879.5 1227.14   929.2 1241.24   998.8 1247.06  1018.6 1246.79
  1137.9 1266.57  1157.8 1266.21  1207.5 1269.92    1297 1286.94  1306.9 1284.06
  1316.9 1284.95  1366.6 1293.19  1396.4 1295.46  1416.3  1294.9    1466 1302.77
#Mann= 3 , 0 , 0
       0      .1       0   705.3    .045       0   775.3      .1       0
Bank Sta=705.3,775.3
XS Rating Curve= 0 ,0
Exp/Cntr=0.3,0.1

Type RM Length L Ch R = 1 ,70374.5 ,1117.4,1042.1,966.7
XS GIS Cut Line= 4
     1831553.436      313714.181     1831189.628      313912.928
     1830775.291      313926.402     1830714.657      314047.672
#Sta/Elev= 30
       0 1311.17    29.6  1302.9    49.4 1298.18    69.1 1290.33   128.3  1274.2
   148.1 1267.38   217.2  1257.5   236.9 1253.48   315.8 1242.53   325.7 1240.33
   394.8 1233.57   414.6 1230.87   473.8 1225.64   523.1 1219.95   552.7 1215.84
   572.5 1211.21   602.1 1207.51   641.6 1203.64   684.9 1201.43   720.5 1200.99
   740.3 1202.08   754.9 1206.18   779.8 1215.24   789.6  1219.7   799.5 1228.24
   829.1 1241.91   896.9 1257.51   916.3 1264.24   935.6 1265.26   964.7 1264.59
#Mann= 3 , 0 , 0
       0      .1       0   684.9    .045       0   754.9      .1       0
Bank Sta=684.9,754.9
XS Rating Curve= 0 ,0
Exp/Cntr=0.3,0.1

Type RM Length L Ch R = 1 ,69332.4 ,520.2,470.1,420
XS GIS Cut Line= 3
     1830816.035      312494.839     1830785.397      312764.239
       1830731.5      313993.774
#Sta/Elev= 30
       0 1461.93    58.1 1470.87   106.5 1481.86   125.9 1483.73   135.6 1483.03
   154.9 1472.28   164.6 1472.18   242.1 1416.51   261.4 1408.08   341.2 1334.28
   361.2 1325.51   431.2 1274.06   451.2 1267.02   481.3 1244.49   531.3 1201.28
   551.5 1193.04   561.3 1187.98   571.3 1186.74   621.5 1188.66   641.4 1191.47
   711.4 1219.91   731.4 1223.54   761.4 1225.71   841.5 1225.27  1021.6 1235.93
  1281.7  1258.8  1331.8 1260.29  1401.8 1258.38  1421.8 1263.36  1501.8 1265.27
#Mann= 3 , 0 , 0
       0      .1       0   551.5    .045       0   621.5      .1       0
Bank Sta=551.5,621.5
XS Rating Curve= 0 ,0
Exp/Cntr=0.3,0.1

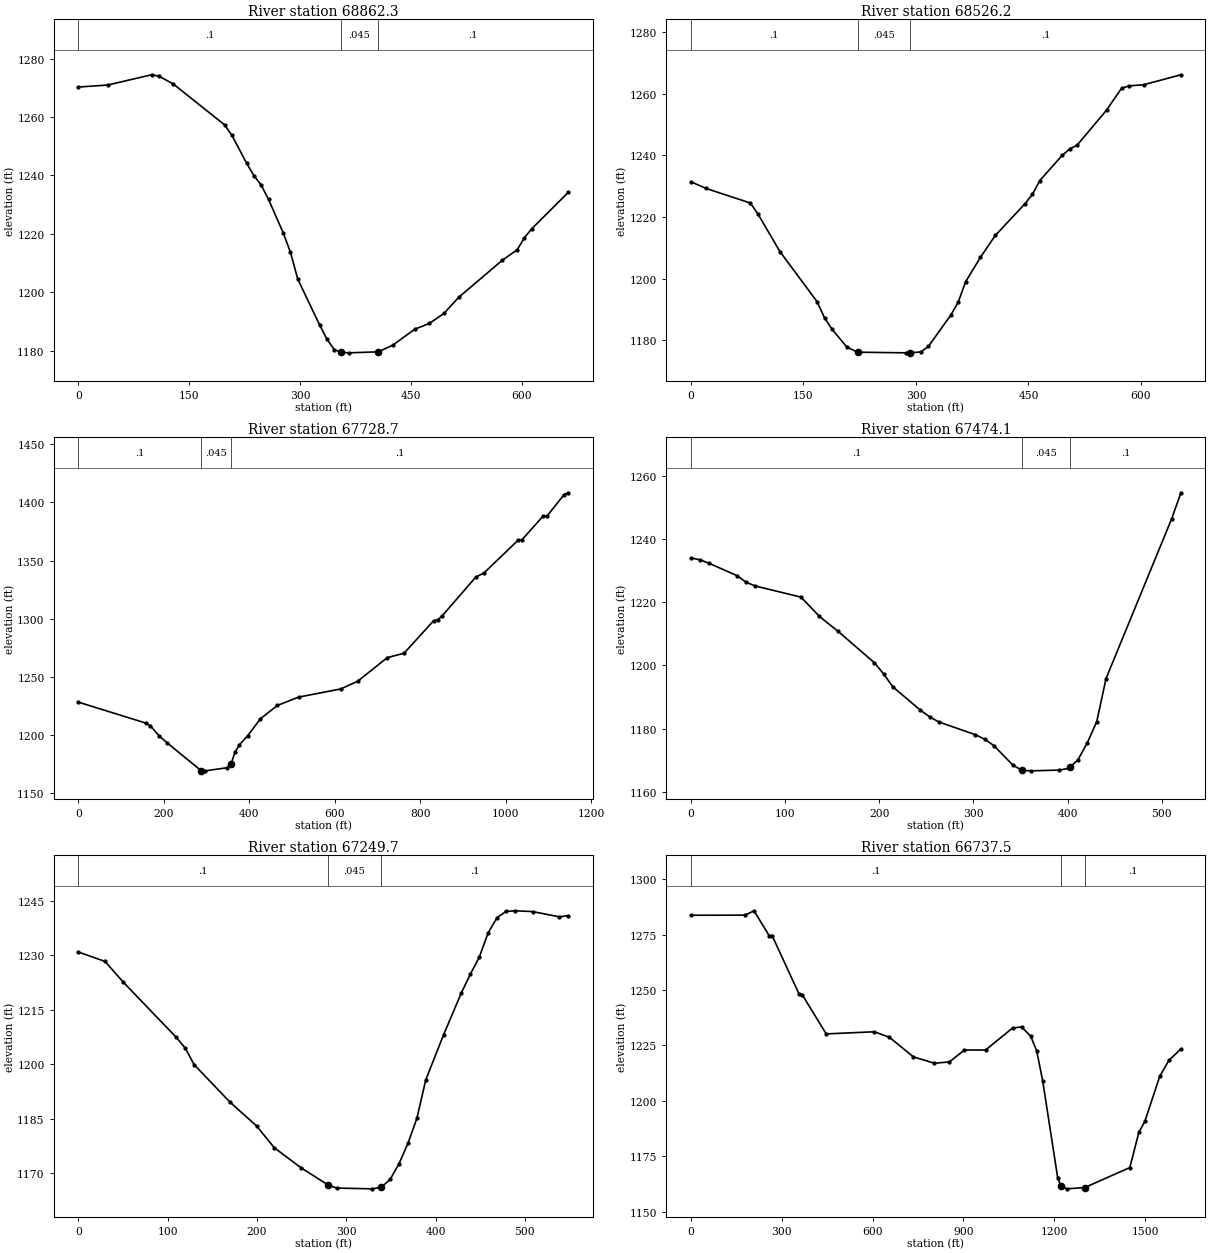
Type RM Length L Ch R = 1 ,68862.3 ,346,336.1,334.7
XS GIS Cut Line= 2
     1830155.471      313161.732     1830691.077      313552.489
#Sta/Elev= 30
       0 1270.24    39.6 1270.92      99 1274.44   108.8    1274   128.6 1271.26
   197.9 1257.28   207.8 1253.68   227.6 1244.19   237.5 1239.91   247.4 1236.67
   257.3 1231.78   277.1 1220.35     287 1213.64   296.9 1204.43   326.6  1188.7
   336.4 1183.86   346.3 1180.33   355.1 1179.41   366.1  1179.2   405.7 1179.55
   425.1 1181.77   455.2 1187.29     475 1189.27   494.8 1192.73   514.6 1198.21
   573.9 1210.96   593.7 1214.47   603.6 1218.64   613.5 1221.69     663 1234.19
#Mann= 3 , 0 , 0
       0      .1       0   355.1    .045       0   405.7      .1       0
Bank Sta=355.1,405.7
XS Rating Curve= 0 ,0
Exp/Cntr=0.3,0.1

Type RM Length L Ch R = 1 ,68526.2 ,692.4,797.6,894.2
XS GIS Cut Line= 3
     1830091.468      313586.175     1830324.806       313694.42
     1830650.654      313919.665
#Sta/Elev= 30
       0 1231.45    19.8 1229.31    79.2 1224.55      89 1221.13   118.7 1208.77
   168.2 1192.52   178.1 1187.29     188 1183.61   207.8 1177.82   222.2 1176.12
   286.9 1175.91   292.2 1175.92   306.7 1176.22   316.6 1177.98   346.4 1188.14
   356.2 1192.26   366.2 1198.99     386 1206.91   405.8 1214.01   445.4 1224.32
   455.3 1227.38   465.2 1231.85   494.9    1240   504.8 1242.06   514.7 1243.28
   554.3 1254.75   574.1 1261.79     584 1262.57   603.8 1262.96   653.3 1266.18
#Mann= 3 , 0 , 0
       0      .1       0   222.2    .045       0   292.2      .1       0
Bank Sta=222.2,292.2
XS Rating Curve= 0 ,0
Exp/Cntr=0.3,0.1

Type RM Length L Ch R = 1 ,67728.7 ,223.8,254.5,284.9
XS GIS Cut Line= 3
      1830013.99      313626.598     1829555.862       313956.72
     1829664.838      314527.879
#Sta/Elev= 30
       0 1228.12   158.5 1209.98   168.4 1207.72   188.2 1199.32     208 1192.93
   287.4 1169.06   297.2 1168.95   346.7 1171.58   357.4 1175.26   366.6 1185.14
   376.4 1191.25   396.3 1199.27     426 1213.82   465.6 1225.26   515.2 1232.42
     614 1239.48   653.4 1246.06   722.4 1266.39   761.8 1270.18   830.8 1298.11
   840.6 1299.03   850.5 1302.16   929.3 1335.61     949 1339.38  1027.9 1367.26
  1037.7 1367.87    1087 1388.23  1096.9  1388.6  1136.3 1406.82  1146.1 1408.33
#Mann= 3 , 0 , 0
       0      .1       0   287.4    .045       0   357.4      .1       0
Bank Sta=287.4,357.4
XS Rating Curve= 0 ,0
Exp/Cntr=0.3,0.1

Type RM Length L Ch R = 1 ,67474.1 ,204.1,224.5,245.1
XS GIS Cut Line= 3
     1830065.374       313578.25     1829743.913      313567.796
     1829545.286      313573.023
#Sta/Elev= 30
       0    1234     9.8 1233.39    19.5 1232.25    48.7 1228.42    58.5 1226.32
    68.2 1225.12     117 1221.57   136.4 1215.48   155.9 1210.85   194.9 1200.79
   204.7 1197.25   214.4 1193.19   243.7  1185.8   253.4 1183.71   263.2 1182.07
   302.1 1178.04   311.9 1176.62   321.6 1174.61   341.5 1168.52   351.4 1166.75
   361.4  1166.6   391.2 1166.84   401.1 1167.38   402.4 1167.74     411 1170.11
     421 1175.53   430.9 1182.14   440.8 1195.82   510.4 1246.32   520.3 1254.61
#Mann= 3 , 0 , 0
       0      .1       0   351.4    .045       0   402.4      .1       0
Bank Sta=351.4,402.4
XS Rating Curve= 0 ,0
Exp/Cntr=0.3,0.1

Type RM Length L Ch R = 1 ,67249.7 ,570.9,512.1,453.3
XS GIS Cut Line= 2
     1830044.307      313471.643      1829535.65      313266.159
#Sta/Elev= 30
       0  1230.9    29.9 1228.31    49.9 1222.71   109.7 1207.38   119.7 1204.42
   129.7 1199.87   169.6  1189.6   199.5    1183   219.4 1176.99   249.4 1171.47
   279.1 1166.82   289.3 1165.89   329.2 1165.68   339.1 1166.12   349.1 1168.28
   359.1 1172.64     369 1178.18     379 1185.06     389 1195.71     409 1208.16
   428.9 1219.68   438.9 1224.81   448.8 1229.42   458.8 1236.17   468.8 1240.38
   478.8 1242.07   488.8 1242.26   508.7 1242.04   538.6 1240.59   548.6 1240.94
#Mann= 3 , 0 , 0
       0      .1       0   279.1    .045       0   339.1      .1       0
Bank Sta=279.1,339.1
XS Rating Curve= 0 ,0
Exp/Cntr=0.3,0.1

Type RM Length L Ch R = 1 ,66737.5 ,688,611,529.2
XS GIS Cut Line= 3
     1830101.573      311770.505     1830046.754      312672.318
     1829528.913      313165.101
#Sta/Elev= 30
       0 1283.73   178.7 1283.78   208.5 1285.75   258.1 1274.57   268.1 1274.56
   357.4 1248.11   367.4 1247.91   446.8 1230.21   605.6 1231.17   655.3 1228.71
   734.7 1219.85   804.2 1216.97   853.8 1217.58   903.5 1222.96     973 1222.92
  1062.3 1232.87  1092.1 1233.34  1121.9 1229.22  1141.8 1222.67  1161.6 1209.17
  1211.3 1165.31  1221.2  1161.8    1241 1160.32  1300.6  1160.9  1449.5  1169.9
  1479.3 1185.76  1499.2 1190.76  1548.8 1211.23  1578.6 1218.26  1618.3 1223.43
#Mann= 3 , 0 , 0
       0      .1       0  1221.2    .045       0  1300.6      .1       0
Bank Sta=1221.2,1300.6
XS Rating Curve= 0 ,0
Exp/Cntr=0.3,0.1

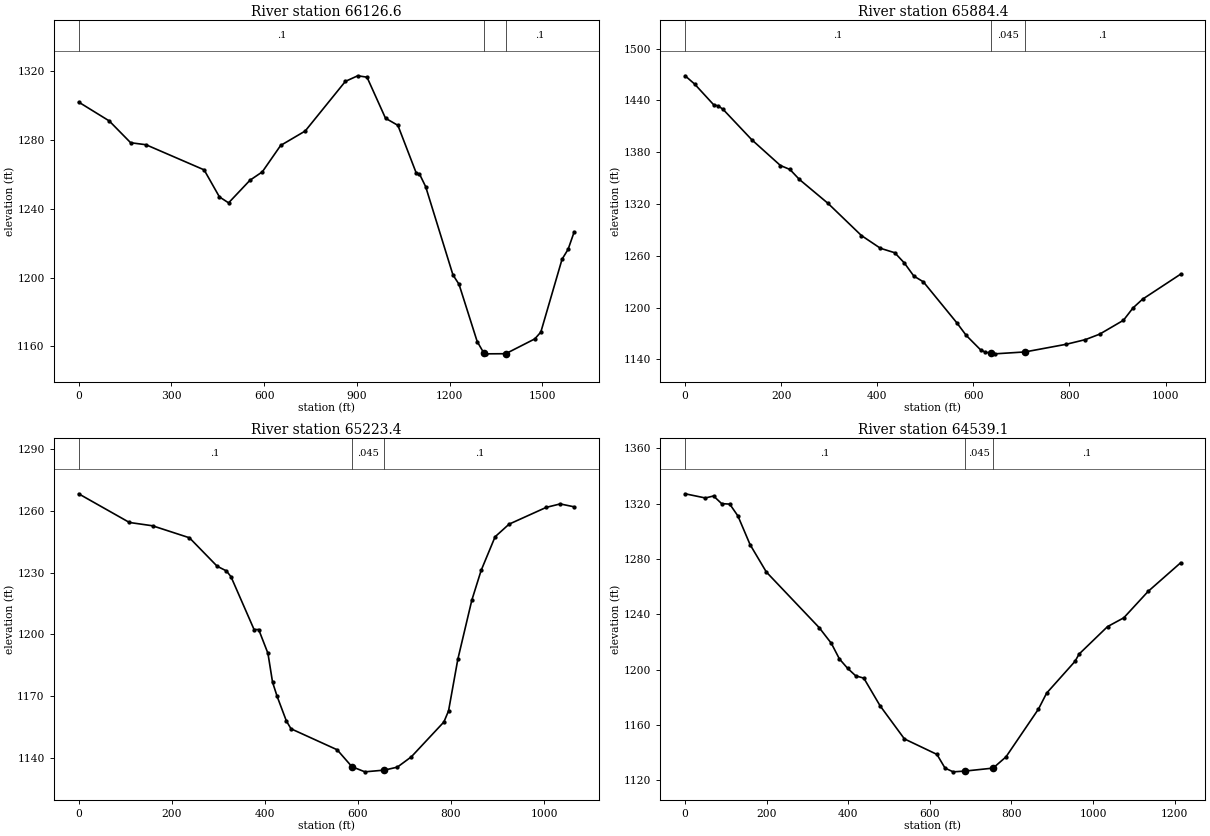
Type RM Length L Ch R = 1 ,66126.6 ,251.8,242.1,232.4
XS GIS Cut Line= 4
     1829562.599      311740.188     1829279.466      312372.905
     1829210.281      312796.942      1829488.49      313188.681
#Sta/Elev= 30
       0 1301.99      99 1291.03   168.3 1278.36   217.9  1277.2     406  1262.6
   455.5 1246.89   485.2 1243.43   554.5 1256.59   594.2 1261.42   653.6 1276.78
   733.1 1285.17     863    1314     903 1317.26     933 1316.45   992.9 1292.59
  1032.9 1288.47  1092.8 1260.52  1102.8  1260.2  1122.8 1252.84  1211.1 1201.56
  1230.7 1196.13  1289.5 1162.86  1311.8 1155.93  1318.9 1155.71  1381.8 1155.78
  1475.8 1164.38  1495.4 1168.34  1564.1 1210.68  1583.7 1216.45  1603.3 1226.54
#Mann= 3 , 0 , 0
       0      .1       0  1311.8    .045       0  1381.8      .1       0
Bank Sta=1311.8,1381.8
XS Rating Curve= 0 ,0
Exp/Cntr=0.3,0.1

Type RM Length L Ch R = 1 ,65884.4 ,696.4,661.1,625.1
XS GIS Cut Line= 2
     1828656.448      312605.915     1829377.327      313343.636
#Sta/Elev= 30
       0 1468.51    19.8 1458.95    59.5  1434.9    69.4 1433.48    79.3 1429.47
   138.8  1394.4   198.4 1364.56   218.2 1359.97     238 1348.35   297.5 1320.68
     367 1283.42   406.6 1268.65   436.4 1263.49   456.2 1251.72   476.1 1236.48
   495.9 1229.79   565.3 1182.51   585.2 1167.68   614.9 1151.06   624.8 1148.24
   637.5 1147.14   644.7 1146.37   707.5 1148.58   793.4 1157.46   833.1 1162.84
   862.8 1169.16   912.4 1185.28   932.3 1199.57   952.1 1209.66  1031.4 1238.69
#Mann= 3 , 0 , 0
       0      .1       0   637.5    .045       0   707.5      .1       0
Bank Sta=637.5,707.5
XS Rating Curve= 0 ,0
Exp/Cntr=0.3,0.1

Type RM Length L Ch R = 1 ,65223.4 ,670.2,684.3,698.9
XS GIS Cut Line= 3
     1828287.892       313603.75      1828930.99      313649.357
     1829350.378      313670.389
#Sta/Elev= 30
       0 1268.41   109.1 1254.46   158.7 1252.85     238 1247.02   297.6 1233.18
   317.4 1230.92   327.3  1228.1   376.9  1202.4   386.8 1202.41   406.7 1190.84
   416.6  1176.8   426.5 1169.86   446.3 1157.94   456.3 1154.14   555.4 1143.94
   587.1 1135.72     615 1133.21   657.1 1134.06   684.7  1135.5   714.7  1140.5
   784.7 1157.45   794.7 1162.84   814.7    1188   844.7 1216.66   864.7 1231.13
   894.7  1247.5   924.7 1253.63  1004.6  1261.8  1034.6 1263.48  1064.6 1262.06
#Mann= 3 , 0 , 0
       0      .1       0   587.1    .045       0   657.1      .1       0
Bank Sta=587.1,657.1
XS Rating Curve= 0 ,0
Exp/Cntr=0.3,0.1

Type RM Length L Ch R = 1 ,64539.1 ,783.1,835.6,888.1
XS GIS Cut Line= 2
     1827985.308      314032.711     1829128.051      314445.165
#Sta/Elev= 30
       0 1327.05    49.8 1324.01    69.7 1325.46    89.6 1319.94   109.5 1319.57
   129.5 1311.01   159.3  1290.3   199.2 1270.48   328.6 1230.32   358.5 1218.94
   378.4 1207.61   398.3 1200.91   418.2 1195.44   438.2 1193.74     478 1173.78
   537.7 1149.82   617.4 1138.62   637.3  1128.7   657.2 1126.01   685.1 1126.53
   755.1 1128.71   786.7 1136.82   866.4 1171.42   886.3  1182.9     956 1205.92
   965.9 1211.15  1035.6    1231  1075.5 1237.37  1135.2 1256.48  1214.9 1277.16
#Mann= 3 , 0 , 0
       0      .1       0   685.1    .045       0   755.1      .1       0
Bank Sta=685.1,755.1
XS Rating Curve= 0 ,0
Exp/Cntr=0.3,0.1