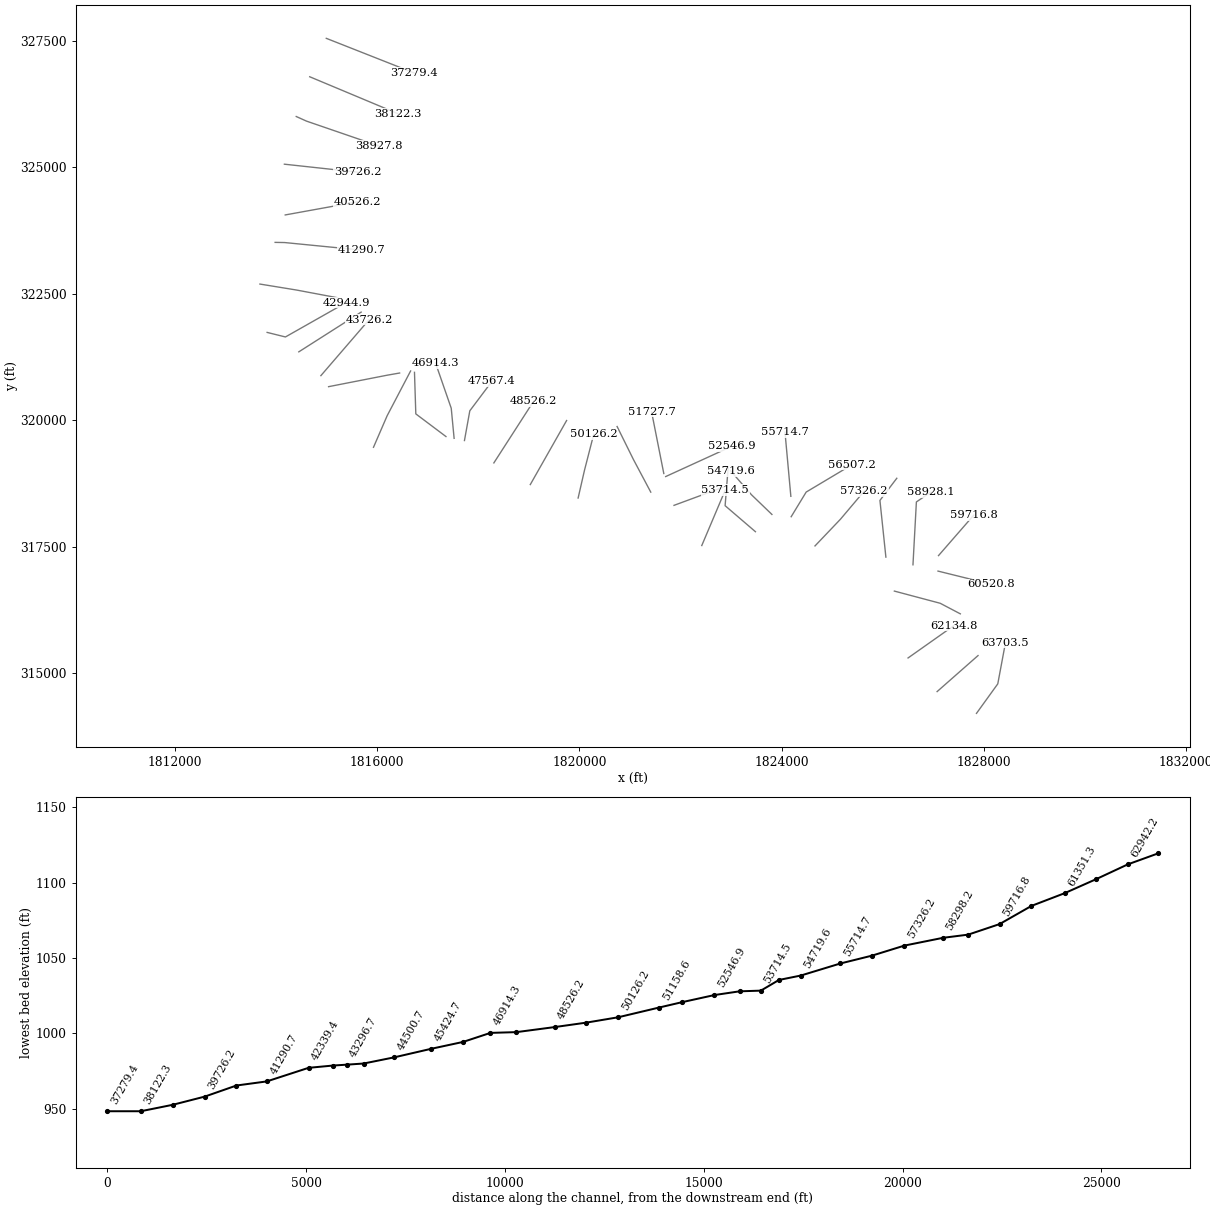
HEC-RAS study MrshFrk1.prj: MrshFrk1

--- MrshFrk1.g01 (geometry) --- (continued)

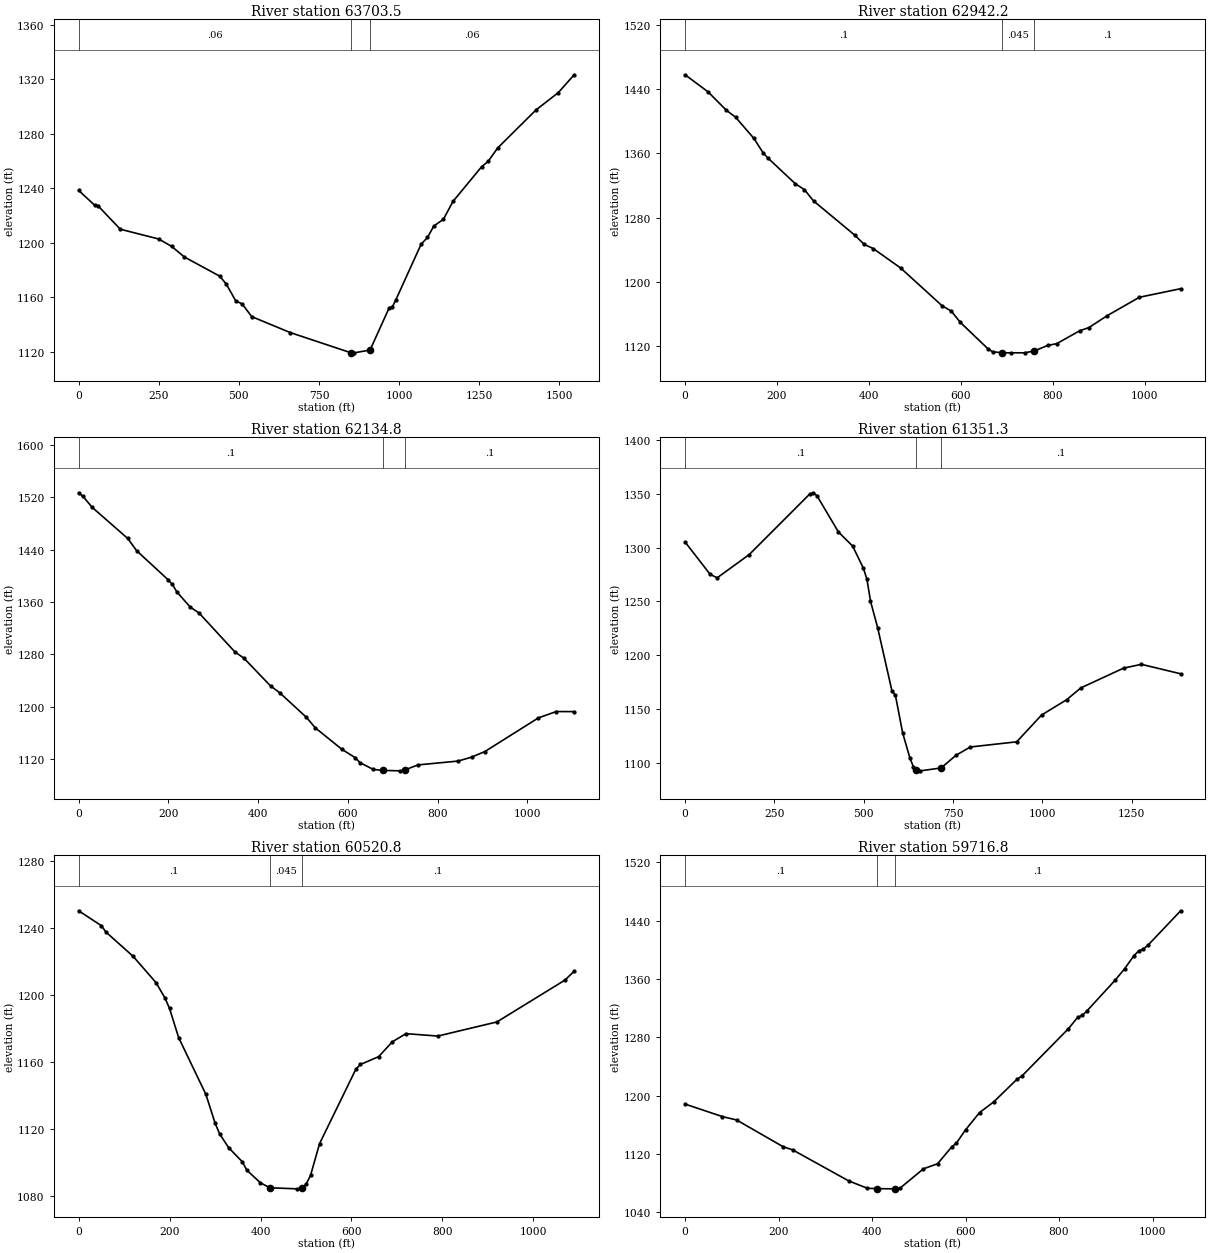
Type RM Length L Ch R = 1 ,63703.5 ,794.9,761.3,727.7
XS GIS Cut Line= 3
     1827854.346      314201.292     1828275.798      314785.393
     1828427.384      315597.223
#Sta/Elev= 30
       0 1238.46      50 1227.59      60 1227.28     130 1209.98   250.1  1202.8
   290.1 1197.42   330.1 1189.58   440.2 1175.55   460.2 1169.88   490.2 1157.44
   510.2 1155.17   540.2 1145.86   660.2 1134.18   849.6 1119.37   859.6 1119.31
   909.3 1121.36     969 1152.39     979 1153.05   988.9 1157.76  1068.5 1198.97
  1088.4 1203.93  1108.3 1212.35  1138.2  1217.3    1168 1230.36  1257.6  1255.9
  1277.5 1259.67  1307.3 1269.54  1426.7 1297.41  1496.4 1310.15  1546.1 1323.27
#Mann= 3 , 0 , 0
       0     .06       0   849.6    .045       0   909.3     .06       0
Bank Sta=849.6,909.3
XS Rating Curve= 0 ,0
Exp/Cntr=0.3,0.1

Type RM Length L Ch R = 1 ,62942.2 ,812.8,807.4,802
XS GIS Cut Line= 2
     1827075.778      314632.076     1827885.041      315344.579
#Sta/Elev= 30
       0  1457.7    49.9 1436.51    89.8 1413.59   109.8 1404.96   149.8 1378.55
   169.7 1360.69   179.7 1354.47   239.6 1322.36   259.6 1314.92   279.5 1300.85
   369.4 1258.25   389.4 1246.94   409.3  1241.7   469.2 1217.38   559.1 1170.58
     579 1163.94     599 1149.83   658.9 1117.08   668.9 1113.44   689.8  1112.1
   708.8 1112.03   738.8 1112.08   759.8 1114.38   788.7 1121.18   808.7 1123.47
   858.6 1139.46   878.6 1143.43   918.5 1158.28   988.4 1181.11  1078.2 1191.77
#Mann= 3 , 0 , 0
       0      .1       0   689.8    .045       0   759.8      .1       0
Bank Sta=689.8,759.8
XS Rating Curve= 0 ,0
Exp/Cntr=0.3,0.1

Type RM Length L Ch R = 1 ,62134.8 ,827.4,783.4,739.5
XS GIS Cut Line= 2
     1826501.095      315297.325     1827403.333      315934.082
#Sta/Elev= 30
       0 1526.96      10 1521.34    29.8 1504.91   109.4 1457.19   129.3 1438.41
     199 1394.31   208.9 1387.02   218.9 1375.46   248.7 1352.33   268.6 1343.11
   348.2 1283.82   368.1  1274.4   427.8 1231.74   447.7 1221.64   507.4 1183.97
   527.3 1167.83     587 1134.82   616.8    1122   626.8 1114.75   656.6 1104.22
     679  1102.7   716.3 1102.08   726.3  1103.3   756.1 1111.13   845.6 1117.01
   875.5 1122.99   905.3 1131.56  1024.7 1183.05  1064.5  1192.7  1104.3 1192.56
#Mann= 3 , 0 , 0
       0      .1       0     679    .045       0   726.3      .1       0
Bank Sta=679,726.3
XS Rating Curve= 0 ,0
Exp/Cntr=0.3,0.1

Type RM Length L Ch R = 1 ,61351.3 ,830.2,830.5,830.9
XS GIS Cut Line= 3
     1826230.282      316619.898     1827137.214      316378.736
     1827534.708      316169.883
#Sta/Elev= 30
       0 1305.12    69.9 1275.19    89.8 1271.91   179.7 1293.52   349.4 1349.77
   359.4 1350.79   369.4 1347.97   429.3 1314.43   469.2 1301.32   499.2 1280.81
   509.2 1270.51   519.1 1250.37   539.1 1225.68     579 1167.25     589 1162.81
     609 1128.27     629 1105.24   638.9 1096.89   646.8 1094.07   658.9 1092.88
   716.8 1095.55   758.8 1107.37   798.7 1115.01   928.5  1119.8   998.3 1144.69
  1068.2 1158.82  1108.1 1169.81  1227.8 1188.15  1277.7 1191.68  1387.5  1182.9
#Mann= 3 , 0 , 0
       0      .1       0   646.8    .045       0   716.8      .1       0
Bank Sta=646.8,716.8
XS Rating Curve= 0 ,0
Exp/Cntr=0.3,0.1

Type RM Length L Ch R = 1 ,60520.8 ,748.8,803.9,859.1
XS GIS Cut Line= 2
     1827093.423      317015.399     1828151.182      316753.506
#Sta/Elev= 30
       0 1250.32      50 1241.44      60 1237.64     120  1223.1     170 1207.53
     190 1198.23   199.9 1192.06   219.9  1174.7   279.9 1140.79   299.9  1123.8
   309.9 1117.34   329.9 1109.01   359.9 1100.64   369.9 1095.58   399.9 1088.05
   420.7 1085.12   479.9 1084.48   490.7 1084.92   499.9 1087.15   509.9 1092.44
   529.8 1111.42   609.8 1155.93   619.8 1158.66   659.8 1163.32   689.8 1172.16
   719.8 1177.04   789.8  1175.6   919.8 1184.02  1069.7 1209.03  1089.7 1214.31
#Mann= 3 , 0 , 0
       0      .1       0   420.7    .045       0   490.7      .1       0
Bank Sta=420.7,490.7
XS Rating Curve= 0 ,0
Exp/Cntr=0.3,0.1

Type RM Length L Ch R = 1 ,59716.8 ,755.5,788.7,821.9
XS GIS Cut Line= 2
     1827103.528      317321.941     1827799.764      318121.327
#Sta/Elev= 30
       0 1188.55      80  1171.4     110 1166.84     210 1130.02     230 1125.84
     350 1083.27     390 1073.16   410.4 1072.64     450 1072.39     460 1073.44
     510 1099.89     540 1106.74     570 1129.61     580 1134.79     600 1153.32
     630 1176.97     660 1191.45     710 1222.61     720 1226.69   820.1 1291.96
   840.1 1307.73   850.1 1310.32   860.1 1316.61   920.1 1358.48   940.1 1373.95
   960.1 1391.92   970.1 1398.31   980.1 1400.96   990.1 1406.24  1060.1 1453.56
#Mann= 3 , 0 , 0
       0      .1       0   410.4    .045       0     450      .1       0
Bank Sta=410.4,450
XS Rating Curve= 0 ,0
Exp/Cntr=0.3,0.1

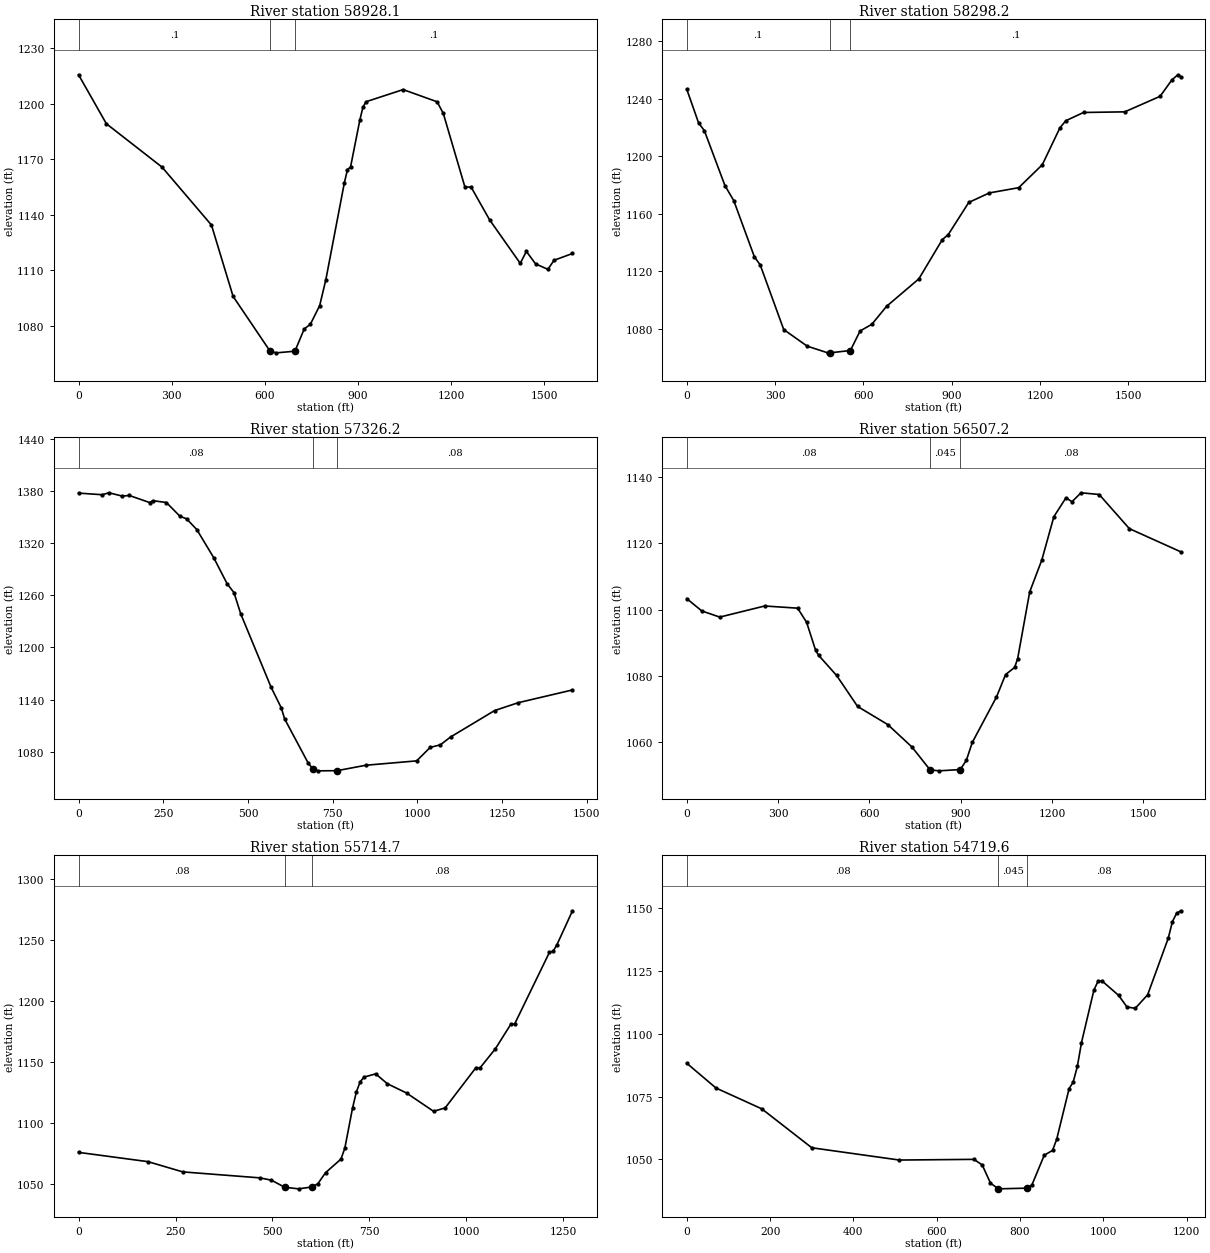
Type RM Length L Ch R = 1 ,58928.1 ,621.9,629.9,637.9
XS GIS Cut Line= 3
      1826598.24      317140.037     1826665.833      318383.035
     1826951.942      318578.425
#Sta/Elev= 30
       0 1215.56    89.6 1189.13   268.9  1165.7   428.2 1134.41   497.9 1095.89
   617.4 1066.21   637.4  1065.4   697.1 1066.28     727 1078.28   746.9 1080.85
   776.8 1090.88   796.7 1104.88   856.4 1157.27   866.4 1164.33   876.4 1165.82
   906.2  1191.1   916.2 1198.05   926.2 1201.01  1045.7 1207.56  1155.2 1200.98
  1175.1 1194.68  1244.8 1154.93  1264.6 1154.94    1324  1137.3    1423 1113.72
  1442.8 1120.18  1472.5 1113.42  1512.1 1110.49  1531.9 1115.38  1591.3 1119.05
#Mann= 3 , 0 , 0
       0      .1       0   617.4    .045       0   697.1      .1       0
Bank Sta=617.4,697.1
XS Rating Curve= 0 ,0
Exp/Cntr=0.3,0.1

Type RM Length L Ch R = 1 ,58298.2 ,1016.7,971.9,927.5
XS GIS Cut Line= 3
     1826062.634      317291.624     1825944.734      318413.364
     1826278.224      318851.281
#Sta/Elev= 30
       0 1246.47    39.9 1223.22    59.9 1217.65   129.8  1179.5   159.7 1169.08
   229.6 1130.08   249.5 1124.42   329.4 1079.48   409.2 1067.95   479.1  1063.3
   485.9  1063.3   555.9 1064.92   588.9  1078.5   628.8 1083.14   678.8 1095.62
   788.6 1114.73   868.4 1142.05   888.4 1145.47   958.2 1167.86  1028.1 1174.46
  1127.9 1178.11    1208 1194.04    1268 1219.74    1288 1224.66  1348.1 1230.38
  1488.2 1230.82  1608.3 1241.62  1648.3 1252.98  1668.4 1256.59  1678.4 1255.26
#Mann= 3 , 0 , 0
       0      .1       0   485.9    .045       0   555.9      .1       0
Bank Sta=485.9,555.9
XS Rating Curve= 0 ,0
Exp/Cntr=0.3,0.1

Type RM Length L Ch R = 1 ,57326.2 ,832.6,819,802.5
XS GIS Cut Line= 3
      1824660.53      317513.049     1825162.614      318039.828
      1825633.77      318596.843
#Sta/Elev= 30
       0 1377.38    69.8 1375.53    89.7 1377.76   129.6 1373.89   149.5 1374.69
   209.4 1366.58   219.3 1368.69   259.2 1366.56   299.1 1350.81     319 1347.75
   348.9 1335.47   398.8 1303.16   438.6    1273   458.6 1263.01   478.5  1238.6
   568.2 1154.12   598.1 1130.57   608.1 1117.76   677.9 1066.82   692.7 1059.78
   707.8 1058.14   762.7 1058.33   847.6 1064.57   997.6  1069.6  1037.5 1085.08
  1067.5 1088.03  1097.5    1097  1227.4  1127.4  1297.4 1136.49  1457.3 1151.12
#Mann= 3 , 0 , 0
       0     .08       0   692.7    .045       0   762.7     .08       0
Bank Sta=692.7,762.7
XS Rating Curve= 0 ,0
Exp/Cntr=0.3,0.1

Type RM Length L Ch R = 1 ,56507.2 ,735.6,792.5,849.3
XS GIS Cut Line= 3
     1824189.416      318090.758     1824486.134      318578.425
     1825388.916      319117.399
#Sta/Elev= 30
       0 1103.36    49.2 1099.66   108.3  1097.8   255.9 1101.15   364.2 1100.49
   393.7 1096.19   423.2 1087.76     433 1086.27   492.1  1080.2     561 1070.86
   660.1  1065.4   739.5 1058.64     799 1051.75   828.7 1051.45   898.2 1051.84
     918 1054.57   937.8 1060.03  1017.2 1073.71    1047 1080.47  1076.7 1082.62
  1086.6 1085.23  1126.3  1105.4    1166 1114.99  1205.7 1128.08  1245.4 1133.76
  1265.2 1132.58  1294.9 1135.28  1354.5 1134.76  1453.6 1124.47  1622.3 1117.49
#Mann= 3 , 0 , 0
       0     .08       0     799    .045       0   898.2     .08       0
Bank Sta=799,898.2
XS Rating Curve= 0 ,0
Exp/Cntr=0.3,0.1

Type RM Length L Ch R = 1 ,55714.7 ,963.9,995.1,1026.4
XS GIS Cut Line= 2
     1824182.961       318494.21     1824066.973      319762.362
#Sta/Elev= 30
       0 1076.17   179.1 1068.55   268.6 1060.16   467.6 1055.26   497.4 1053.33
   531.1  1047.6   567.1 1046.26   601.1 1047.75   616.8 1050.41   636.7 1059.48
   676.5 1070.65   686.5  1079.6   706.4 1112.56   716.3 1125.81   726.3 1134.19
   736.2 1137.92   766.1 1140.56   795.9 1132.49   845.6 1124.86   915.3 1109.83
   945.1 1112.62  1024.7 1145.72  1034.7 1145.32  1074.5 1161.07  1114.3 1181.17
  1124.2 1181.39  1213.8 1240.09  1223.7 1241.17  1233.6 1246.64  1273.4  1274.3
#Mann= 3 , 0 , 0
       0     .08       0   531.1    .045       0   601.1     .08       0
Bank Sta=531.1,601.1
XS Rating Curve= 0 ,0
Exp/Cntr=0.3,0.1

Type RM Length L Ch R = 1 ,54719.6 ,543.3,550.3,557.3
XS GIS Cut Line= 3
     1823808.483      318135.735     1823404.817      318524.527
     1822993.849       318996.13
#Sta/Elev= 30
       0 1088.23    70.1 1078.38   180.2 1070.08   300.2  1054.6   510.4 1049.72
   689.5 1049.99   709.4 1047.76   729.2 1040.53   747.8  1038.3   749.1 1038.26
   817.8 1038.54   828.5 1039.73   858.3 1051.64   878.2 1053.55   888.1 1057.92
   917.9  1078.1   927.8 1080.76   937.8 1086.97   947.7 1096.43   977.5 1117.31
   987.4 1120.88   997.3 1120.96  1037.1 1115.21  1056.9 1110.64  1076.8 1110.08
  1106.6 1115.48  1156.2 1138.05  1166.1 1144.62  1176.1  1147.9    1186 1148.91
#Mann= 3 , 0 , 0
       0     .08       0   747.8    .045       0   817.8     .08       0
Bank Sta=747.8,817.8
XS Rating Curve= 0 ,0
Exp/Cntr=0.3,0.1

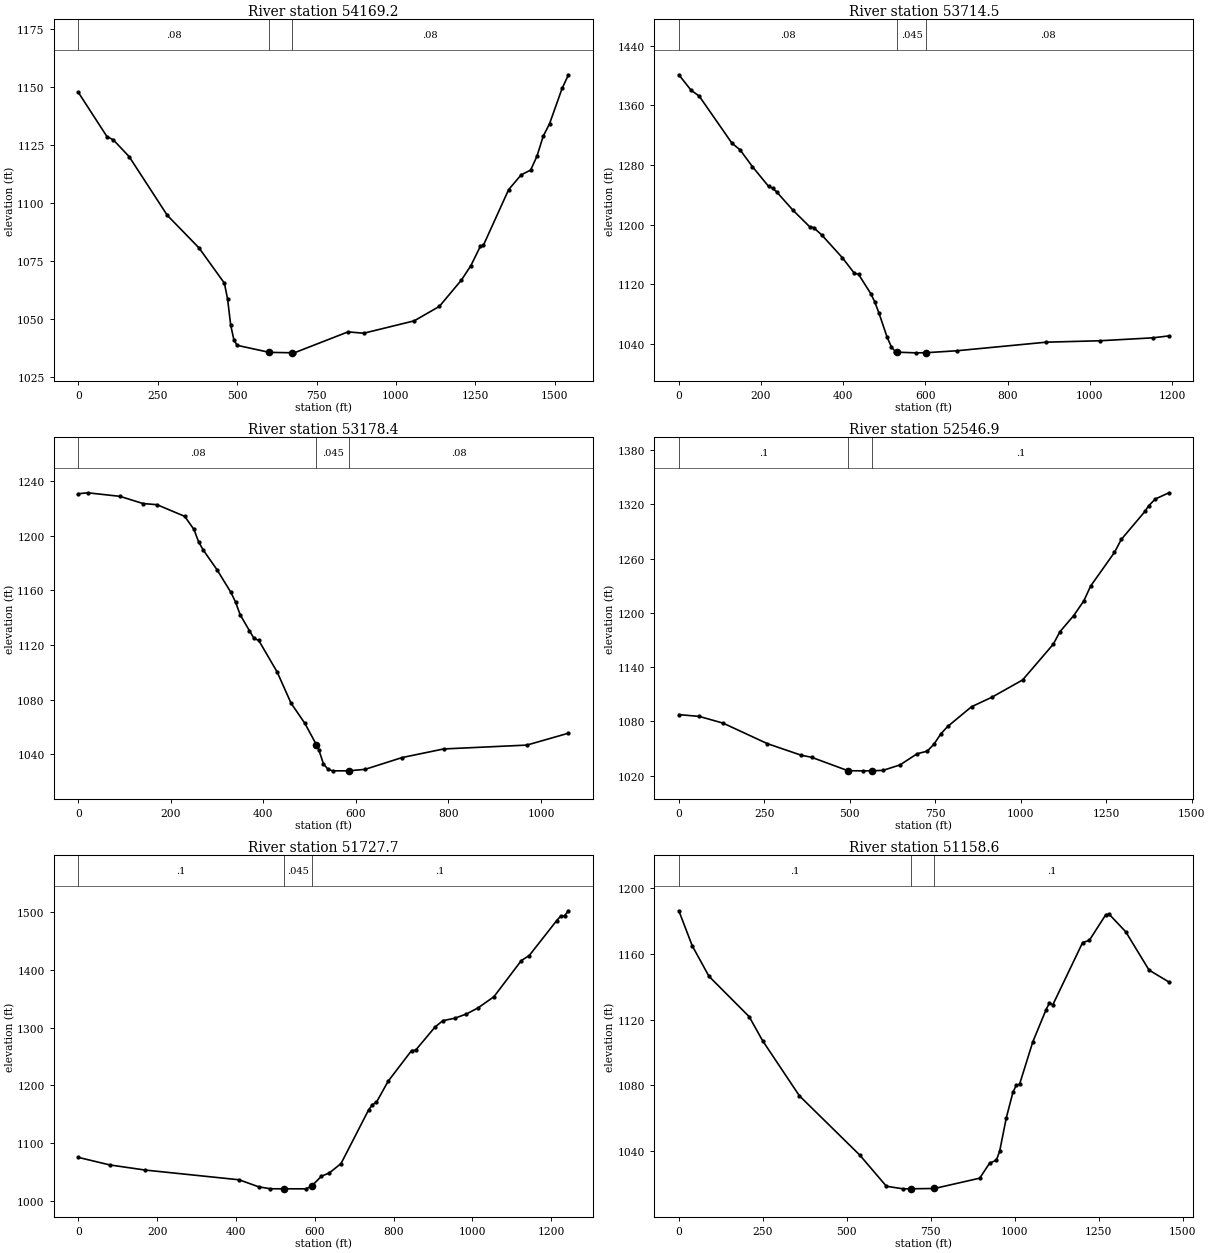
Type RM Length L Ch R = 1 ,54169.2 ,518.1,454.7,391.4
XS GIS Cut Line= 3
     1823482.162      317794.853     1822882.686      318308.938
      1822943.32      319060.133
#Sta/Elev= 30
       0 1147.62      90 1128.58     110 1127.17   159.9 1119.94   279.9 1094.65
   379.9 1080.57   459.8 1065.38   469.8 1058.67   479.8 1047.24   489.8 1040.94
   499.8 1038.57   601.5 1035.52   671.5 1035.35   679.8 1035.32   849.2 1044.36
   898.8 1043.78  1057.5 1049.11  1136.8 1055.34  1206.2 1066.68    1236 1072.89
  1265.7 1081.18  1275.6 1081.71    1355 1105.69  1394.6 1112.09  1424.4 1114.13
  1444.2 1120.13    1464 1128.76  1483.9 1134.12  1523.5 1149.37  1543.4 1155.22
#Mann= 3 , 0 , 0
       0     .08       0   601.5    .045       0   671.5     .08       0
Bank Sta=601.5,671.5
XS Rating Curve= 0 ,0
Exp/Cntr=0.3,0.1

Type RM Length L Ch R = 1 ,53714.5 ,577.6,536,494.5
XS GIS Cut Line= 2
     1822421.189      317520.688     1822886.054      318618.848
#Sta/Elev= 30
       0 1400.84    29.8 1380.12    49.7 1372.19   129.2 1309.18   149.1 1300.19
   178.9 1277.86   218.6 1251.14   228.6 1248.86   238.5 1243.61   278.2 1219.07
     318 1197.43   327.9 1196.09   347.8 1186.16   397.5 1155.96   427.3 1134.72
   437.2 1133.52   467.1 1107.53     477 1096.16   486.9 1081.55   506.8 1049.18
   516.8 1036.73   526.7 1029.77   531.2 1029.11   576.4 1028.24   601.2  1028.4
   675.8 1030.99   894.4 1042.55  1023.6  1044.4  1152.8 1048.34  1192.5 1050.93
#Mann= 3 , 0 , 0
       0     .08       0   531.2    .045       0   601.2     .08       0
Bank Sta=531.2,601.2
XS Rating Curve= 0 ,0
Exp/Cntr=0.3,0.1

Type RM Length L Ch R = 1 ,53178.4 ,627.8,631.6,635.4
XS GIS Cut Line= 2
     1821872.108      318315.675     1822865.843      318682.851
#Sta/Elev= 30
       0 1230.88      20  1231.6      90 1228.98   139.9  1223.7   169.9 1222.88
   229.9 1214.33   249.9 1204.72   259.8 1195.76   269.8 1189.69   299.8 1175.16
   329.8 1158.56   339.8 1151.45   349.8 1142.18   369.8 1130.49   379.8 1124.79
   389.8 1123.45   429.8 1100.18   459.7 1077.42   489.7 1062.54   514.6  1046.9
   519.7 1043.35   529.7 1032.94   539.7 1028.88   549.7 1027.78   584.6  1027.8
   619.6 1028.86   699.6  1037.5   789.6 1043.82   969.4 1046.65  1059.4 1055.37
#Mann= 3 , 0 , 0
       0     .08       0   514.6    .045       0   584.6     .08       0
Bank Sta=514.6,584.6
XS Rating Curve= 0 ,0
Exp/Cntr=0.3,0.1

Type RM Length L Ch R = 1 ,52546.9 ,752,819.2,886.4
XS GIS Cut Line= 2
     1821707.048      318884.967     1823010.692      319481.207
#Sta/Elev= 30
       0 1087.51    59.7 1085.53   129.4 1078.09   258.8  1055.4   358.4 1042.53
   388.2 1040.33   494.8 1025.43   537.6 1025.31   564.8 1025.33   597.3 1025.83
   647.1  1031.9   696.8 1044.18   726.7 1047.11   746.6 1054.99   766.5 1066.33
   786.4 1074.42   856.1 1096.22   915.9  1106.8  1005.5 1125.86    1095  1165.3
    1115 1179.38  1154.8 1196.98  1184.6 1213.36  1204.6 1229.82  1274.2 1266.97
  1294.2 1281.35  1363.8 1312.52  1373.8  1318.4  1393.7 1326.06  1433.5 1332.94
#Mann= 3 , 0 , 0
       0      .1       0   494.8    .045       0   564.8      .1       0
Bank Sta=494.8,564.8
XS Rating Curve= 0 ,0
Exp/Cntr=0.3,0.1

Type RM Length L Ch R = 1 ,51727.7 ,554.6,569,582
XS GIS Cut Line= 2
     1821669.993      318945.601     1821428.155      320165.723
#Sta/Elev= 30
       0 1075.07    79.6 1062.05   169.2 1053.16     408 1036.26   457.7 1024.04
   487.6 1020.66     522 1020.61   577.2 1020.55     592 1025.11     617 1042.54
   636.9 1048.03   666.7 1064.45   736.4 1157.09   746.3 1166.56   756.3 1170.38
   786.1 1207.06   845.8 1260.46   855.8 1260.89   905.5  1301.4   925.4  1312.3
   955.3 1316.45   985.1 1323.86    1015 1334.67  1054.8 1353.84  1124.4 1416.57
  1144.4 1425.24    1214  1485.8    1224 1493.39  1233.9 1494.15  1243.9 1502.86
#Mann= 3 , 0 , 0
       0      .1       0     522    .045       0     592      .1       0
Bank Sta=522,592
XS Rating Curve= 0 ,0
Exp/Cntr=0.3,0.1

Type RM Length L Ch R = 1 ,51158.6 ,1068,1032.4,997
XS GIS Cut Line= 3
     1821412.312      318577.116     1821070.882      319219.469
     1820746.623      319874.706
#Sta/Elev= 30
       0 1186.25    39.9 1164.94    89.7 1146.38   209.3 1121.82   249.1 1107.25
   358.8 1073.65   538.1 1037.66   617.8 1018.61   667.7 1017.04   690.6 1017.08
   760.6 1017.25   895.4 1023.53     925  1032.7   944.8 1034.41   954.7 1039.88
   974.4 1060.15   994.2 1075.75  1004.1 1080.11    1014 1080.68  1053.5 1106.55
    1093 1126.13  1102.9 1130.19  1112.8 1128.97  1201.7 1166.93  1221.4 1168.19
  1270.8 1183.94  1280.7 1184.13  1330.1 1173.44  1399.3 1150.16  1458.5 1142.91
#Mann= 3 , 0 , 0
       0      .1       0   690.6    .045       0   760.6      .1       0
Bank Sta=690.6,760.6
XS Rating Curve= 0 ,0
Exp/Cntr=0.3,0.1

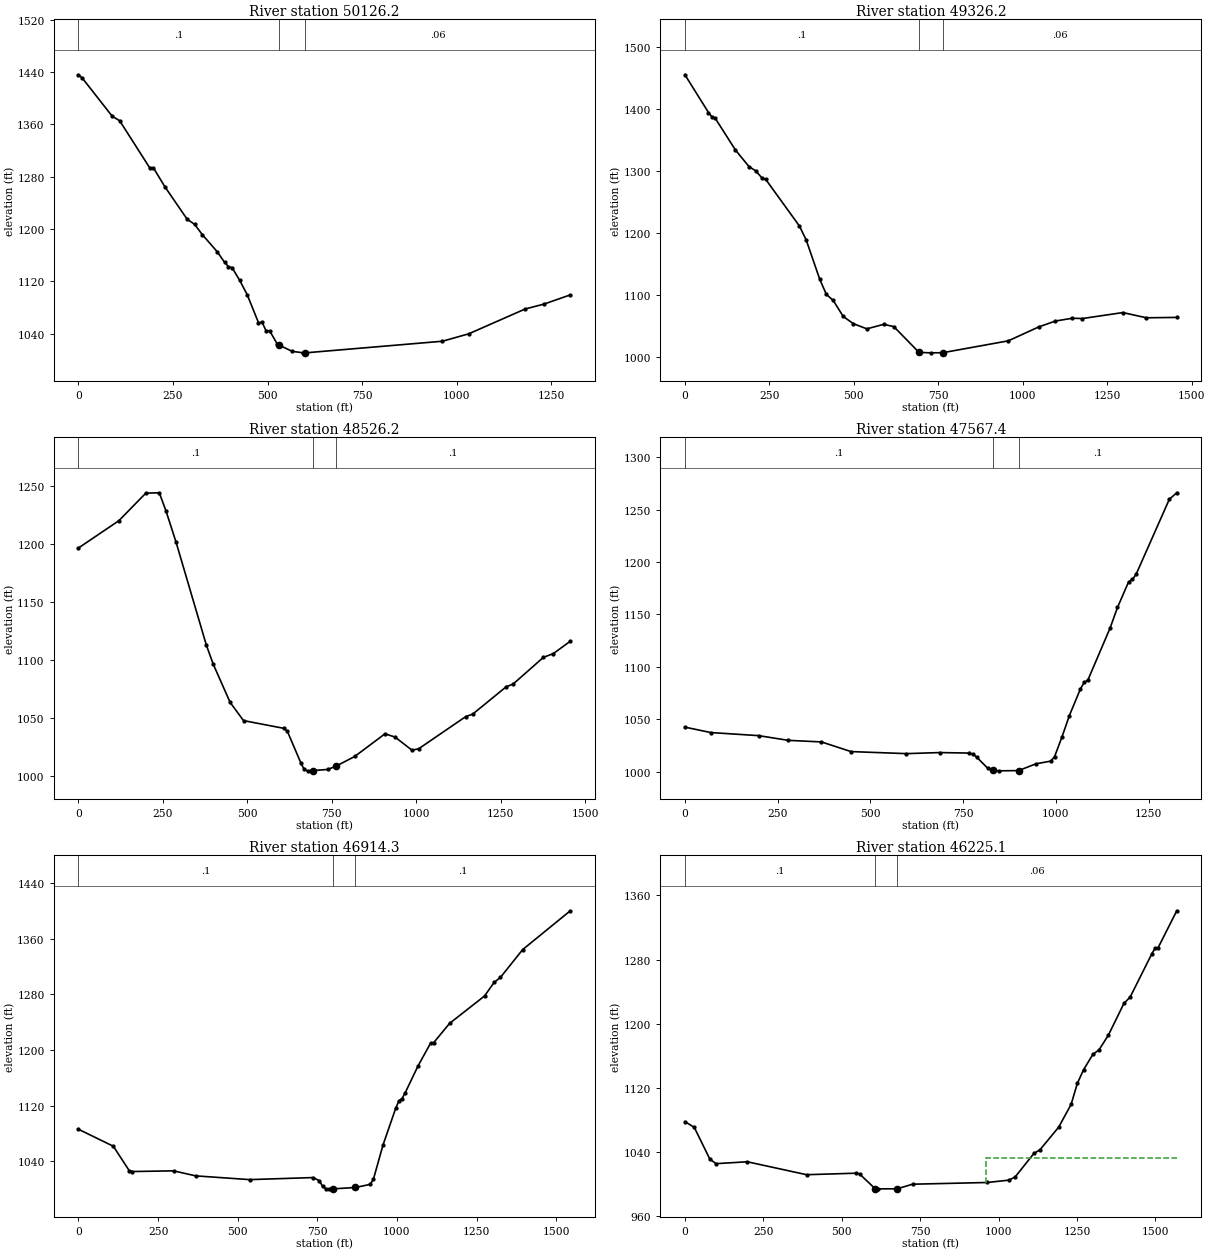
Type RM Length L Ch R = 1 ,50126.2 ,814.7,800,786.6
XS GIS Cut Line= 3
     1819975.593      318460.524     1820101.761       319011.18
     1820284.698      319723.103
#Sta/Elev= 30
       0 1435.91     9.9 1431.02    89.2 1372.58     109 1365.56   188.3 1293.66
   198.2 1293.55     228 1264.99   287.4  1214.9   307.2 1207.02   327.1 1191.58
   366.7  1165.3   386.5 1148.76   396.4 1142.61   406.4 1140.58   426.2 1121.43
     446  1099.6   475.7 1056.88   485.6 1057.01   495.6  1044.7   505.5 1044.03
   525.3 1024.37   529.9 1022.48   564.9 1012.85   594.7 1010.56   599.9 1010.56
   962.2 1028.32  1031.8 1039.72  1180.8 1077.65  1230.4 1085.11    1300 1099.21
#Mann= 3 , 0 , 0
       0      .1       0   529.9    .045       0   599.9     .06       0
Bank Sta=529.9,599.9
XS Rating Curve= 0 ,0
Exp/Cntr=0.3,0.1

Type RM Length L Ch R = 1 ,49326.2 ,802.9,800,797.1
XS GIS Cut Line= 3
     1819029.496      318726.624     1819388.585      319359.901
     1819747.674      319993.178
#Sta/Elev= 30
       0 1455.07    69.8 1394.25    79.8  1387.3    89.8 1384.94   149.6 1333.83
   189.5 1307.25   209.4 1300.33   229.4 1288.04   239.3 1286.45   339.1 1211.28
     359 1188.93   398.9  1125.9   418.8 1101.07   438.8  1091.6   468.7 1065.61
   498.6 1054.01   538.5 1045.68   588.4 1052.93   618.3 1049.28     693 1007.72
     728 1007.01     763  1007.2   957.4 1026.36  1047.1 1048.73    1097 1058.28
  1146.8 1062.78  1176.8  1062.3  1296.4  1071.9  1366.2 1063.48    1456  1064.1
#Mann= 3 , 0 , 0
       0      .1       0     693    .045       0     763     .06       0
Bank Sta=693,763
XS Rating Curve= 0 ,0
Exp/Cntr=0.3,0.1

Type RM Length L Ch R = 1 ,48526.2 ,962.4,958.9,955.3
XS GIS Cut Line= 3
     1818309.028       319154.88     1818703.207      319766.932
     1819097.385      320378.983
#Sta/Elev= 30
       0 1196.52   119.7 1220.11   199.4 1243.91   239.3 1244.22   259.3 1228.42
   289.2 1201.29     379 1112.31   398.9 1096.22   448.8 1063.27   488.7 1047.43
   608.3 1040.74   618.3 1038.32   658.2 1010.97   668.2 1005.27   678.1 1004.04
     693  1004.3     738 1005.21     763 1008.17   817.8 1016.44   907.5 1036.04
   937.4 1033.18   987.3 1021.89  1007.2 1023.11  1146.8 1050.96  1166.8 1052.95
  1266.5 1076.72  1286.5 1078.93  1376.2 1102.02  1406.1 1105.36    1456 1116.01
#Mann= 3 , 0 , 0
       0      .1       0     693    .045       0     763      .1       0
Bank Sta=693,763
XS Rating Curve= 0 ,0
Exp/Cntr=0.3,0.1

Type RM Length L Ch R = 1 ,47567.4 ,603.7,653.1,702.5
XS GIS Cut Line= 3
     1817727.427      319597.644     1817833.169      320185.242
     1818271.086      320768.008
#Sta/Elev= 30
       0  1042.4    69.6 1037.24     199 1034.27   278.6  1029.8   368.2 1028.27
   447.8 1019.07     597 1017.12   686.9 1018.13   766.8 1017.65   776.8 1016.42
   786.8 1013.71   816.7 1003.03   829.5 1001.18   846.7  1000.7   899.5 1000.94
   946.5  1007.4   986.5 1009.99   996.5  1014.2  1016.4 1032.88  1036.4 1053.35
  1066.4 1078.96  1076.4    1085  1086.3 1087.26  1146.3 1136.96  1166.2 1156.56
  1196.2 1181.03  1206.2 1183.28  1216.2 1188.04    1306 1259.83    1326 1265.98
#Mann= 3 , 0 , 0
       0      .1       0   829.5    .045       0   899.5      .1       0
Bank Sta=829.5,899.5
XS Rating Curve= 0 ,0
Exp/Cntr=0.3,0.1

Type RM Length L Ch R = 1 ,46914.3 ,659.5,689.1,718.8
XS GIS Cut Line= 3
     1817522.893      319641.327     1817465.993      320235.771
     1817155.465      321130.678
#Sta/Elev= 30
       0 1085.92   109.5 1061.49   159.2 1026.55   169.2  1025.1   298.6 1026.09
   368.2 1018.86   537.4 1013.47   736.8 1016.42   756.7 1011.82   766.7 1003.62
   776.6 1000.22   786.6  1000.2   799.7  1000.2   869.7 1002.14   916.2 1006.63
   926.2 1014.01   956.1 1062.94     996 1115.89    1006  1126.6    1016 1130.01
  1025.9 1138.31  1065.8 1176.57  1105.7 1209.77  1115.7 1210.64  1165.5 1238.28
  1275.2 1277.66  1305.1 1297.15    1325 1304.34  1394.8 1344.38  1544.4 1400.22
#Mann= 3 , 0 , 0
       0      .1       0   799.7    .045       0   869.7      .1       0
Bank Sta=799.7,869.7
XS Rating Curve= 0 ,0
Exp/Cntr=0.3,0.1

Type RM Length L Ch R = 1 ,46225.1 ,868.1,800.4,731.6
XS GIS Cut Line= 3
     1817361.567      319676.585     1816765.326      320124.608
     1816739.049      320946.502
#Sta/Elev= 30
       0 1077.96    29.8 1070.87    79.6 1031.16    99.4  1025.6   198.9 1027.93
   387.8 1011.82   546.9 1013.71   556.9 1012.74   606.6   994.3   616.5  994.19
   676.2   994.2   725.9  999.97   963.8  1002.1  1033.1 1005.04  1052.9 1009.04
  1112.4 1038.25  1132.2 1042.97  1191.6 1071.06  1231.3  1099.5  1251.1 1125.62
  1270.9 1142.64  1300.6 1161.77  1320.4 1167.52  1350.2 1185.87  1399.7 1225.41
  1419.5 1233.27  1488.9 1287.45  1498.8 1294.01  1508.7 1294.84  1568.1 1340.85
#Mann= 3 , 0 , 0
       0      .1       0   606.6    .045       0   676.2     .06       0
#XS Ineff= 2 , 0
                          960.54         1032.69
Permanent Ineff=
       F       F
Bank Sta=606.6,676.2
XS Rating Curve= 0 ,0
Exp/Cntr=0.3,0.1

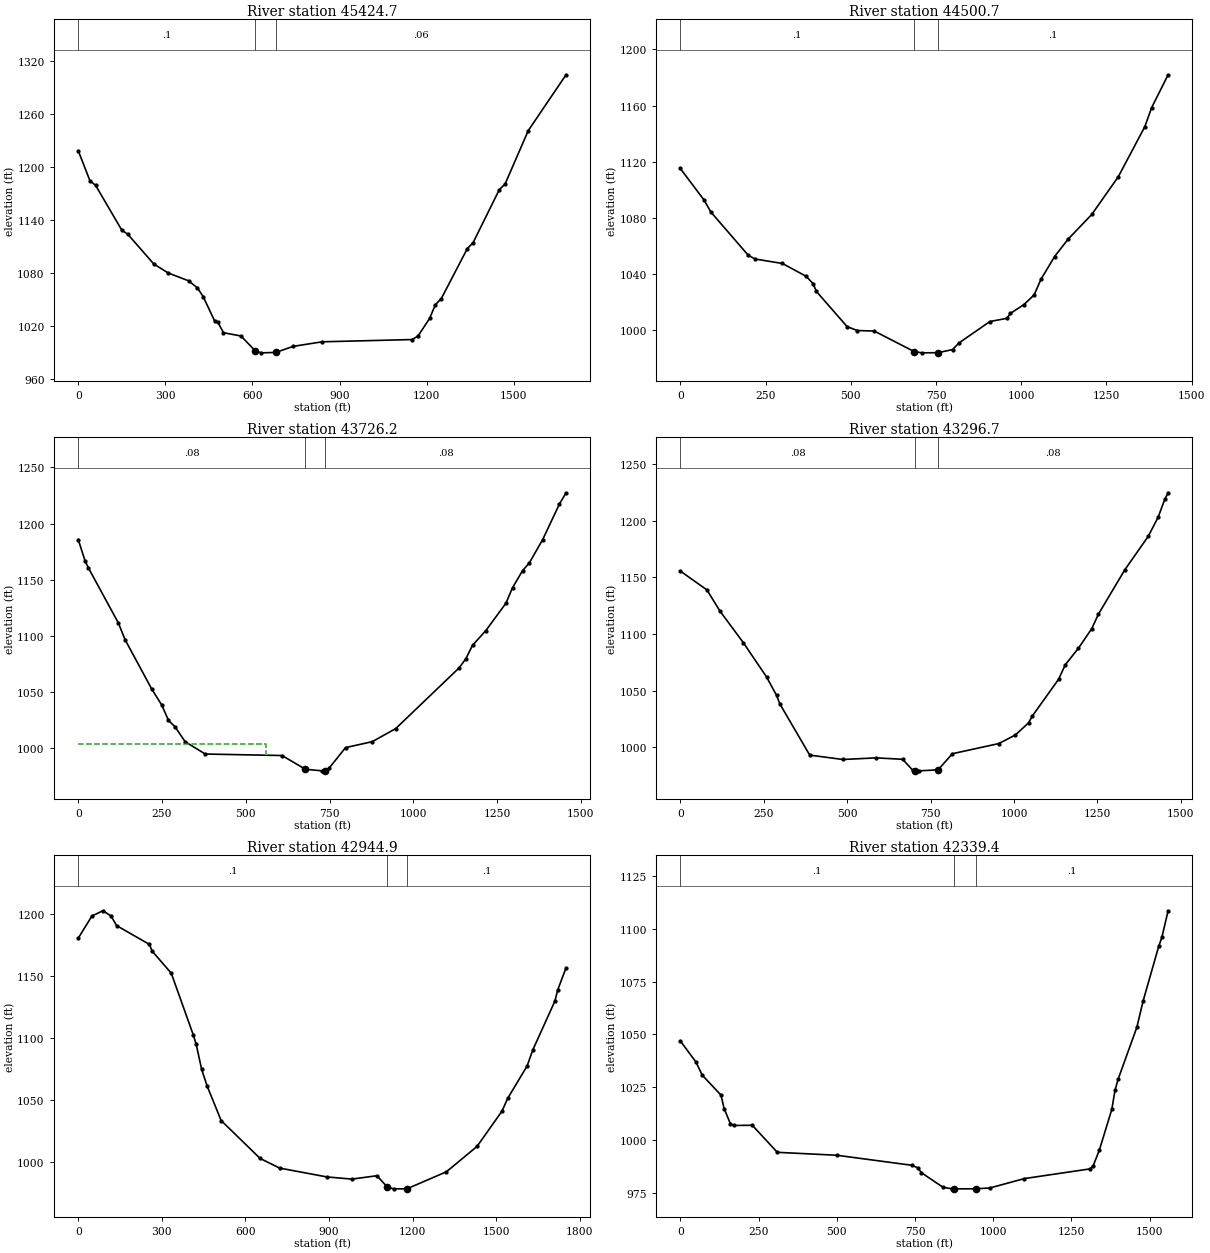
Type RM Length L Ch R = 1 ,45424.7 ,973.1,924.1,876.1
XS GIS Cut Line= 3
     1815928.353      319464.078     1816198.503      320088.218
     1816662.329      320973.524
#Sta/Elev= 30
       0 1218.39      40  1184.6      60 1179.06     150 1128.45     170 1124.08
     260 1090.25     310 1079.96     380 1071.16   410.1 1063.21   430.1 1053.34
   470.1 1025.38   480.1 1024.64   500.1 1012.41   560.1 1008.72   609.8  991.87
   630.1  989.64   679.8  990.08   740.1  996.97     840 1002.13  1149.8 1004.68
  1169.8 1008.68  1209.8 1028.51  1229.8 1044.18  1249.8 1050.84  1339.7 1107.64
  1359.7 1114.38  1449.7 1174.27  1469.7  1180.7  1549.6  1241.2  1679.6 1304.33
#Mann= 3 , 0 , 0
       0      .1       0   609.8    .045       0   679.8     .06       0
Bank Sta=609.8,679.8
XS Rating Curve= 0 ,0
Exp/Cntr=0.3,0.1

Type RM Length L Ch R = 1 ,44500.7 ,740.9,774.5,808
XS GIS Cut Line= 3
     1815040.177      320663.042     1816196.035      320889.277
     1816445.311      320933.069
#Sta/Elev= 30
       0 1115.21    69.9 1092.66    89.8 1084.16   199.6 1053.36   219.6 1050.77
   299.4 1047.61   369.3 1038.46   389.3 1033.26   399.2  1027.7   489.1  1002.7
     519  999.88   568.9  999.51   686.1  984.88   708.7     984   756.1   984.1
   798.5  986.33   818.5  991.24   908.3  1006.3   958.2 1008.56   968.2 1012.04
  1008.1 1018.36    1038 1025.26    1058 1036.36  1097.9 1052.54  1137.9 1065.01
    1207  1082.5  1284.9 1109.39  1362.7 1145.02  1382.2  1158.3  1430.9 1181.91
#Mann= 3 , 0 , 0
       0      .1       0   686.1    .045       0   756.1      .1       0
Bank Sta=686.1,756.1
XS Rating Curve= 0 ,0
Exp/Cntr=0.3,0.1

Type RM Length L Ch R = 1 ,43726.2 ,444.2,429.5,414.9
XS GIS Cut Line= 3
     1814887.988      320881.305     1815363.216      321432.796
     1815838.444      321984.288
#Sta/Elev= 30
       0 1185.81      20 1167.14    29.9  1160.8   119.7 1111.58   139.6 1096.74
   219.4 1052.68   249.3 1038.43   269.3 1024.83   289.2 1018.99   319.1 1005.81
     379  994.84   608.3   993.5   678.1  981.26     728  979.87     738  980.15
     748  981.98   797.8 1000.54   877.6 1005.85   947.4 1017.44  1136.9 1071.56
  1156.8 1079.61  1176.8 1091.61  1216.7 1104.81  1276.5 1129.09  1296.4 1143.04
  1326.4 1158.18  1346.3 1164.97  1386.2 1185.73    1436  1217.3    1456 1227.47
#Mann= 3 , 0 , 0
       0     .08       0   678.1    .045       0     738     .08       0
#XS Ineff= 2 , 0
          559.43 1003.91
Permanent Ineff=
       F       F
Bank Sta=678.1,738
XS Rating Curve= 0 ,0
Exp/Cntr=0.3,0.1

Type RM Length L Ch R = 1 ,43296.7 ,354.4,351.8,349.1
XS GIS Cut Line= 2
     1814451.262      321351.697     1815684.055      322137.526
#Sta/Elev= 30
       0 1155.55    79.6 1138.91   119.3    1120     189 1092.25   258.6 1061.95
   288.4 1045.79   298.4 1038.14   387.9  992.99   487.3  989.12   586.8  990.56
   666.3  989.29   696.2  979.79   702.6  979.36   716.1   979.1   772.6  979.99
   815.5  994.22   954.7 1003.19  1004.5 1010.82  1044.2  1021.6  1054.2 1027.18
  1133.8 1059.97  1153.6 1072.67  1193.4 1087.46  1233.2 1104.68  1253.1 1117.47
  1332.7 1156.85  1402.3 1186.12  1432.1 1203.12    1452 1218.87    1462 1224.67
#Mann= 3 , 0 , 0
       0     .08       0   702.6    .045       0   772.6     .08       0
Bank Sta=702.6,772.6
XS Rating Curve= 0 ,0
Exp/Cntr=0.3,0.1

Type RM Length L Ch R = 1 ,42944.9 ,641,605.5,570.1
XS GIS Cut Line= 3
     1813824.556      321736.167     1814186.779      321646.196
     1815385.724      322325.386
#Sta/Elev= 30
       0 1180.22    49.1 1198.05    88.4 1202.27   117.9 1198.07   137.5 1190.36
   255.4 1175.23   265.2 1169.83   333.9 1152.05   413.2 1102.25   423.2 1095.03
   443.1 1074.58   463.1 1061.01     513 1033.47   652.8 1002.99   722.7  995.22
   892.5  988.09   982.3  986.33  1072.2  989.05  1109.8   979.9  1132.1   978.5
  1179.8   978.5  1321.8  992.24  1431.7 1012.64  1521.5 1041.12  1541.5 1051.24
  1611.4 1077.35  1631.4 1090.04  1711.2 1129.61  1721.2  1138.5  1751.2 1156.33
#Mann= 3 , 0 , 0
       0      .1       0  1109.8    .045       0  1179.8      .1       0
Bank Sta=1109.8,1179.8
XS Rating Curve= 0 ,0
Exp/Cntr=0.3,0.1

Type RM Length L Ch R = 1 ,42339.4 ,1043,1048.7,1054.3
XS GIS Cut Line= 3
     1813681.963      322692.362     1814402.493      322574.931
     1815217.173      322421.713
#Sta/Elev= 30
       0 1046.96      50 1036.98      70 1030.79     130 1021.33     140 1014.94
     160 1007.84     170 1006.97     230 1007.07     310  994.27     500  992.89
     740  988.14     760  986.89     770   984.7   839.9   977.7   869.9     977
   873.9     977   943.9  977.01   989.7  977.42  1099.6  981.85  1309.3  986.43
  1319.3  987.79  1339.3  995.37  1379.2 1014.63  1389.2 1023.55  1399.2 1028.84
  1459.1 1053.38  1479.1 1065.83    1529 1091.71    1539 1095.88    1559 1108.51
#Mann= 3 , 0 , 0
       0      .1       0   873.9    .045       0   943.9      .1       0
Bank Sta=873.9,943.9
XS Rating Curve= 0 ,0
Exp/Cntr=0.3,0.1

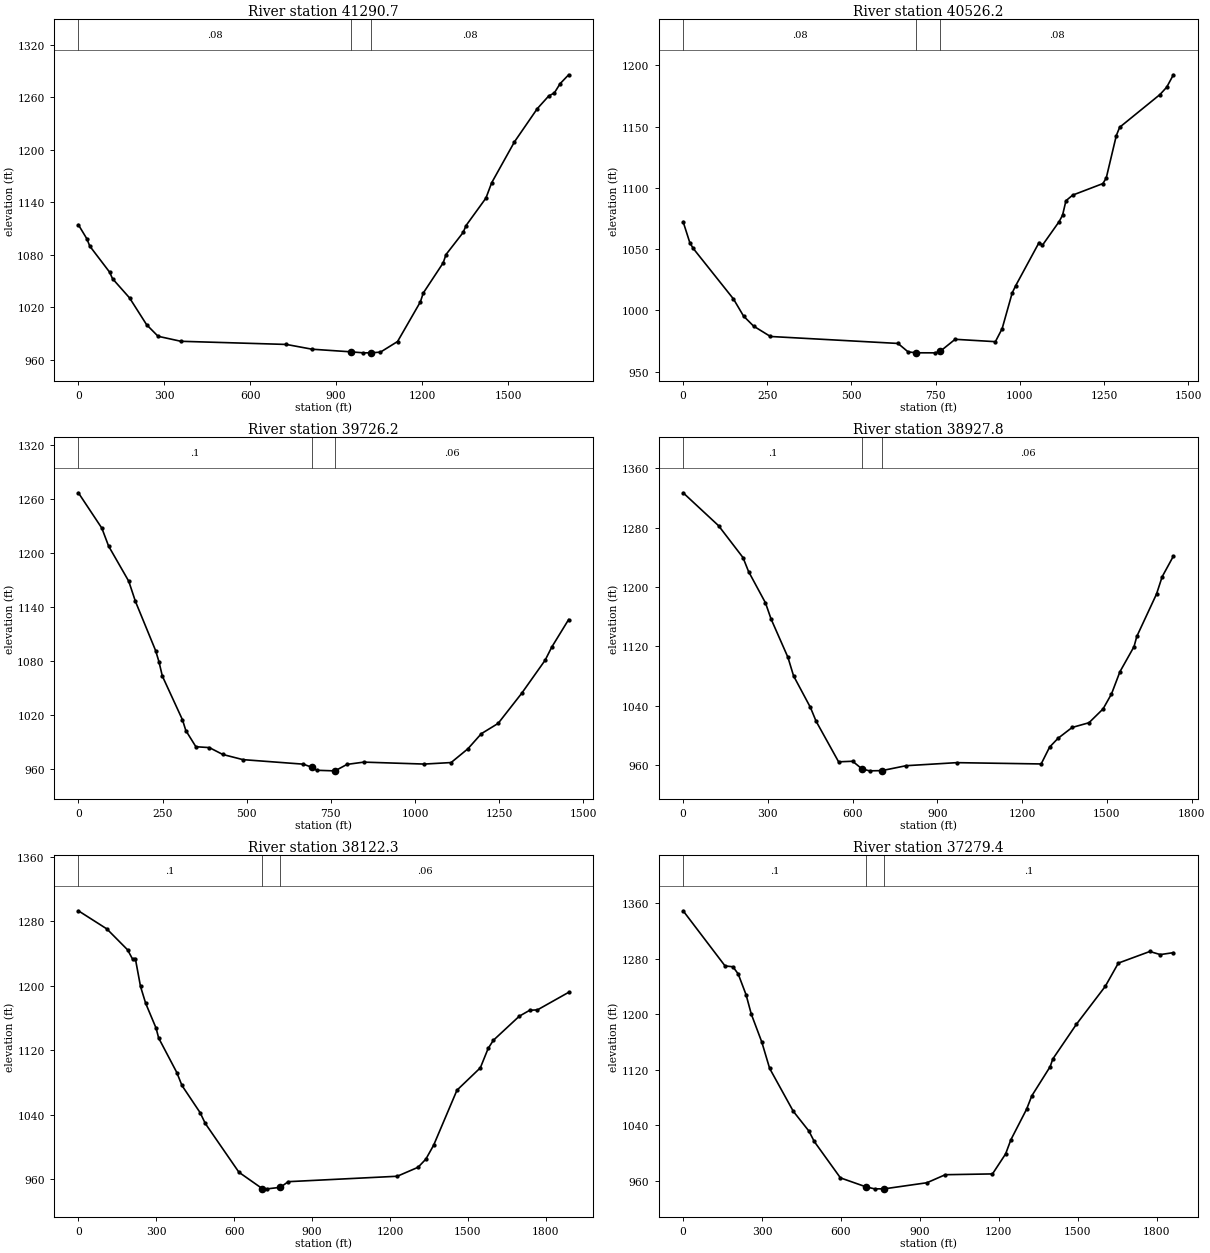
Type RM Length L Ch R = 1 ,41290.7 ,750.5,764.5,778.4
XS GIS Cut Line= 3
     1813982.871      323516.778     1814171.512      323513.409
     1815687.196        323364.1
#Sta/Elev= 30
       0 1114.35    29.8  1098.2    39.7    1090   109.2 1060.12   119.2 1052.73
   178.7 1030.76   238.4 1000.08   278.3  986.91   357.9   981.2   726.2  977.59
   815.8  972.15   950.2  969.18     995     968  1020.2     968  1054.7  968.81
  1114.4  980.93  1194.1 1026.24    1204 1036.24  1273.7 1070.81  1283.6 1080.31
  1343.4 1105.53  1353.3 1113.31    1423 1144.82  1442.9 1162.26  1522.6 1209.07
  1602.2 1246.95    1642 1261.39  1661.9 1264.97  1681.8 1275.45  1711.7 1285.66
#Mann= 3 , 0 , 0
       0     .08       0   950.2    .045       0  1020.2     .08       0
Bank Sta=950.2,1020.2
XS Rating Curve= 0 ,0
Exp/Cntr=0.3,0.1

Type RM Length L Ch R = 1 ,40526.2 ,814.4,800,785.6
XS GIS Cut Line= 3
     1814182.624      324059.509     1814898.941       324189.41
     1815615.258      324319.312
#Sta/Elev= 30
       0 1072.37      20 1055.15    29.9 1050.59   149.6 1009.23   179.5  995.29
   209.4  987.08   259.3  978.63   638.2  972.94   668.2  966.04     693   965.3
     748  965.27     763  966.41   807.8  976.33   927.4  974.39   947.4  985.02
   977.3 1014.24   987.3 1019.94  1057.1 1055.38  1067.1 1053.18  1116.9 1072.54
  1126.9 1077.76  1136.9  1089.5  1156.8 1094.08  1246.6 1103.52  1256.6 1108.11
  1286.5 1142.74  1296.4  1149.5  1416.1 1176.24  1436.1 1182.24    1456 1192.38
#Mann= 3 , 0 , 0
       0     .08       0     693    .045       0     763     .08       0
Bank Sta=693,763
XS Rating Curve= 0 ,0
Exp/Cntr=0.3,0.1

Type RM Length L Ch R = 1 ,39726.2 ,809.6,798.4,787.3
XS GIS Cut Line= 3
     1814165.909      325063.255     1814889.633       324984.47
     1815613.358      324905.686
#Sta/Elev= 30
       0 1267.11    69.8 1227.71    89.8 1207.82   149.6 1168.75   169.5 1146.27
   229.4  1091.6   239.3 1079.31   249.3 1063.37   309.2 1014.61   319.1 1002.74
     349  984.68   388.9  983.75   428.8   976.1   488.7  970.35   668.2  965.31
     693  961.88   708.1  958.51   757.9  957.89     763  958.02   797.8  965.06
   847.7  967.58  1027.2  965.42    1107   967.1  1156.8  982.41  1196.7   999.2
  1246.6 1010.64  1316.4 1044.04  1386.2 1080.92  1406.1 1095.67    1456 1126.14
#Mann= 3 , 0 , 0
       0      .1       0     693    .045       0     763     .06       0
Bank Sta=693,763
XS Rating Curve= 0 ,0
Exp/Cntr=0.3,0.1

Type RM Length L Ch R = 1 ,38927.8 ,808.7,805.5,802.2
XS GIS Cut Line= 3
     1814400.576      326006.165     1814602.692      325915.213
     1816034.343      325423.399
#Sta/Elev= 30
       0 1327.06   125.3 1282.78     212 1239.74   231.6 1220.99   291.4 1178.84
   311.3 1157.04     371 1105.41   390.9 1080.45   450.7 1037.82   470.6 1019.38
   550.3  964.65   600.1  965.39   633.3  955.03   659.8  952.49   703.3  952.78
   789.3  959.41   968.6  963.52  1267.3  961.76  1297.2  984.47  1327.1  996.35
  1376.9 1010.91  1436.6 1017.29  1486.4 1035.88  1516.3 1056.06  1546.2 1086.02
    1596 1119.79  1605.9 1133.57  1675.6  1190.6  1695.6 1213.93  1735.4 1241.73
#Mann= 3 , 0 , 0
       0      .1       0   633.3    .045       0   703.3     .06       0
Bank Sta=633.3,703.3
XS Rating Curve= 0 ,0
Exp/Cntr=0.3,0.1

Type RM Length L Ch R = 1 ,38122.3 ,841.9,842.9,843.9
XS GIS Cut Line= 3
     1814666.821       326792.53     1815338.426      326511.584
     1816408.256      326063.431
#Sta/Elev= 30
       0 1292.85   109.7 1270.37   189.5 1244.46   209.4 1232.56   219.4  1233.6
   239.3 1199.06   259.3 1178.06   299.2 1147.42   309.2 1135.11     379  1092.4
   398.9  1076.3   468.7  1042.7   488.7 1029.25   618.3  968.76     708   948.5
     728   948.2     778  950.09     808  957.08    1228   963.8    1308  974.92
    1338  984.99    1368 1002.25  1457.9 1070.48  1547.9 1098.22  1577.9 1122.17
  1597.9 1132.28  1697.9  1162.2  1737.9 1169.52  1767.9 1170.04  1887.9 1191.76
#Mann= 3 , 0 , 0
       0      .1       0     708    .045       0     778     .06       0
Bank Sta=708,778
XS Rating Curve= 0 ,0
Exp/Cntr=0.3,0.1

Type RM Length L Ch R = 1 ,37279.4 ,476.6,480.6,484.6
XS GIS Cut Line= 2
      1814994.77      327552.437     1816728.272      326868.524
#Sta/Elev= 30
       0 1348.85   159.4 1269.36   189.3 1268.17   209.3 1257.87   239.2 1227.93
   259.1 1199.99     299 1159.72   328.9  1121.7   418.6 1060.01   478.3 1031.36
   498.3  1016.5   597.9     964   694.5  951.14   727.5   948.2   764.5   948.2
   926.8     957   996.5  968.56  1175.9  969.71  1225.8  998.56  1245.7 1018.84
  1305.5 1062.96  1325.4 1082.27  1395.2 1124.32  1405.1 1135.31  1494.8  1185.3
  1604.4 1239.89  1654.3 1273.48  1773.8 1290.19  1813.7 1285.74  1863.5  1288.5
#Mann= 3 , 0 , 0
       0      .1       0   694.5    .045       0   764.5      .1       0
Bank Sta=694.5,764.5
XS Rating Curve= 0 ,0
Exp/Cntr=0.3,0.1