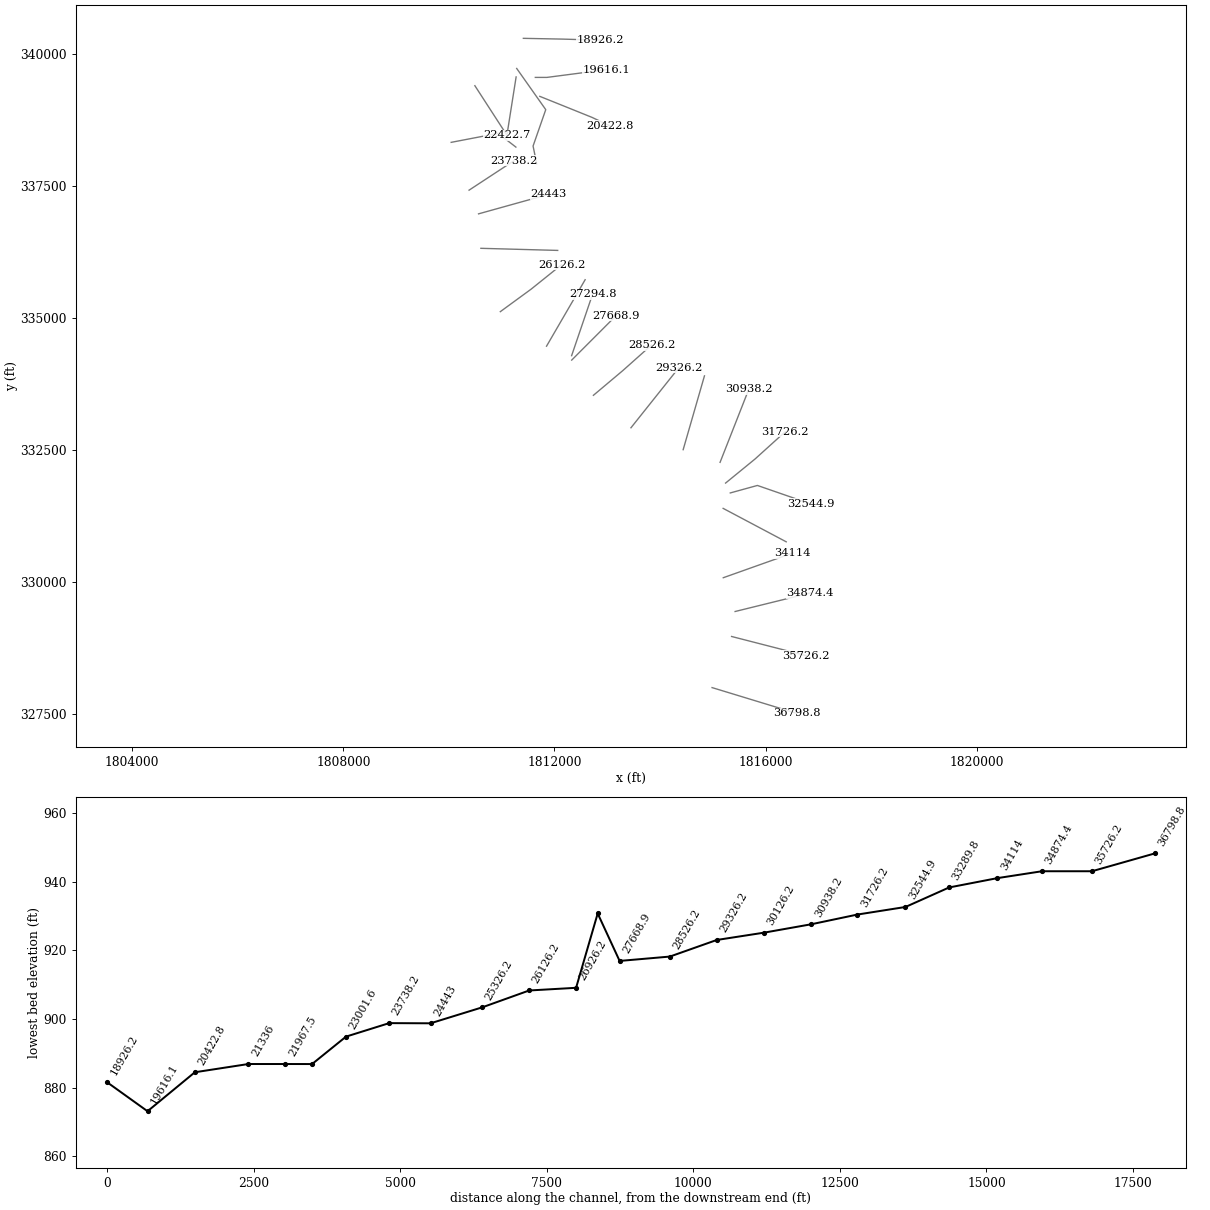
HEC-RAS study MrshFrk1.prj: MrshFrk1

--- MrshFrk1.g01 (geometry) --- (continued)

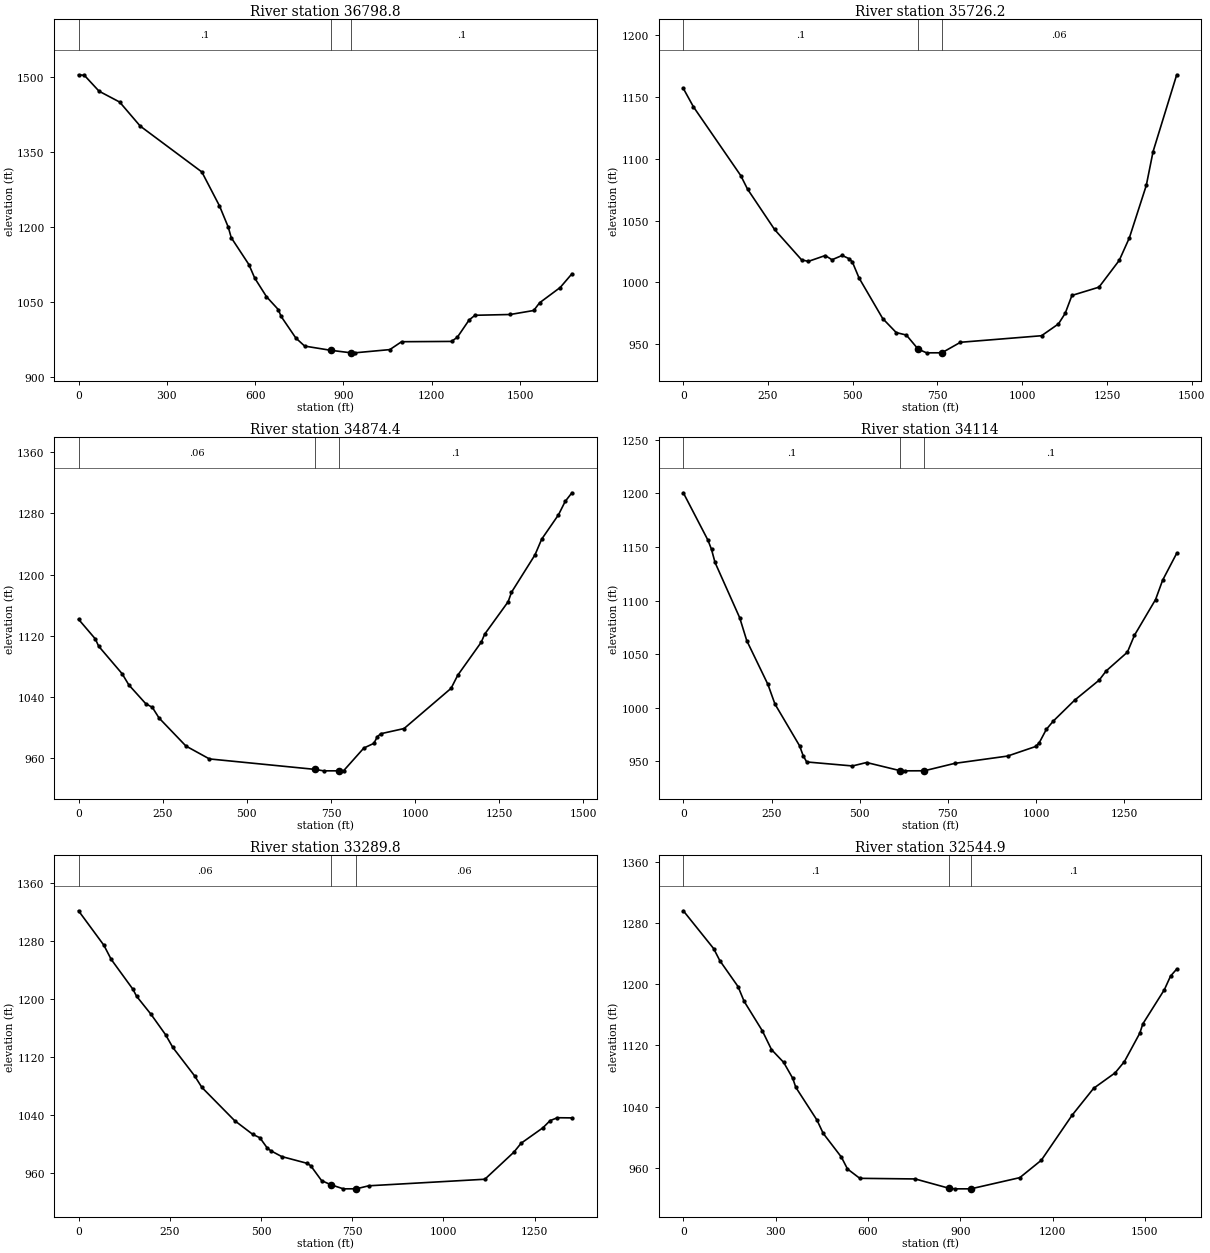
Type RM Length L Ch R = 1 ,36798.8 ,1070.4,1072.6,1074.8
XS GIS Cut Line= 2
     1814986.711      327993.633      1816590.16      327505.188
#Sta/Elev= 30
       0 1505.06      20  1503.9    69.8 1472.16   139.7 1450.46   209.5 1402.36
     419 1310.42   478.9 1242.47   508.8 1199.78   518.8 1178.82   578.7 1125.08
   598.6  1097.9   638.6 1060.61   678.5 1034.96   688.4 1021.03   738.3  977.84
   768.3  961.71   856.5  953.29   926.5   948.2   937.9  948.19  1057.6  954.67
  1097.5  970.46  1267.1  971.06  1287.1  979.55    1327 1014.04  1346.9 1023.41
  1466.7 1024.98  1546.5 1033.01  1566.4 1048.45  1636.3 1079.02  1676.2 1106.47
#Mann= 3 , 0 , 0
       0      .1       0   856.5    .045       0   926.5      .1       0
Bank Sta=856.5,926.5
XS Rating Curve= 0 ,0
Exp/Cntr=0.3,0.1

Type RM Length L Ch R = 1 ,35726.2 ,827,851.8,876.7
XS GIS Cut Line= 2
     1815356.552      328962.194     1816766.677      328599.589
#Sta/Elev= 30
       0 1156.86    29.9 1141.96   169.5 1086.37   189.5 1075.41   269.3 1042.76
     349 1018.22     369 1016.97   418.8  1021.7   438.8 1018.28   468.7 1021.77
   488.7 1019.22   498.6 1016.65   518.6 1003.55   588.4  970.73   628.3   959.4
   658.2  957.38     693  945.99     718     943     763  943.04   817.8  951.54
  1057.1  956.84    1107  966.39  1126.9  974.94  1146.8  989.43  1226.6  996.12
  1286.5 1017.82  1316.4  1036.1  1366.2  1078.4  1386.2 1105.74    1456 1167.89
#Mann= 3 , 0 , 0
       0      .1       0     693    .045       0     763     .06       0
Bank Sta=693,763
XS Rating Curve= 0 ,0
Exp/Cntr=0.3,0.1

Type RM Length L Ch R = 1 ,34874.4 ,755.7,760.5,765.3
XS GIS Cut Line= 2
     1815423.468      329435.488     1816846.488      329786.448
#Sta/Elev= 30
       0 1141.46    49.8 1115.74    59.8 1106.18   129.6 1070.08   149.6  1055.4
   199.4 1031.06   219.4 1026.03   239.3 1012.13   319.1  975.47   388.8   958.6
   703.7  944.85   727.8     943   773.7  943.02   787.7  943.24   847.5  972.83
   877.4  979.01   887.4  987.46   897.3  991.52   967.1  998.38  1106.7 1051.02
  1126.7 1068.29  1196.5  1111.5  1206.4 1121.83  1276.2 1164.36  1286.2 1176.77
    1356 1225.73  1375.9 1246.33  1425.8 1278.21  1445.7 1295.71  1465.7 1307.03
#Mann= 3 , 0 , 0
       0     .06       0   703.7    .045       0   773.7      .1       0
Bank Sta=703.7,773.7
XS Rating Curve= 0 ,0
Exp/Cntr=0.3,0.1

Type RM Length L Ch R = 1 ,34114   ,865.5,824,782.6
XS GIS Cut Line= 2
     1815198.932      330075.422     1816516.738      330544.012
#Sta/Elev= 30
       0 1200.67    69.9 1156.34    79.9  1147.8    89.9  1135.6   159.8 1083.98
   179.8 1062.62   239.8 1021.71   259.8 1003.34   329.7  964.31   339.7  955.16
   349.7   949.3   479.5  945.56   519.5  948.78   613.3  941.25   629.4     941
   683.3  941.06   769.2  947.97   919.1  954.79     999  963.76    1009  967.26
    1029  979.72    1049  987.55  1108.9 1006.87  1178.8 1025.71  1198.8 1034.36
  1258.8 1051.81  1278.8 1067.58  1338.7    1101  1358.7 1119.04  1398.6 1144.18
#Mann= 3 , 0 , 0
       0      .1       0   613.3    .045       0   683.3      .1       0
Bank Sta=613.3,683.3
XS Rating Curve= 0 ,0
Exp/Cntr=0.3,0.1

Type RM Length L Ch R = 1 ,33289.8 ,737.2,744.9,752.6
XS GIS Cut Line= 2
     1815196.578      331389.293     1816391.413      330755.877
#Sta/Elev= 30
       0 1321.64    69.6 1274.06    89.5 1254.69   149.2 1213.38   159.1 1203.83
   198.9 1178.77   238.6 1150.76   258.5 1133.19   318.2 1094.04   338.1 1078.14
   427.6 1032.45   477.3 1013.47   497.2 1008.65   517.1   994.7     527  990.82
   556.8  982.81   626.5  973.48   636.4   970.2   666.2  949.63   691.4     944
   725.9  938.28   761.4  938.33   795.5  942.48  1113.7  951.51  1193.2  988.79
  1213.1 1001.13  1272.8 1022.41  1292.7 1032.36  1312.6 1036.32  1352.4  1036.1
#Mann= 3 , 0 , 0
       0     .06       0   691.4    .045       0   761.4     .06       0
Bank Sta=691.4,761.4
XS Rating Curve= 0 ,0
Exp/Cntr=0.3,0.1

Type RM Length L Ch R = 1 ,32544.9 ,767.7,818.7,871.6
XS GIS Cut Line= 3
     1815331.478      331681.932     1815845.702       331823.72
     1816856.549      331473.549
#Sta/Elev= 30
       0  1296.1    98.8 1246.54   118.5 1230.99   177.8 1197.02   197.6 1177.73
   256.8 1139.17   286.5 1114.66     326 1097.95   355.6 1077.05   365.5 1065.28
   434.6 1022.28   454.4 1005.21   513.7  974.05   533.4  958.58   573.4  946.34
   753.4  945.53   864.2  933.27   883.3   932.6   934.2   932.6  1093.3  947.23
  1163.3  970.02  1263.3 1028.85  1333.2 1064.01  1403.2 1084.25  1433.2 1098.92
  1483.2 1136.05  1493.2 1148.29  1563.2 1193.03  1583.2 1210.75  1603.2 1219.92
#Mann= 3 , 0 , 0
       0      .1       0   864.2    .045       0   934.2      .1       0
Bank Sta=864.2,934.2
XS Rating Curve= 0 ,0
Exp/Cntr=0.3,0.1

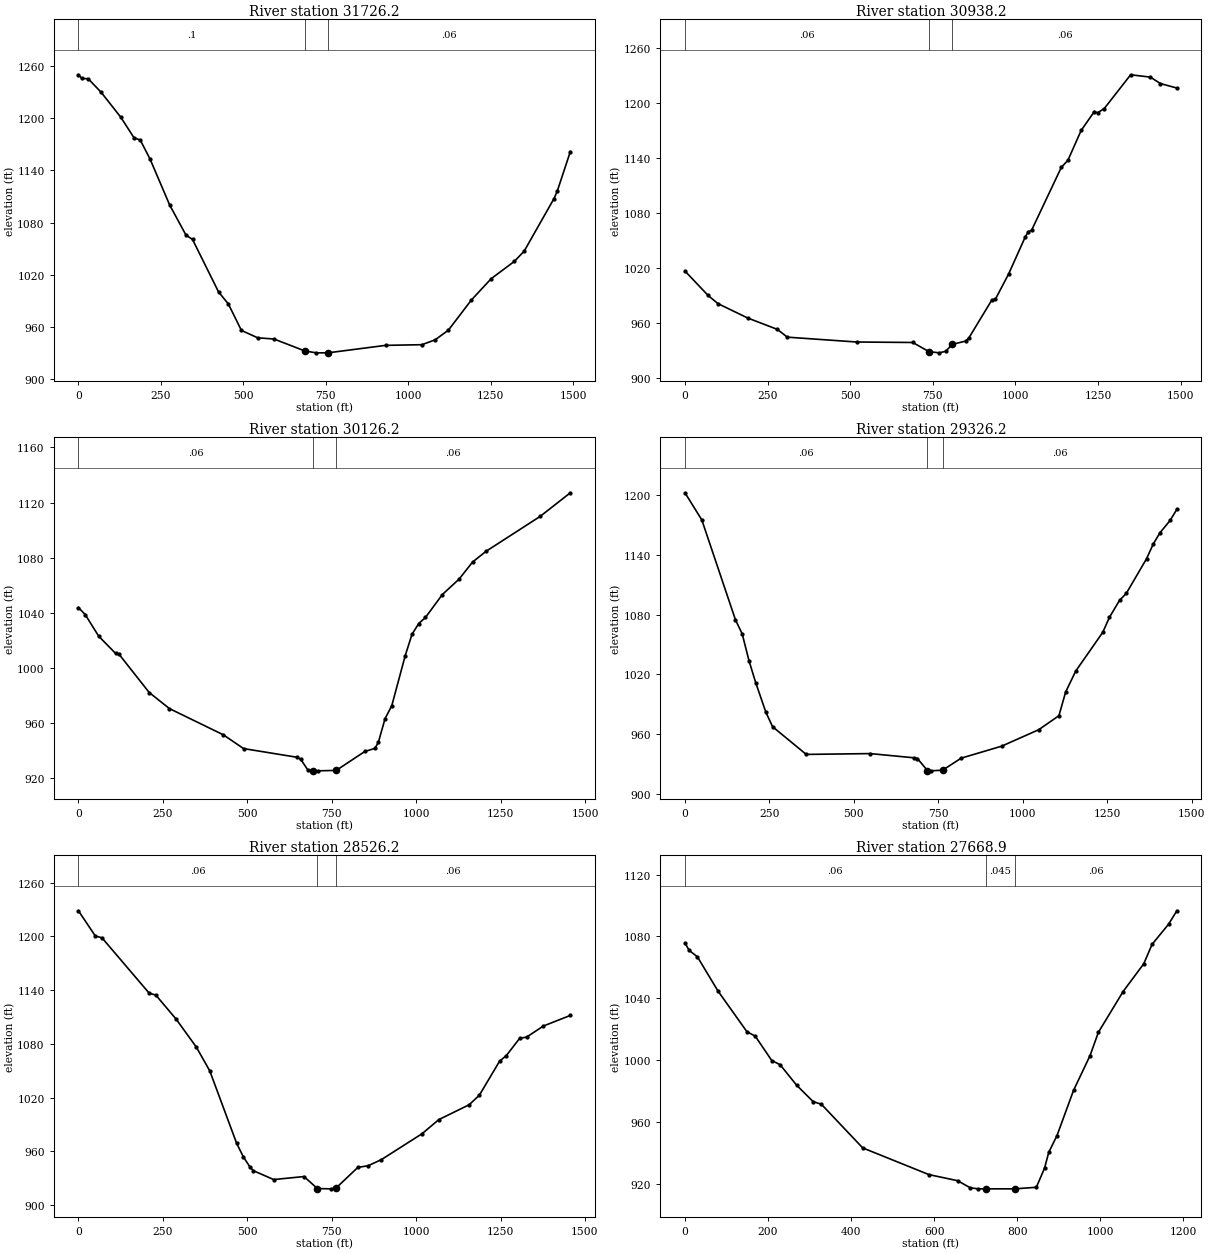
Type RM Length L Ch R = 1 ,31726.2 ,762.1,788,812
XS GIS Cut Line= 3
     1815242.767      331868.958     1815801.538      332325.352
     1816372.989      332841.996
#Sta/Elev= 30
       0 1249.55     9.9 1245.34    29.6    1245    69.2 1229.26   128.5  1200.8
     168 1177.53   187.8 1174.42   217.4 1152.58   276.7 1100.04   326.1 1065.55
   345.9 1060.57     425 1000.25   454.6  986.53   494.2  956.14   543.6  947.65
     593  946.27   686.5  932.57   721.5   930.4   756.5   930.4   931.6  938.99
  1041.6  939.74  1081.6   945.3  1121.7  956.34  1191.7  991.06  1251.7 1015.52
  1321.8  1035.3  1351.8 1047.14  1441.8 1107.18  1451.8 1115.62  1491.8 1161.45
#Mann= 3 , 0 , 0
       0      .1       0   686.5    .045       0   756.5     .06       0
Bank Sta=686.5,756.5
XS Rating Curve= 0 ,0
Exp/Cntr=0.3,0.1

Type RM Length L Ch R = 1 ,30938.2 ,807.2,811.9,816.6
XS GIS Cut Line= 2
     1815138.298      332261.636     1815682.939      333647.467
#Sta/Elev= 30
       0 1016.77      70  990.14    99.9  981.22   189.9  965.55   279.8  953.13
   309.8  944.67   519.7  939.38   689.5  938.86   738.3  928.94   769.5  927.57
   789.5  929.27   808.3  936.67   849.4  940.41   859.4  943.83   929.4  985.49
   939.4  985.88   979.4 1013.33  1029.3 1053.35  1039.3 1059.66  1049.3 1061.29
  1139.2  1129.8  1159.2 1137.53  1199.2 1170.02  1239.2 1190.71  1249.2  1189.3
  1269.2 1193.97  1349.1 1230.78  1409.1 1228.21    1439 1221.23    1489 1216.33
#Mann= 3 , 0 , 0
       0     .06       0   738.3    .045       0   808.3     .06       0
Bank Sta=738.3,808.3
XS Rating Curve= 0 ,0
Exp/Cntr=0.3,0.1

Type RM Length L Ch R = 1 ,30126.2 ,819.6,800,780.2
XS GIS Cut Line= 3
     1814438.963       332501.39     1814640.736      333200.869
     1814842.509      333900.349
#Sta/Elev= 30
       0 1043.68      20 1038.63    59.8 1022.96   109.7 1010.44   119.7 1009.93
   209.4  982.01   269.3  970.33   428.8  951.29   488.7  941.28   648.2  934.92
   658.2   933.4   678.1  926.05     693  925.12     708  925.11     763  925.43
   847.7  939.17   877.6  941.45   887.6  945.74   907.5  962.98   927.4   972.4
   967.3 1008.85   987.3 1024.29  1007.2 1032.11  1027.2 1036.52    1077 1053.14
  1126.9 1064.44  1166.8 1076.83  1206.7 1084.62  1366.2 1109.86    1456 1127.09
#Mann= 3 , 0 , 0
       0     .06       0     693    .045       0     763     .06       0
Bank Sta=693,763
XS Rating Curve= 0 ,0
Exp/Cntr=0.3,0.1

Type RM Length L Ch R = 1 ,29326.2 ,810,800,791.5
XS GIS Cut Line= 3
     1813449.843      332916.434     1813903.501      333485.731
     1814357.695      334055.067
#Sta/Elev= 30
       0 1202.24    49.9 1174.96   149.6 1074.54   169.5  1060.5   189.5 1033.62
   209.4 1011.58   239.3  982.06   259.3  967.35     359   939.5   548.4  940.32
   678.1  936.09   688.1  935.38     718  923.27     728     923   762.9  923.69
   817.7  935.73   937.5  947.76  1047.2  964.29  1107.1  978.37    1127 1002.16
    1157 1023.26  1236.8 1062.04  1256.7 1077.17  1286.6 1094.23  1306.6 1101.22
  1366.5 1135.97  1386.4  1150.8  1406.4 1162.14  1436.3 1174.44  1456.3 1185.65
#Mann= 3 , 0 , 0
       0     .06       0     718    .045       0   762.9     .06       0
Bank Sta=718,762.9
XS Rating Curve= 0 ,0
Exp/Cntr=0.3,0.1

Type RM Length L Ch R = 1 ,28526.2 ,852.9,857.3,860.3
XS GIS Cut Line= 3
     1812738.625      333532.034     1813295.702      334000.263
     1813840.062      334485.324
#Sta/Elev= 30
       0 1228.66    49.8 1200.59    69.8 1198.44   209.3 1136.73   229.3 1134.45
   289.1 1107.76   348.9 1076.56   388.8 1049.98   468.5  969.02   488.5   953.8
   508.4  942.31   518.4  938.36   578.2  928.53   667.9  931.89   707.8  918.48
   747.7  918.17   762.7     919   827.6  942.16   857.6  943.92   897.5  950.88
  1017.4  979.66  1067.3  995.48  1157.2 1012.08  1187.2 1022.68  1247.1 1060.62
  1267.1 1066.94    1307 1086.38    1327 1087.53  1376.9 1099.96  1456.8 1111.82
#Mann= 3 , 0 , 0
       0     .06       0   707.8    .045       0   762.7     .06       0
Bank Sta=707.8,762.7
XS Rating Curve= 0 ,0
Exp/Cntr=0.3,0.1

Type RM Length L Ch R = 1 ,27668.9 ,351.2,374.1,397
XS GIS Cut Line= 2
     1812327.211       334199.16     1813164.304      335037.354
#Sta/Elev= 30
       0  1075.9      10 1071.02    29.9 1066.88    79.6 1044.71   149.3 1018.42
   169.2 1015.61     209  999.82     229  997.16   268.8  983.91   308.6  973.28
   328.5  971.57     428  943.36   587.3  926.12     657  922.13   686.9  917.55
   706.8   916.9   724.3   916.9   794.3   916.9   846.2   917.9   866.1  930.39
     876  940.46   895.9  951.31   935.7   980.5   975.6 1003.05   995.5 1018.01
  1055.2 1044.44    1105 1062.42  1124.9 1074.92  1164.7 1087.96  1184.6 1096.61
#Mann= 3 , 0 , 0
       0     .06       0   724.3    .045       0   794.3     .06       0
Bank Sta=724.3,794.3
XS Rating Curve= 0 ,0
Exp/Cntr=0.3,0.1

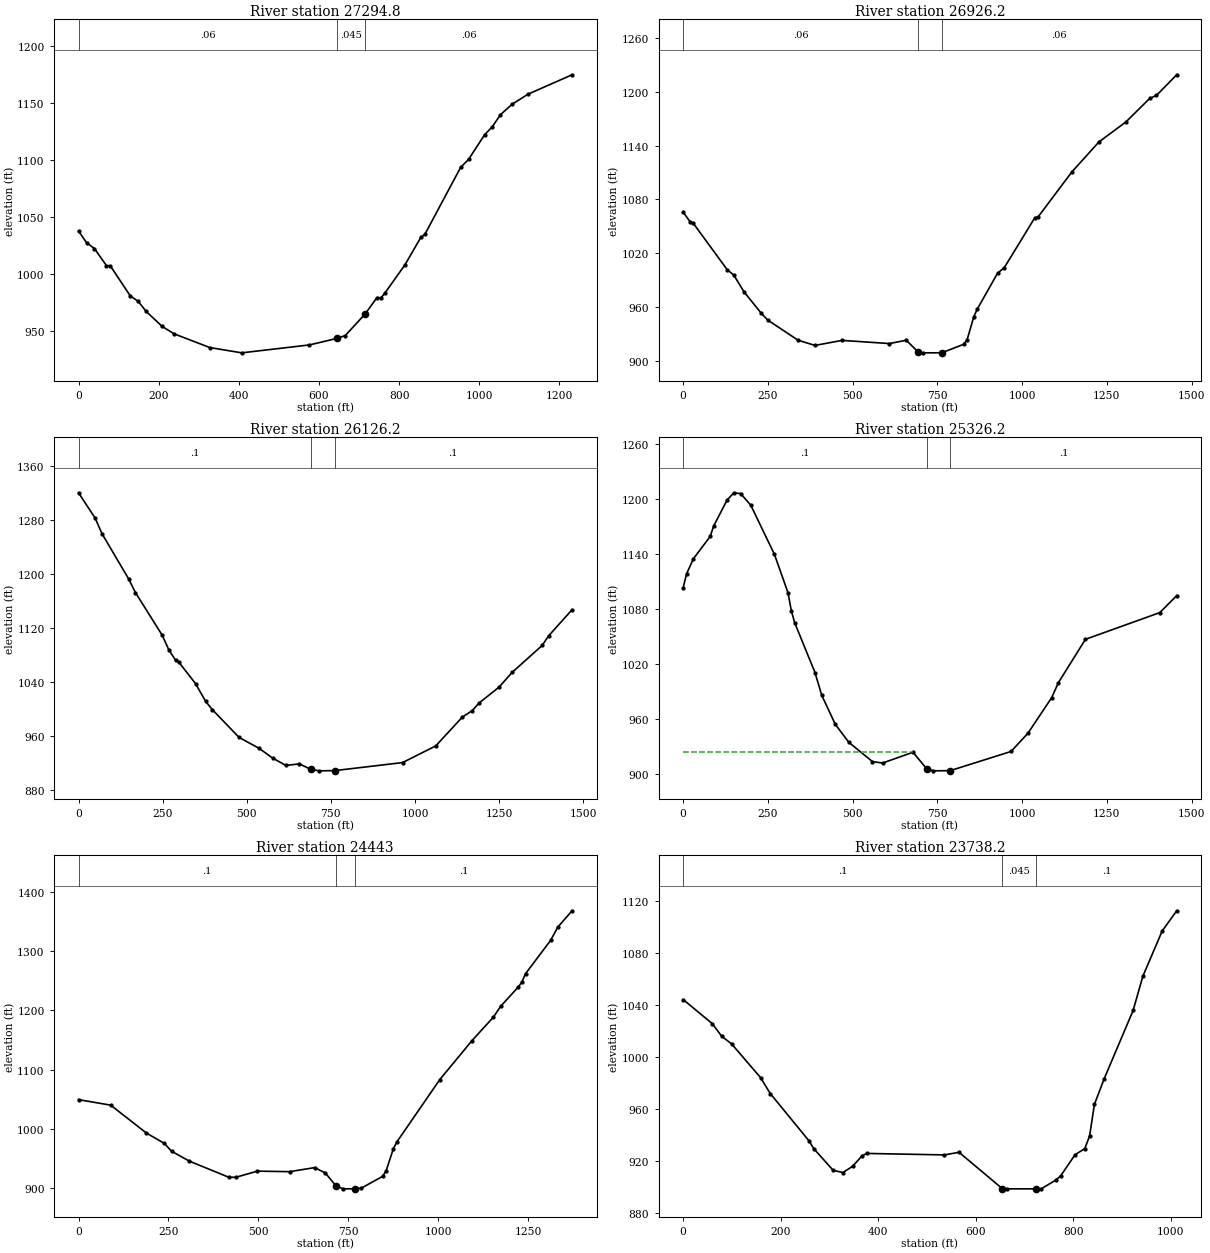
Type RM Length L Ch R = 1 ,27294.8 ,378.5,368.6,358.7
XS GIS Cut Line= 2
     1812325.525       334282.79     1812723.019      335448.322
#Sta/Elev= 30
       0 1037.75    19.9  1027.5    39.7 1022.28    69.5 1007.37    79.4 1007.09
   129.1   980.7     149  975.86   168.8  967.04   208.6  953.92   238.3  947.42
   327.7  935.33   407.2  930.71     576  937.65   644.9  943.39   665.4  945.85
   714.9  964.77   744.8  979.27   754.8  979.06   764.7   983.3   814.4 1007.98
   854.1  1032.1     864 1034.68   953.4 1093.56   973.2 1100.59    1013 1122.13
  1032.8 1129.43  1052.7 1139.82  1082.5 1149.22  1122.2 1157.95  1231.4 1174.89
#Mann= 3 , 0 , 0
       0     .06       0   644.9    .045       0   714.9     .06       0
Bank Sta=644.9,714.9
XS Rating Curve= 0 ,0
Exp/Cntr=0.3,0.1

Type RM Length L Ch R = 1 ,26926.2 ,820.7,800,781.5
XS GIS Cut Line= 3
      1811850.15      334462.568     1812215.872      335092.038
     1812581.593      335721.508
#Sta/Elev= 30
       0 1065.91      20  1055.3    29.9 1053.41   129.6 1001.89   149.6  995.56
   179.5  977.03   229.4   953.6   249.3  945.62   339.1  923.11   388.9  917.35
   468.7  922.95   608.3  919.43   658.2  923.12     693  910.05   708.1  909.08
     763  909.14   827.7  918.63   837.7  923.82   857.6  949.53   867.6  957.82
   927.4  997.77   947.4 1004.06  1037.2 1059.53  1047.1 1060.61  1146.8 1110.72
  1226.6 1144.15  1306.4 1166.46  1376.2 1192.54  1396.2 1195.93    1456 1218.94
#Mann= 3 , 0 , 0
       0     .06       0     693    .045       0     763     .06       0
Bank Sta=693,763
XS Rating Curve= 0 ,0
Exp/Cntr=0.3,0.1

Type RM Length L Ch R = 1 ,26126.2 ,833,800,764.7
XS GIS Cut Line= 3
     1810974.449      335116.532      1811560.42      335544.743
      1812137.95      336008.523
#Sta/Elev= 30
       0 1320.03    49.7 1282.25    69.6 1259.57   149.1  1192.3     169 1172.32
   248.6 1109.14   268.4 1087.34   288.3 1072.23   298.3 1069.03     348 1037.26
   377.8 1011.05   397.7  998.87   477.2  957.76   536.9  941.53   576.6  927.24
   616.4  916.25   656.2  918.66   690.8  910.29   715.8   908.3   760.8  908.61
   962.8  920.52  1061.5  945.22  1140.6  987.95  1170.2  997.57  1189.9 1008.61
  1249.2 1032.08  1288.7 1054.19  1377.6 1093.94  1397.3 1108.42  1466.5 1146.86
#Mann= 3 , 0 , 0
       0      .1       0   690.8    .045       0   760.8      .1       0
Bank Sta=690.8,760.8
XS Rating Curve= 0 ,0
Exp/Cntr=0.3,0.1

Type RM Length L Ch R = 1 ,25326.2 ,868.2,883.2,898.2
XS GIS Cut Line= 3
     1810606.436      336316.958     1811334.163       336297.02
      1812061.89      336277.082
#Sta/Elev= 30
       0 1103.22      10 1118.23    29.9 1134.56    79.8 1159.06    89.8  1170.3
   129.6 1198.78   149.6 1206.62   169.5 1205.69   199.4 1193.09   269.3 1139.36
   309.2 1097.59   319.1 1078.01   329.1 1064.72   388.9 1010.55   408.9  985.66
   448.8  954.09   488.7  934.49   558.5  913.43   588.4  911.92   678.1  923.69
     718  905.77     738   903.4   787.8  903.61   967.3  924.52  1017.2  944.46
    1087  983.12    1107  999.59  1186.7  1046.8  1406.1 1075.95    1456 1094.48
#Mann= 3 , 0 , 0
       0      .1       0     718    .045       0   787.8      .1       0
#XS Ineff= 2 , 0
          678.04  923.69
Permanent Ineff=
       F       F
Bank Sta=718,787.8
XS Rating Curve= 0 ,0
Exp/Cntr=0.3,0.1

Type RM Length L Ch R = 1 ,24443   ,689.4,704.8,720.3
XS GIS Cut Line= 2
     1810562.247      336969.944      1811884.24      337338.101
#Sta/Elev= 30
       0 1049.44    89.5 1040.05   188.9  992.92   238.7  975.47   258.6  962.29
   308.3  945.49   417.7  918.36   437.5  918.24   497.2  928.65   586.7  927.74
   656.3  934.57   686.2  925.64     716  903.52   735.9  898.75   768.2  898.82
   785.6  899.66   845.3  919.79   855.2  928.95   875.1  965.99     885  977.79
  1004.4 1083.17  1093.9 1148.93  1153.5 1188.65  1173.4 1206.73  1223.1 1239.87
  1233.1 1248.26    1243 1262.19  1312.6 1318.26  1332.5 1340.61  1372.3 1368.34
#Mann= 3 , 0 , 0
       0      .1       0     716    .045       0   768.2      .1       0
Bank Sta=716,768.2
XS Rating Curve= 0 ,0
Exp/Cntr=0.3,0.1

Type RM Length L Ch R = 1 ,23738.2 ,756.2,736.6,716.9
XS GIS Cut Line= 2
      1810382.39      337418.759     1811229.049      337974.203
#Sta/Elev= 30
       0 1044.28    59.6 1025.78    79.4  1015.9    99.3 1010.22   158.8  984.29
   178.7  972.03   258.1  935.73     268  929.65   307.8  913.02   327.6  911.35
   347.5  916.04   367.3  924.31   377.2  926.01   536.1  924.88   565.9  926.89
   654.7  898.99   665.1   898.8   724.7   898.8   734.6  898.81   764.4   905.5
   774.3  908.67   804.1  925.04     824   929.7   833.9  939.53   843.8  963.78
   863.7  983.34   923.2 1035.94   943.1 1062.14   982.8 1097.01  1012.6 1112.51
#Mann= 3 , 0 , 0
       0      .1       0   654.7    .045       0   724.7      .1       0
Bank Sta=654.7,724.7
XS Rating Curve= 0 ,0
Exp/Cntr=0.3,0.1

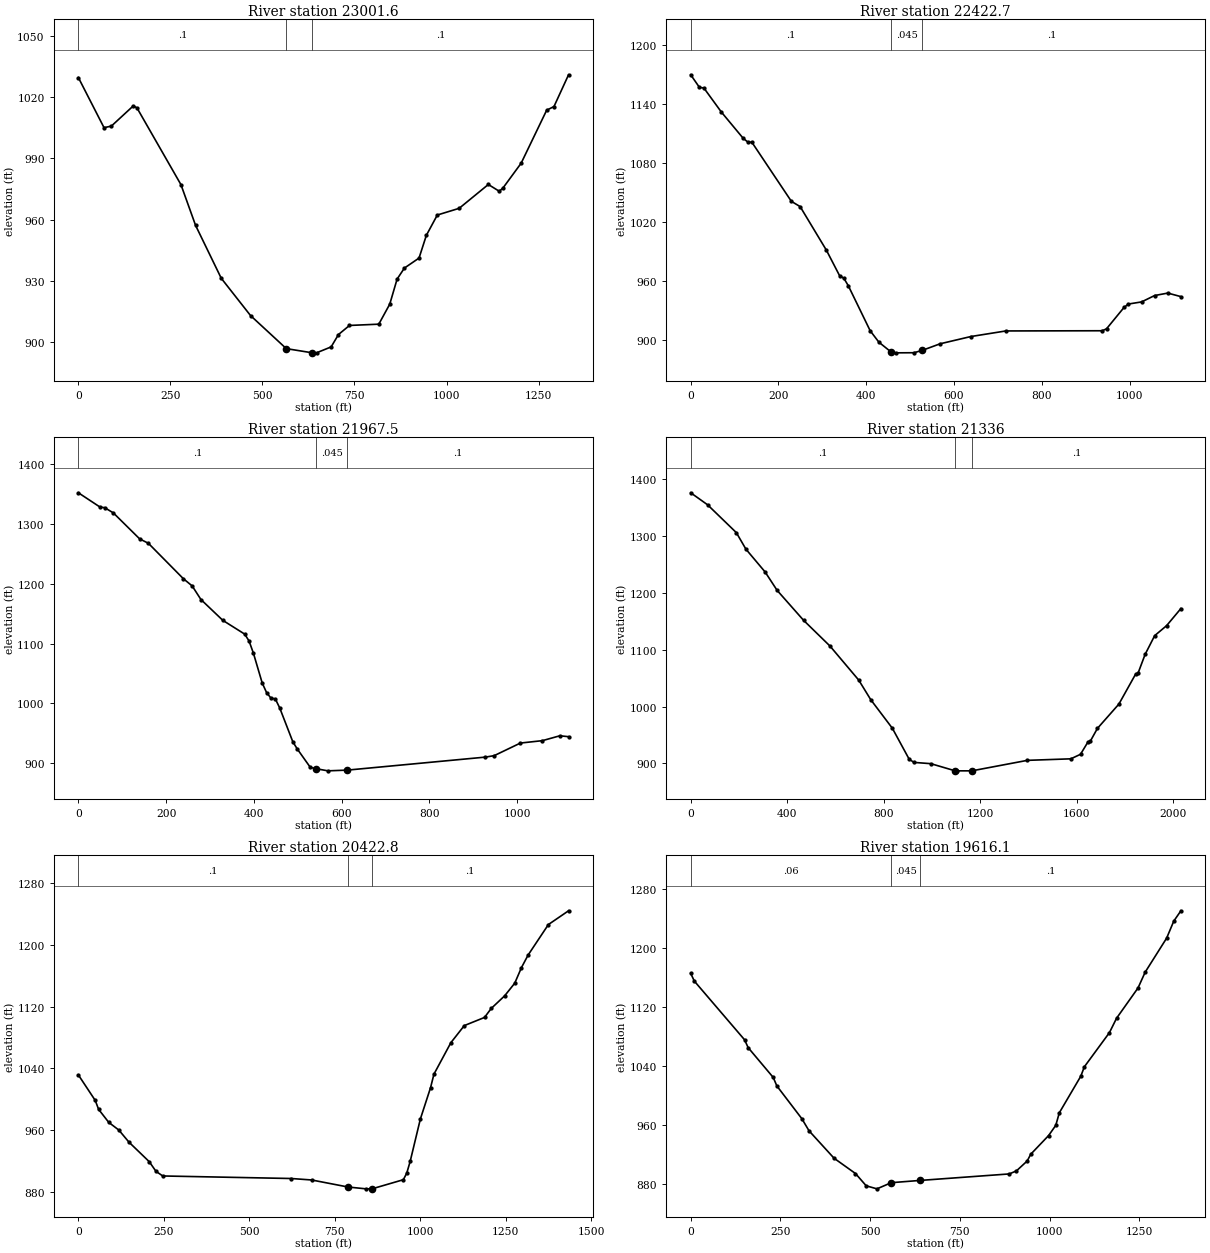
Type RM Length L Ch R = 1 ,23001.6 ,638.8,578.9,519
XS GIS Cut Line= 3
     1810043.306      338324.537     1810932.613      338495.212
     1811269.472      338234.707
#Sta/Elev= 30
       0 1029.52    69.7 1005.01    89.6 1005.77   149.3 1015.68   159.2 1014.68
   278.6  977.15   318.4   957.2   388.1  931.34   467.7  913.09   564.8  896.93
   634.8   894.9   646.8  894.87   686.6  897.78   706.5  903.83   736.4  908.27
     816  908.89   845.8   918.7   865.7  930.94   885.6  936.34   925.3  941.23
   945.2  952.36   974.9  962.28  1034.3  965.56  1113.5  977.22  1143.2   973.9
  1153.1  975.46  1202.6  987.62    1272 1013.57  1291.8 1015.34  1331.4 1030.88
#Mann= 3 , 0 , 0
       0      .1       0   564.8    .045       0   634.8      .1       0
Bank Sta=564.8,634.8
XS Rating Curve= 0 ,0
Exp/Cntr=0.3,0.1

Type RM Length L Ch R = 1 ,22422.7 ,492.4,455.4,418.5
XS GIS Cut Line= 2
     1810492.451      339397.994      1811099.67      338460.316
#Sta/Elev= 30
       0 1169.72      20 1156.82    29.9 1156.34    69.8 1131.83   119.7 1105.03
   129.7 1101.47   139.6 1100.96   229.4 1040.99   249.4 1035.62   309.2   991.3
   339.1  965.51   349.1  962.66   359.1  955.18     409  909.34   428.9   897.7
   457.3   887.5   468.8  886.89   508.7     887   527.3  889.35   568.5  896.11
   638.4  903.47   718.2  909.16   937.6  909.36   947.6  911.33   987.4  933.02
   997.4  936.53  1027.4  938.68  1057.3  945.19  1087.2  947.67  1117.1  944.07
#Mann= 3 , 0 , 0
       0      .1       0   457.3    .045       0   527.3      .1       0
Bank Sta=457.3,527.3
XS Rating Curve= 0 ,0
Exp/Cntr=0.3,0.1

Type RM Length L Ch R = 1 ,21967.5 ,640.3,631.3,622.3
XS GIS Cut Line= 2
     1811273.964      339564.178      1811099.67      338460.316
#Sta/Elev= 30
       0 1352.24    49.9 1328.07    59.9 1327.35    79.8 1318.53   139.7  1275.1
   159.6 1267.72   239.5 1208.33   259.4  1196.4   279.4 1173.62   329.3 1138.75
   379.2  1115.7   389.1 1104.24   399.1 1083.72   419.1 1033.92     429 1017.98
     439  1008.6     449 1007.29     459  992.24   488.9  935.54   498.9  923.62
   528.8  892.68   542.8  890.37   568.8   886.9   612.8  888.09     928  909.88
   947.9   912.3  1007.8  933.41  1057.7  937.39  1097.6  945.55  1117.5  944.07
#Mann= 3 , 0 , 0
       0      .1       0   542.8    .045       0   612.8      .1       0
Bank Sta=542.8,612.8
XS Rating Curve= 0 ,0
Exp/Cntr=0.3,0.1

Type RM Length L Ch R = 1 ,21336   ,835.7,913.2,990.8
XS GIS Cut Line= 4
     1811284.978      339724.733     1811835.395      338944.357
     1811595.101      338254.817      1811664.72      337915.814
#Sta/Elev= 30
       0 1376.31    69.6 1355.26     189 1306.21   228.8 1277.05   308.4 1236.87
   358.1 1204.52   467.5 1151.92     577 1106.58   696.3 1046.57   746.1  1012.1
   835.6   961.8   905.2  907.39   925.1  901.75     995  899.52    1095  887.01
    1105   886.9    1165   886.9  1395.1  905.37  1575.1  908.05  1615.2  916.02
  1645.2  937.12  1655.2   938.6  1685.2  961.57  1774.2 1004.37  1843.4 1057.06
  1853.3 1058.44  1882.9 1091.87  1922.5 1124.84  1971.9 1142.43  2031.2 1172.57
#Mann= 3 , 0 , 0
       0      .1       0    1095    .045       0    1165      .1       0
Bank Sta=1095,1165
XS Rating Curve= 0 ,0
Exp/Cntr=0.3,0.1

Type RM Length L Ch R = 1 ,20422.8 ,780.8,806.7,832.6
XS GIS Cut Line= 4
     1811723.109      339195.878     1812181.237      339011.729
      1812715.72      338796.139     1813044.491      338639.824
#Sta/Elev= 30
       0 1031.64    49.4  998.68    59.2   987.2    88.9  970.36   118.5  960.39
   148.1  944.78   207.4  919.57   227.1  907.09   246.9  901.13   622.9  897.84
   682.6  895.94   789.1  886.85   841.5   884.5   859.1   884.5   950.8  896.31
   960.8  904.87   970.7   919.9  1000.5  974.64  1030.3 1015.12  1040.3 1032.67
  1089.8 1073.29  1129.1 1095.38  1188.2  1105.9  1207.8 1117.49  1247.2 1133.86
  1276.7 1150.18  1296.4 1170.39    1316 1186.67  1375.1  1225.9  1434.1 1243.69
#Mann= 3 , 0 , 0
       0      .1       0   789.1    .045       0   859.1      .1       0
Bank Sta=789.1,859.1
XS Rating Curve= 0 ,0
Exp/Cntr=0.3,0.1

Type RM Length L Ch R = 1 ,19616.1 ,697.2,689.8,682
XS GIS Cut Line= 3
     1811637.771      339555.195     1811857.853      339555.195
      1812994.19      339703.413
#Sta/Elev= 30
       0 1165.96      10 1155.49   150.1 1075.68   160.1 1065.02     230  1024.5
     240 1013.02   309.8   968.4   329.7  952.04   399.4  914.78   459.2  893.95
   489.1  877.25     519  873.16   558.9  881.53   638.6  884.57   887.7  893.42
   907.7  897.57   937.6  910.98   947.5  920.14   997.3  945.56  1017.3  959.43
  1027.2  976.51    1087 1026.18    1097 1039.05  1166.8 1085.42  1186.7 1104.98
  1246.5 1146.13  1266.4 1167.57  1326.2 1213.79  1346.1 1236.93    1366    1251
#Mann= 3 , 0 , 0
       0     .06       0   558.9    .045       0   638.6      .1       0
Bank Sta=558.9,638.6
XS Rating Curve= 0 ,0
Exp/Cntr=0.3,0.1

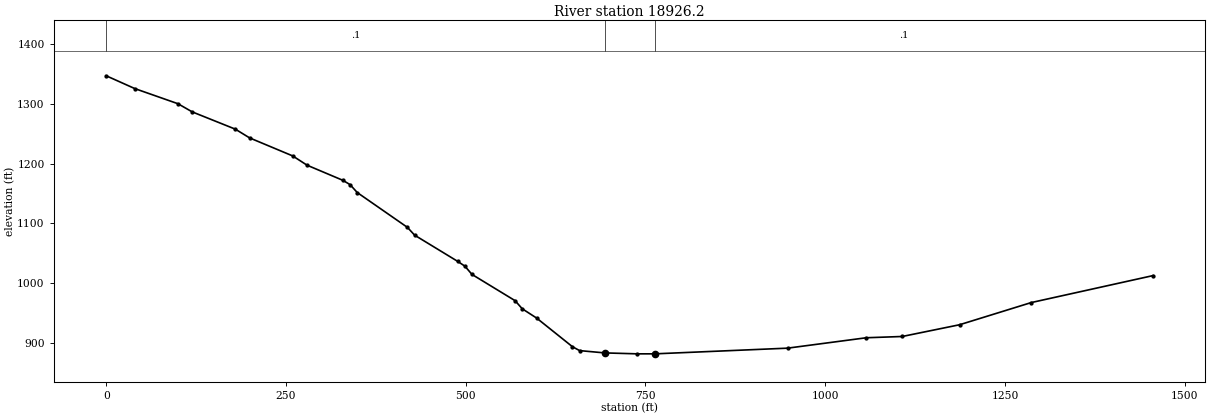
Type RM Length L Ch R = 1 ,18926.2 ,789.6,799.9,811.3
XS GIS Cut Line= 3
     1811411.069      340295.453      1812139.26      340281.212
     1812866.734      340260.695
#Sta/Elev= 30
       0 1347.27    39.9 1325.77    99.8 1300.47   119.7 1286.77   179.6 1257.89
   199.5 1243.22   259.4 1213.06   279.4 1197.51   329.2 1172.19   339.2 1164.97
   349.2 1151.72     419 1093.37     429 1080.34   488.9 1036.44   498.9 1028.43
   508.8 1014.58   568.7  970.65   578.7  957.03   598.6  941.59   648.5  893.53
   658.5  887.01   693.3  883.17   738.3   881.6   763.3   881.6   947.7  891.11
  1057.3  908.55  1107.2  910.66  1186.9   930.3  1286.6  967.45  1456.1 1012.65
#Mann= 3 , 0 , 0
       0      .1       0   693.3    .045       0   763.3      .1       0
Bank Sta=693.3,763.3
XS Rating Curve= 0 ,0
Exp/Cntr=0.3,0.1