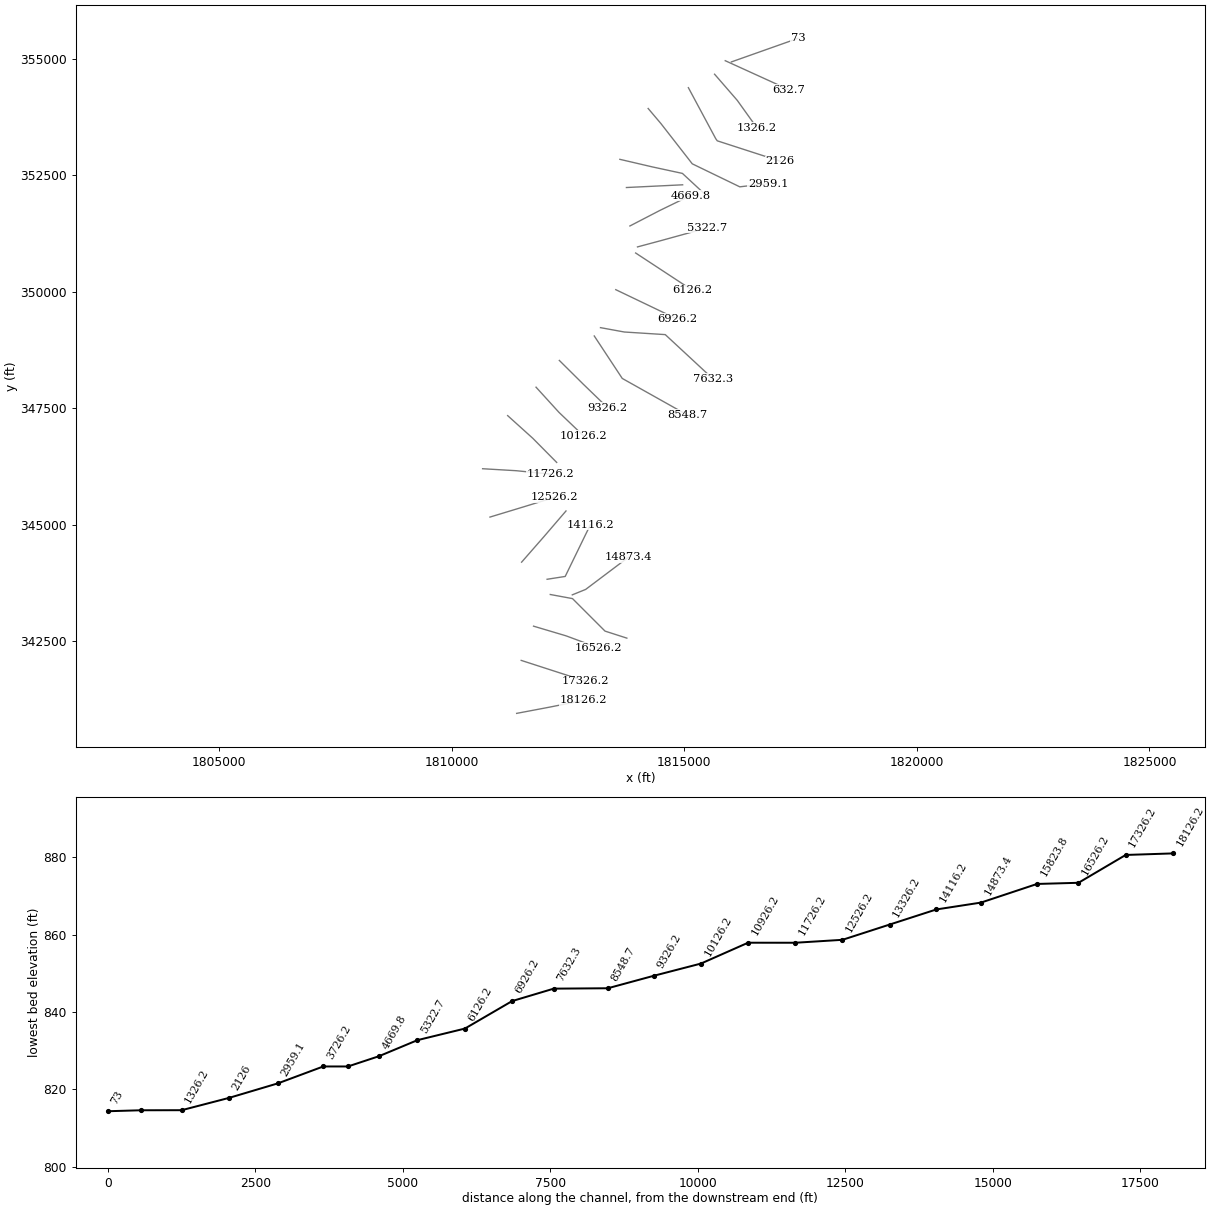
HEC-RAS study MrshFrk1.prj: MrshFrk1

--- MrshFrk1.g01 (geometry) --- (continued)

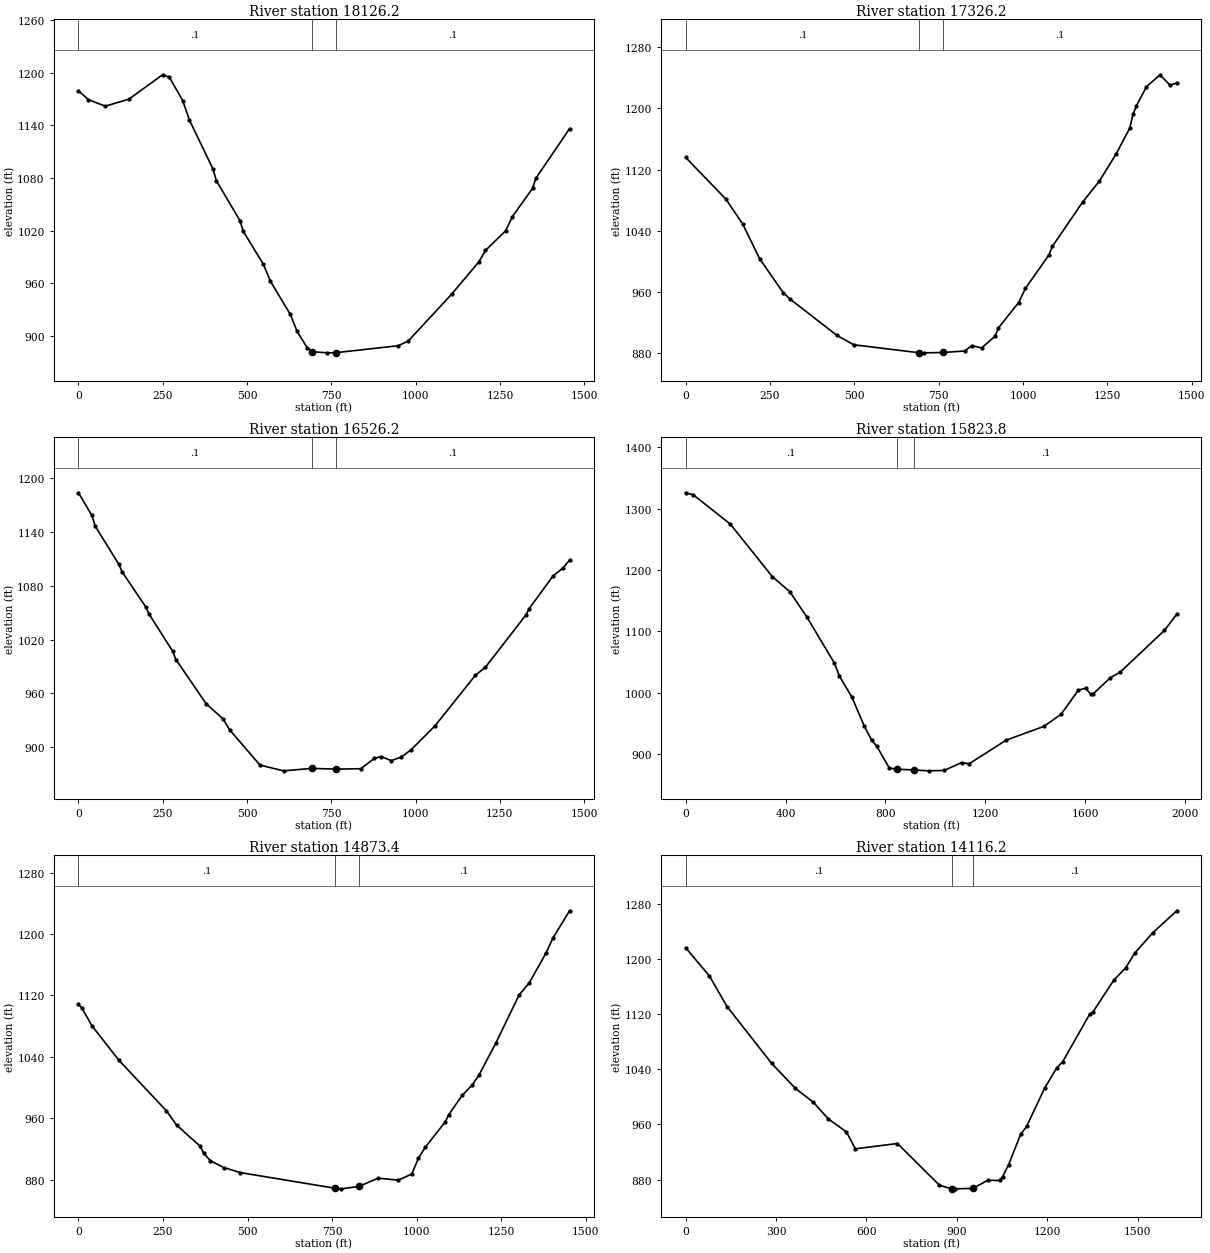
Type RM Length L Ch R = 1 ,18126.2 ,825,800,774.4
XS GIS Cut Line= 3
     1811398.147      340943.653     1812113.511      341078.964
     1812827.365      341221.735
#Sta/Elev= 30
       0 1179.46    29.9 1169.23    79.8 1161.83   149.6 1169.84   249.3 1197.59
   269.3 1194.99   309.2 1168.16   329.1 1146.02   398.9  1090.3   408.9 1077.04
   478.7 1031.59   488.7 1019.39   548.5  981.75   568.5  963.02   628.3  924.69
   648.3  905.41   678.2  886.81     693  882.23     738     881     763  881.19
   947.4  889.06   977.4  894.31    1107  948.05  1186.8  984.46  1206.7  997.58
  1266.6 1020.05  1286.5 1036.16  1346.3  1068.2  1356.3 1079.81    1456 1136.29
#Mann= 3 , 0 , 0
       0      .1       0     693    .045       0     763      .1       0
Bank Sta=693,763
XS Rating Curve= 0 ,0
Exp/Cntr=0.3,0.1

Type RM Length L Ch R = 1 ,17326.2 ,798.8,800,797.9
XS GIS Cut Line= 3
     1811496.073      342081.691     1812188.796      341857.817
     1812881.518      341633.943
#Sta/Elev= 30
       0 1136.02   119.7 1081.34   169.5 1048.67   219.4 1003.61   289.2  959.32
   309.2  950.98   448.8  903.28   498.6  891.11     693  880.69     708   880.6
     763  881.05   827.7  883.04   847.7  889.99   877.6  887.11   917.5   902.4
   927.4  913.23   987.3  946.37  1007.2  964.76    1077 1008.56    1087  1019.6
  1176.8 1077.59  1226.6 1105.08  1276.5  1140.8  1316.4 1174.08  1326.4 1192.37
  1336.3 1203.47  1366.2 1228.36  1406.1 1243.98    1436 1230.39    1456 1233.27
#Mann= 3 , 0 , 0
       0      .1       0     693    .045       0     763      .1       0
Bank Sta=693,763
XS Rating Curve= 0 ,0
Exp/Cntr=0.3,0.1

Type RM Length L Ch R = 1 ,16526.2 ,727.9,702.5,680.3
XS GIS Cut Line= 3
     1811761.212      342817.012     1812459.076      342609.509
     1813142.696      342356.722
#Sta/Elev= 30
       0 1183.93    39.9 1158.66    49.9 1146.52   119.7 1104.21   129.6 1095.66
   199.5 1056.58   209.4 1048.59   279.3 1007.14   289.2  997.73     379  948.31
   428.9  931.48   448.8  919.08   538.6  879.82   608.4   873.4   693.1  876.14
   763.1  875.31   837.9  875.78   877.8   887.3   897.8  889.38   927.8  884.82
   957.7  888.72   987.6  897.18  1057.5  923.54  1177.4  980.07  1207.3  989.09
  1327.1 1047.33  1337.1 1054.54    1407 1090.61    1437 1099.85  1456.9 1108.76
#Mann= 3 , 0 , 0
       0      .1       0   693.1    .045       0   763.1      .1       0
Bank Sta=693.1,763.1
XS Rating Curve= 0 ,0
Exp/Cntr=0.3,0.1

Type RM Length L Ch R = 1 ,15823.8 ,876.7,950.4,1024.1
XS GIS Cut Line= 4
     1812120.862      343497.178     1812598.942      343408.861
     1813297.689      342710.773      1813766.72      342559.977
#Sta/Elev= 30
       0 1325.84    29.8 1322.74   178.6 1274.99   347.3 1189.26   416.7 1165.01
   486.2 1123.06   595.9 1048.34   615.9 1027.29   665.8  993.13   715.6  945.58
   745.6  922.53   765.5  913.12   815.4   877.8   844.7  875.82   914.7  874.51
     975   873.1  1034.9  873.72  1104.7  886.48  1134.7  884.55  1284.3  923.22
    1434  945.38  1503.4  965.25  1572.4 1004.41    1602 1007.71  1621.7  997.81
  1631.5  998.51  1700.5 1024.59  1739.9 1033.84  1917.3 1101.81  1966.6 1128.22
#Mann= 3 , 0 , 0
       0      .1       0   844.7    .045       0   914.7      .1       0
Bank Sta=844.7,914.7
XS Rating Curve= 0 ,0
Exp/Cntr=0.3,0.1

Type RM Length L Ch R = 1 ,14873.4 ,733.3,757.2,781.1
XS GIS Cut Line= 3
     1812594.451      343489.707     1812881.904      343606.485
     1813794.028      344292.764
#Sta/Elev= 30
       0 1108.46      10 1103.96      40 1080.51   120.1 1035.42   260.2   969.8
   290.2   951.3   359.9   923.7   369.8  915.02   389.7     905   429.4  896.02
     479   889.4   758.9  869.03   776.8  868.28   828.9  871.45     886  882.15
   945.5  879.58   985.2  887.55  1005.1  908.24  1024.9  922.26  1084.5  955.56
  1094.4  964.73  1134.1   989.9  1163.9 1003.41  1183.7 1016.24  1233.4 1057.69
  1302.8 1120.93  1332.6 1136.44  1382.2 1175.36  1402.1  1194.5  1451.7 1230.25
#Mann= 3 , 0 , 0
       0      .1       0   758.9    .045       0   828.9      .1       0
Bank Sta=758.9,828.9
XS Rating Curve= 0 ,0
Exp/Cntr=0.3,0.1

Type RM Length L Ch R = 1 ,14116.2 ,803.3,790,777.1
XS GIS Cut Line= 3
     1812052.598      343824.281     1812441.741      343884.955
     1812982.862      344996.283
#Sta/Elev= 30
       0 1216.06    78.8 1175.02   137.8 1130.55   285.5  1048.3   364.3 1012.08
   423.8  992.04   473.6  967.85   533.4  949.11   563.3  924.49   702.9   932.2
   842.4  871.67     883  866.52   892.3   866.5     953   867.2  1001.9  878.72
  1041.8  878.76  1051.8  884.02  1071.7  901.32  1111.6  945.44  1131.5  956.94
  1191.3 1012.37  1231.2 1041.73  1251.1 1050.56  1340.8 1119.69  1350.8 1122.19
  1420.6 1168.82  1460.4 1186.87  1490.4 1208.08  1550.2 1237.71  1629.9 1269.52
#Mann= 3 , 0 , 0
       0      .1       0     883    .045       0     953      .1       0
Bank Sta=883,953
XS Rating Curve= 0 ,0
Exp/Cntr=0.3,0.1

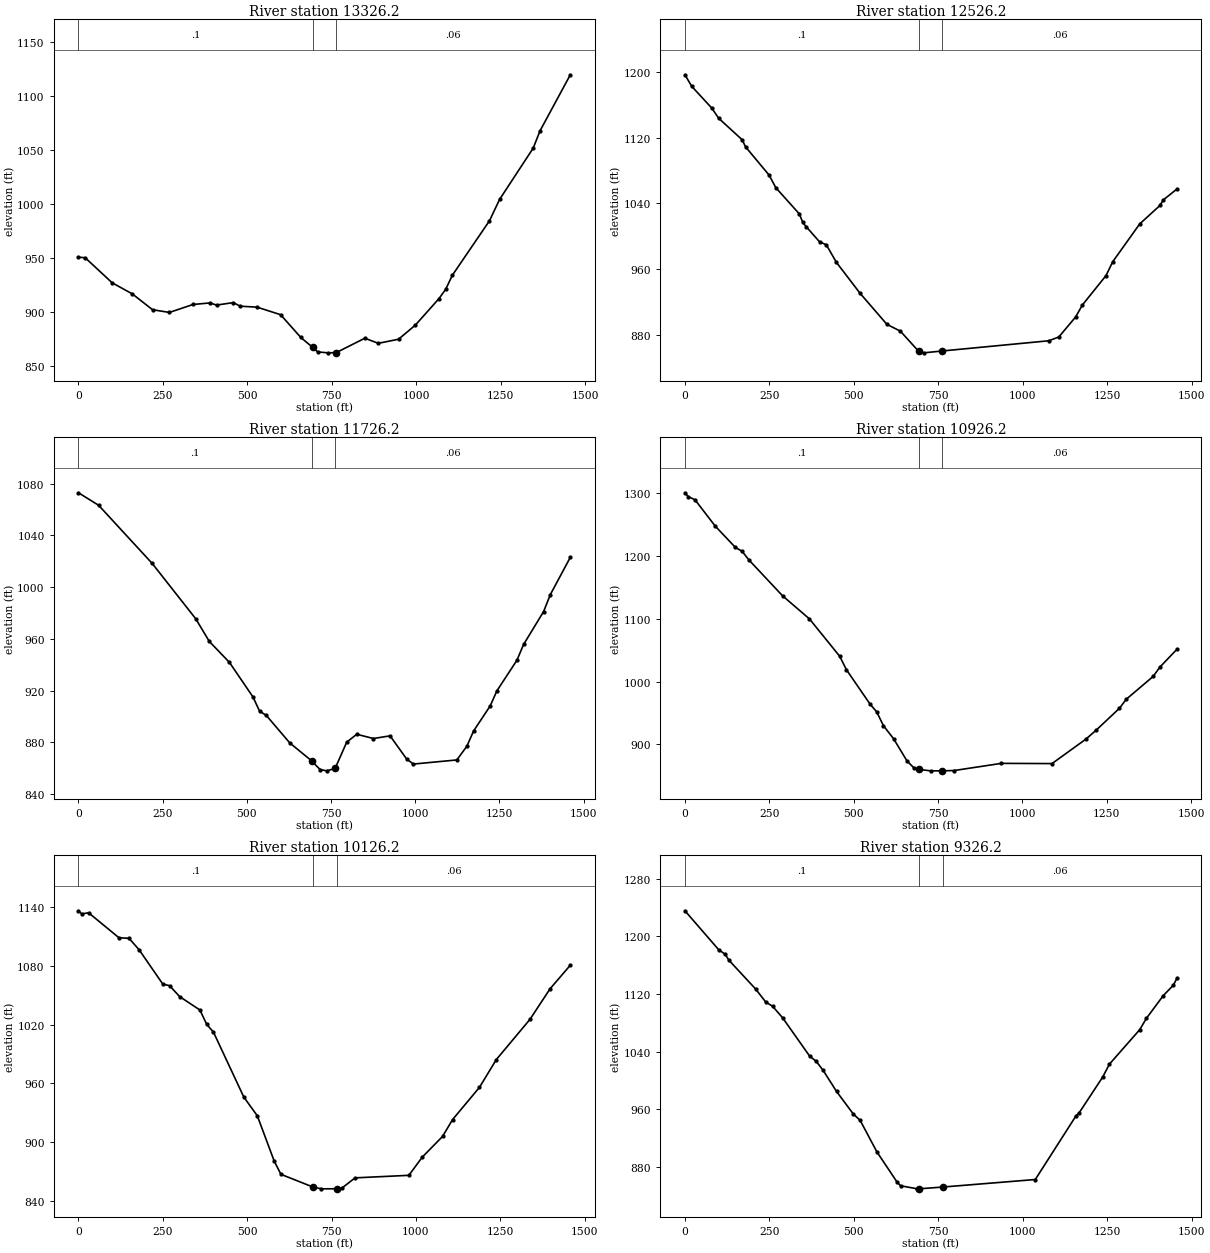
Type RM Length L Ch R = 1 ,13326.2 ,827.9,800,771.7
XS GIS Cut Line= 3
     1811504.599      344191.753     1811984.354      344739.301
      1812458.78      345291.538
#Sta/Elev= 30
       0  950.99      20  950.46    99.7  927.34   159.6  917.03   219.4  902.43
   269.3  899.95   339.1  907.28   388.9  908.71   408.9  906.74   458.7  909.02
   478.7  905.69   528.5  904.84   598.4  897.85   658.2  876.82     693  867.74
     708  863.48     738   862.6     763  862.79   847.7  876.11   887.6  871.41
   947.4  875.16   997.3  888.22  1067.1  912.67    1087  921.29    1107   934.4
  1216.7  984.62  1246.6 1004.35  1346.3 1051.84  1366.3 1067.73    1456 1119.54
#Mann= 3 , 0 , 0
       0      .1       0     693    .045       0     763     .06       0
Bank Sta=693,763
XS Rating Curve= 0 ,0
Exp/Cntr=0.3,0.1

Type RM Length L Ch R = 1 ,12526.2 ,817.7,800,780.1
XS GIS Cut Line= 3
     1810824.461       345160.28     1811520.583      345371.446
     1812217.253      345585.054
#Sta/Elev= 30
       0 1196.22    19.9 1182.31    79.7 1155.67    99.6 1143.54   169.4 1117.33
   179.4 1108.78   249.1 1074.45   269.1 1059.12   338.8 1027.25   348.8 1016.96
   358.7 1011.94   398.6  993.38   418.5  989.89   448.4  968.53   518.2  931.06
   597.9  893.23   637.8  884.96   692.4  860.28   707.5  858.65   762.4  860.94
  1076.8  873.28  1106.8  877.88  1156.7  902.25  1176.6  916.72  1246.5  952.41
  1266.5   969.3  1346.3 1015.14  1406.2 1037.55  1416.2 1044.36  1456.1 1057.35
#Mann= 3 , 0 , 0
       0      .1       0   692.4    .045       0   762.4     .06       0
Bank Sta=692.4,762.4
XS Rating Curve= 0 ,0
Exp/Cntr=0.3,0.1

Type RM Length L Ch R = 1 ,11726.2 ,833.8,800,765.4
XS GIS Cut Line= 3
     1810666.476       346198.69     1811392.298      346155.994
     1812121.843      346082.535
#Sta/Elev= 30
       0 1073.05    59.8  1063.4   219.1 1018.33   348.6  975.42   388.4  958.06
   448.2  941.84   517.9  915.16   537.8  904.09   557.8  900.75   627.5  879.47
   692.1  865.67   717.1  858.92     737  857.89   762.1  859.78   796.4  880.05
   826.2  886.19   875.7  882.91   925.2  884.96   974.8   866.9   994.6  863.14
  1123.4  866.32  1153.2  876.91    1173  888.68  1222.5  908.14  1242.3  919.79
  1301.8  943.46  1321.6  955.68    1381  981.14  1400.9  994.24  1460.3 1023.11
#Mann= 3 , 0 , 0
       0      .1       0   692.1    .045       0   762.1     .06       0
Bank Sta=692.1,762.1
XS Rating Curve= 0 ,0
Exp/Cntr=0.3,0.1

Type RM Length L Ch R = 1 ,10926.2 ,804.8,800,801.5
XS GIS Cut Line= 3
     1811204.574      347339.621     1811745.239      346852.487
     1812258.612      346334.312
#Sta/Elev= 30
       0 1300.99      10 1294.91    29.9 1289.74    89.7 1247.94   149.5 1213.89
   169.5 1207.73   189.4 1194.05   289.1  1136.9   368.9    1100   458.6  1040.4
   478.5    1019   548.3  964.33   568.2  951.82   588.2   929.8   618.1  909.09
     658  873.62   677.9  862.89   692.7  860.21   727.8   857.9   762.7   857.9
   797.7  858.41   937.6  869.81  1087.5  869.46  1187.4  908.22  1217.4  922.24
  1287.3  957.59  1307.3  971.89  1387.2 1008.36  1407.2 1023.26  1457.2  1051.4
#Mann= 3 , 0 , 0
       0      .1       0   692.7    .045       0   762.7     .06       0
Bank Sta=692.7,762.7
XS Rating Curve= 0 ,0
Exp/Cntr=0.3,0.1

Type RM Length L Ch R = 1 ,10126.2 ,797.4,800,799.7
XS GIS Cut Line= 3
     1811815.051      347950.297     1812306.743       347410.53
     1812832.939      346907.985
#Sta/Elev= 30
       0 1136.12      10 1132.92      30  1134.1     120 1108.64     150 1108.03
     180 1096.27     250 1061.34     270 1059.72   300.1 1048.55   360.1 1034.87
   380.1 1020.26   400.1 1012.37   490.1  946.13   530.1  927.01   580.1  880.89
   600.1  867.31   695.1  854.34   720.1   852.5   765.1  852.58     780  853.02
   819.8   863.7   979.3  866.28  1019.2  884.93    1079   905.9  1108.9  923.17
  1188.6  956.04  1238.5  984.35  1338.2 1025.37    1398 1056.64  1457.8  1080.6
#Mann= 3 , 0 , 0
       0      .1       0   695.1    .045       0   765.1     .06       0
Bank Sta=695.1,765.1
XS Rating Curve= 0 ,0
Exp/Cntr=0.3,0.1

Type RM Length L Ch R = 1 ,9326.2  ,787.4,777.6,767.1
XS GIS Cut Line= 3
     1812315.716      348524.737     1812832.703      348012.206
     1813356.617      347506.622
#Sta/Elev= 30
       0 1235.66    99.7 1181.68   119.7 1175.03   129.6 1167.28   209.4 1126.88
   239.3 1108.85   259.3 1103.11   289.2 1086.95     369 1033.88   388.9 1026.32
   408.9 1014.13   448.8  984.66   498.6  953.24   518.6  944.58   568.4   900.6
   628.3  858.52   638.2  853.64   688.1  849.34     693  849.36     763  851.83
  1037.2  862.29  1156.8  950.06  1166.8  954.81  1236.6 1004.56  1256.6 1022.56
  1346.4  1070.5  1366.3 1086.33  1416.2 1117.89  1446.1 1132.33  1456.1 1141.61
#Mann= 3 , 0 , 0
       0      .1       0     693    .045       0     763     .06       0
Bank Sta=693,763
XS Rating Curve= 0 ,0
Exp/Cntr=0.3,0.1

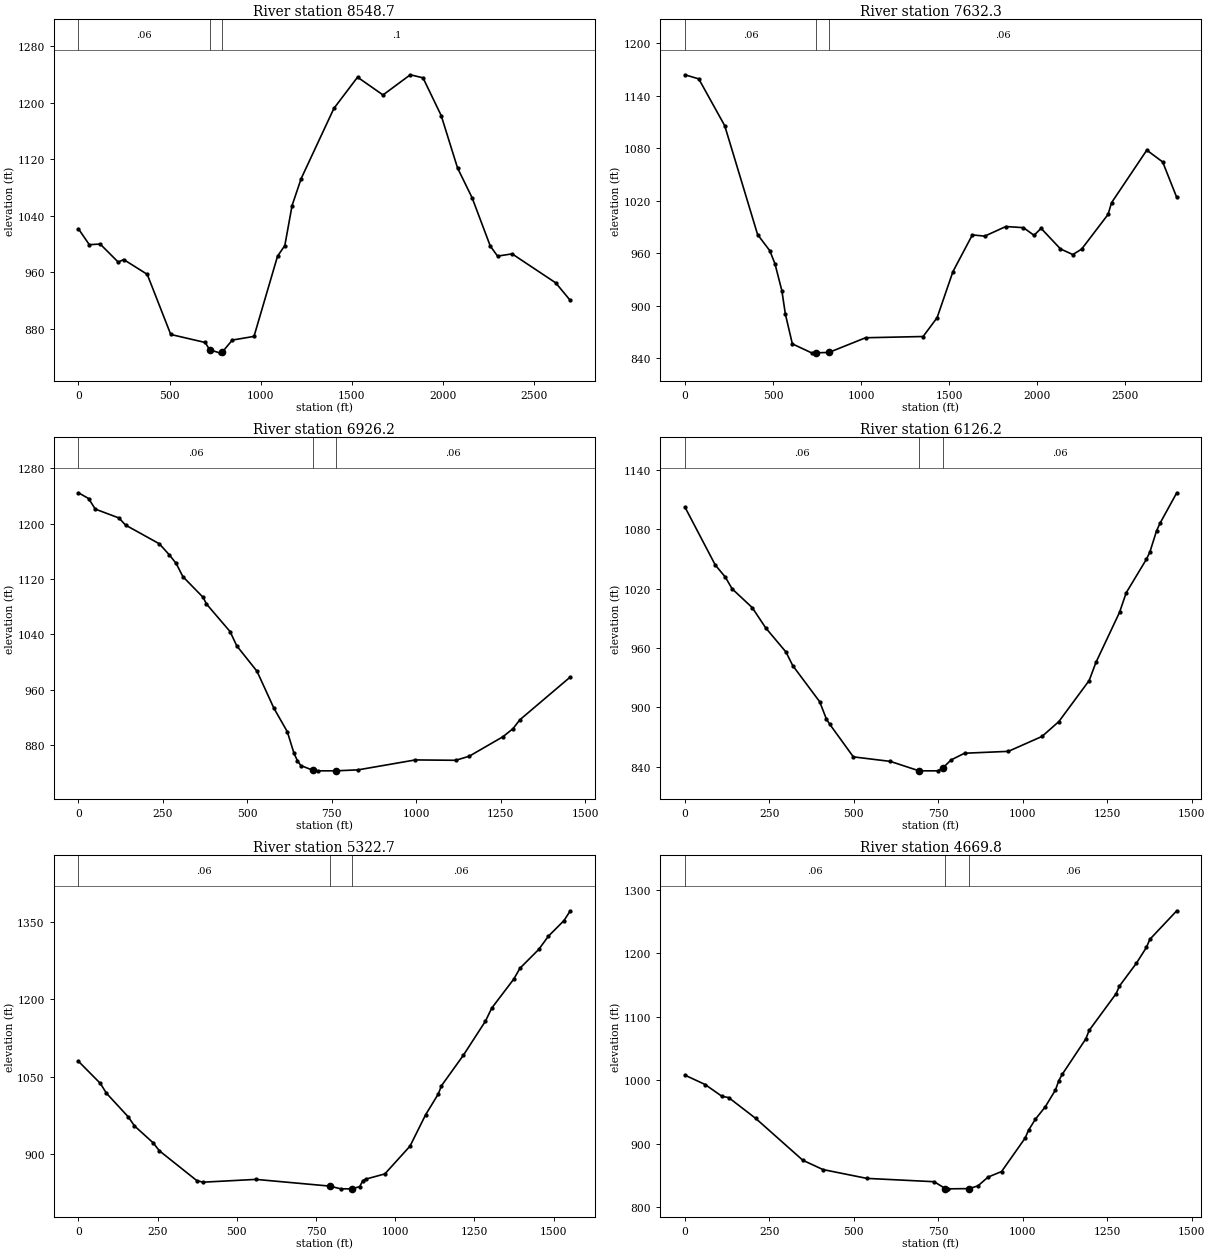
Type RM Length L Ch R = 1 ,8548.7  ,870.6,916.4,962.2
XS GIS Cut Line= 3
      1813066.25      349050.469     1813667.908      348138.362
     1815069.241      347352.357
#Sta/Elev= 30
       0 1021.71    59.6  999.25   119.2 1000.16   218.5  974.55   248.3  978.23
   377.5  957.28   506.6  872.14   695.3  860.81   720.5  850.37   774.8  846.12
   790.5  847.54   844.3  864.18   963.5  869.41  1092.7  982.99  1132.6  998.01
  1172.5 1054.74  1222.4  1092.9    1402 1192.24  1531.8 1236.44  1671.5 1211.26
  1821.2 1239.84    1891 1235.54  1990.8 1182.15  2080.6 1107.87  2160.5 1065.69
  2260.3  997.31  2300.2  983.06    2380  986.27  2619.6  945.18  2699.4   920.3
#Mann= 3 , 0 , 0
       0     .06       0   720.5    .045       0   790.5      .1       0
Bank Sta=720.5,790.5
XS Rating Curve= 0 ,0
Exp/Cntr=0.3,0.1

Type RM Length L Ch R = 1 ,7632.3  ,726.8,706,685.3
XS GIS Cut Line= 4
     1813200.237      349229.246     1813712.823      349135.464
     1814592.453      349079.615     1815612.707       348133.87
#Sta/Elev= 30
       0 1164.05    78.7 1159.35   226.1 1105.81   412.9  981.26   481.8  962.95
   511.3  948.05   550.8  916.97   570.6  890.31   610.2  856.29   719.2  846.02
   747.4   846.1   817.4  846.43  1026.2  863.28    1353  864.69  1432.5  886.25
  1522.6  939.04  1632.7  980.93  1702.8  979.49  1822.8  990.48  1922.9  989.19
    1983  980.43    2023  988.43  2133.1  964.89  2203.2  958.44  2253.2  964.62
  2403.3 1004.28  2423.4 1017.77  2623.5 1077.84  2713.6 1064.36  2793.7  1023.7
#Mann= 3 , 0 , 0
       0     .06       0   747.4    .045       0   817.4     .06       0
Bank Sta=747.4,817.4
XS Rating Curve= 0 ,0
Exp/Cntr=0.3,0.1

Type RM Length L Ch R = 1 ,6926.2  ,806.7,800,793.3
XS GIS Cut Line= 3
     1813528.779      350044.873     1814185.432      349730.562
     1814842.084      349416.252
#Sta/Elev= 30
       0 1244.37    29.9  1236.1    49.9 1220.79   119.7 1208.02   139.6 1197.68
   239.3 1170.76   269.3 1154.56   289.2 1142.31   309.2 1123.24     369 1093.38
     379 1083.75   448.8 1043.95   468.7 1023.27   528.6   986.6   578.4  933.46
   618.3  899.25   638.2  867.91   648.2  857.45   658.2  850.47     693  843.83
     708   842.8     763  842.83   827.7  844.21   997.3  858.56  1116.9  858.03
  1156.8  863.91  1256.6  892.06  1286.5  903.76  1306.4   916.4    1456  978.35
#Mann= 3 , 0 , 0
       0     .06       0     693    .045       0     763     .06       0
Bank Sta=693,763
XS Rating Curve= 0 ,0
Exp/Cntr=0.3,0.1

Type RM Length L Ch R = 1 ,6126.2  ,760.8,803.5,846.2
XS GIS Cut Line= 3
     1813955.877       350832.64     1814564.488       350433.17
       1815173.1        350033.7
#Sta/Elev= 30
       0 1102.39    89.8 1043.84   119.7 1031.52   139.6 1019.78   199.4 1000.66
   239.3  980.15   299.2   955.8   319.1  942.14   398.9  905.59   418.8  888.09
   428.8  882.76   498.6  849.82   608.3  845.22     693   835.7     748  835.69
     763  838.46   787.8  846.68   827.7  853.49   957.4  855.39  1057.1  870.47
    1107  885.52  1196.7  927.01  1216.7  945.28  1286.5  995.87  1306.4 1015.77
  1366.2 1049.66  1376.2  1056.7  1396.2 1078.35  1406.1  1085.8    1456 1116.82
#Mann= 3 , 0 , 0
       0     .06       0     693    .045       0     763     .06       0
Bank Sta=693,763
XS Rating Curve= 0 ,0
Exp/Cntr=0.3,0.1

Type RM Length L Ch R = 1 ,5322.7  ,643.8,653,662.2
XS GIS Cut Line= 3
     1813995.784      350963.485     1814498.827      351098.229
     1815493.757       351372.02
#Sta/Elev= 30
       0 1080.02    68.8 1037.39    88.4  1018.1   157.2   972.3   176.9  954.69
   235.8  921.94   255.5  906.47   373.4  848.78     393  845.59  560.24  851.02
   793.1  838.03   828.4   832.7   863.1   832.7   887.9  836.99   897.8  848.76
   907.7  851.64   967.3  861.66  1046.7  915.55  1096.3  976.76    1136 1016.66
  1145.9 1032.53  1215.3 1091.93  1284.8 1157.81  1304.6 1183.13  1374.1  1239.3
  1393.9 1260.55  1453.5  1297.2  1483.2 1322.37  1532.8  1352.9  1552.7 1371.89
#Mann= 3 , 0 , 0
       0     .06       0   793.1    .045       0   863.1     .06       0
#XS Ineff= 2 , 0
          559.43  850.68
Permanent Ineff=
       F       F
Bank Sta=793.1,863.1
XS Rating Curve= 0 ,0
Exp/Cntr=0.3,0.1

Type RM Length L Ch R = 1 ,4669.8  ,546,525.6,505.2
XS GIS Cut Line= 3
     1813832.398      351413.134     1814478.807      351747.897
     1815133.892      352066.126
#Sta/Elev= 30
       0 1007.95    59.8  993.16   109.7  974.52   129.6  972.52   209.4  939.77
     349  873.66   408.8  858.94   538.5  845.05   737.9  839.78   771.3  828.87
   777.8  828.54   841.3  828.89   867.6  833.23   897.6  847.12   937.5  855.84
  1007.3  908.67  1017.3  920.97  1037.2  938.09  1067.2  958.22  1097.1  984.61
  1107.1  999.48    1117 1009.09  1186.9 1065.15  1196.8 1078.53  1276.7 1136.57
  1286.6 1148.59  1336.5 1184.39  1366.4 1209.52  1376.4 1222.18  1456.2 1267.28
#Mann= 3 , 0 , 0
       0     .06       0   771.3    .045       0   841.3     .06       0
Bank Sta=771.3,841.3
XS Rating Curve= 0 ,0
Exp/Cntr=0.3,0.1

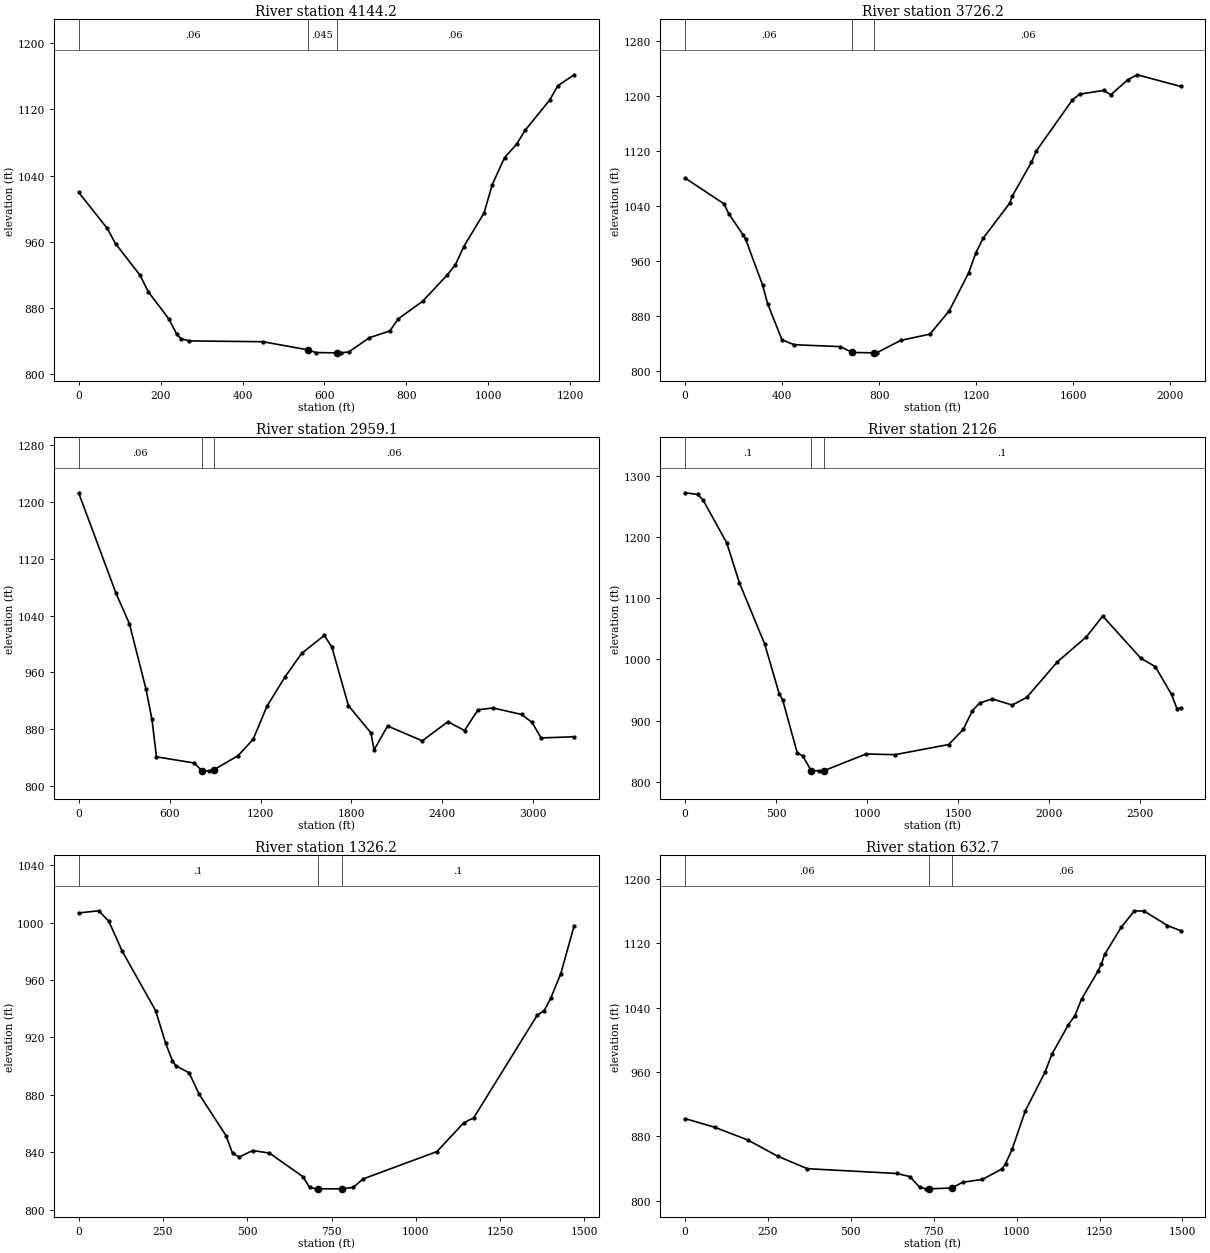
Type RM Length L Ch R = 1 ,4144.2  ,431.7,417.9,405
XS GIS Cut Line= 2
     1813757.737      352239.058     1814965.938      352297.447
#Sta/Elev= 30
       0 1019.96      70  976.19      90  957.89     150  919.63     170  899.76
   219.9  867.07   239.9  848.08   249.9  842.96   269.9   840.3   449.9  839.32
   559.6  829.49   579.8   826.2   629.6   825.9   639.8  825.89   659.8  827.02
   709.8   844.2   759.8  852.37   779.8  866.81   839.7  888.24   899.7  919.92
   919.7  932.33   939.7  953.97   989.7  995.07  1009.7 1029.33  1039.7 1061.77
  1069.7 1078.53  1089.6 1094.74  1149.6 1131.29  1169.6 1148.69  1209.6 1161.96
#Mann= 3 , 0 , 0
       0     .06       0   559.6    .045       0   629.6     .06       0
Bank Sta=559.6,629.6
XS Rating Curve= 0 ,0
Exp/Cntr=0.3,0.1

Type RM Length L Ch R = 1 ,3726.2  ,801.3,767.2,732.2
XS GIS Cut Line= 4
     1813616.765      352844.711     1814317.377      352681.351
     1814961.234      352542.423     1815448.796      352091.051
#Sta/Elev= 30
       0 1080.62   159.9 1043.17   179.8 1028.75   239.8  997.39   249.8  991.18
   319.7  924.48   339.7  897.74   399.7  844.78   449.6  837.73   639.5  834.94
   689.4  826.41   779.3   825.9   789.3  825.89   889.1  844.11  1008.8   853.1
  1088.7  887.05  1168.5  942.23  1198.4   971.7  1228.4  992.86  1338.2 1044.16
  1348.1 1054.01  1427.7 1103.74  1447.5  1120.1  1596.2 1194.39    1626 1202.88
  1725.2 1208.33  1754.9 1202.08  1824.3 1223.78    1864 1231.13  2042.5 1214.12
#Mann= 3 , 0 , 0
       0     .06       0   689.4    .045       0   779.3     .06       0
Bank Sta=689.4,779.3
XS Rating Curve= 0 ,0
Exp/Cntr=0.3,0.1

Type RM Length L Ch R = 1 ,2959.1  ,841.4,833,824.7
XS GIS Cut Line= 5
     1814224.848      353936.827     1814498.827      353613.443
     1815173.153      352748.058     1816194.109      352254.028
     1816803.999      352325.082
#Sta/Elev= 30
       0  1212.6   246.4 1071.35   335.1 1028.28   443.8  937.01   483.7     894
   513.6  841.22   762.9  832.56   812.8  821.66   862.7  821.53   892.6  823.13
  1052.2  842.91  1151.9  865.98  1241.7  912.16  1361.4   953.6  1471.1  986.62
  1620.4 1011.95  1670.2  995.93  1779.6  913.36  1928.8  874.76  1948.8  850.93
  2038.3   884.6  2267.1  863.75  2436.2  890.64  2545.7  878.22  2635.2  907.48
  2734.4  909.92  2922.5  900.81  2991.8  889.52  3051.3   867.8  3269.2  869.46
#Mann= 3 , 0 , 0
       0     .06       0   812.8    .045       0   892.6     .06       0
Bank Sta=812.8,892.6
XS Rating Curve= 0 ,0
Exp/Cntr=0.3,0.1

Type RM Length L Ch R = 1 ,2126    ,788.6,799.8,806.3
XS GIS Cut Line= 4
     1815089.481       354383.73     1815677.384       353288.42
     1815710.556      353242.151     1817065.243       352804.03
#Sta/Elev= 30
       0 1272.24    69.6 1269.43    99.4 1260.06   228.7 1190.49   298.4 1125.17
   437.6 1024.96   517.1  943.93     537  933.06   616.6  846.87   646.4  842.23
     693  818.06   735.9  817.75     763  817.93   994.5  845.31  1153.6  844.17
  1449.4  860.77    1529  885.48  1578.8  915.84  1618.6  928.57  1688.4   935.3
  1797.9  925.25  1877.5  937.75  2046.8  996.03  2206.1 1036.86  2295.7 1070.73
  2504.8 1001.83  2584.4  988.09    2674  942.54  2703.9  919.06  2723.8  920.95
#Mann= 3 , 0 , 0
       0      .1       0     693    .045       0     763      .1       0
Bank Sta=693,763
XS Rating Curve= 0 ,0
Exp/Cntr=0.3,0.1

Type RM Length L Ch R = 1 ,1326.2  ,671.6,693.5,720.1
XS GIS Cut Line= 3
     1815652.654      354673.088     1816140.576      354110.766
     1816562.821      353521.524
#Sta/Elev= 30
       0 1006.66    59.6 1008.17    89.3 1000.98     129  980.13   228.3  938.65
   258.1  915.87   277.9  903.92   287.9   900.3   327.6  895.36   357.4  880.42
   436.8  851.71   456.6  839.23   476.5  836.75   516.2  841.25   565.8  839.47
   665.1  823.04   684.9  815.55   704.8  814.58   709.5  814.59   779.5   814.6
     814  815.61   843.8   821.5  1062.3  840.51  1141.7  860.47  1171.5  864.05
  1360.2   935.6    1380  938.55  1399.9  947.23  1429.7  964.42  1469.4   997.8
#Mann= 3 , 0 , 0
       0      .1       0   709.5    .045       0   779.5      .1       0
Bank Sta=709.5,779.5
XS Rating Curve= 0 ,0
Exp/Cntr=0.3,0.1

Type RM Length L Ch R = 1 ,632.7   ,521.2,559.6,598.2
XS GIS Cut Line= 2
     1815881.923      354963.156     1817241.983      354343.959
#Sta/Elev= 30
       0  901.88    89.7  891.05   189.3  875.26     279  855.18   368.6  839.61
   637.6  833.68   677.4  829.86   707.3   816.6   727.3  814.56   734.1  814.59
   804.1  815.56   836.8  822.69   896.6  826.25   956.4  839.46   966.4  845.86
   986.3  863.83  1026.1  911.63  1085.9  960.01  1105.8  981.62  1155.6 1018.41
  1175.6 1030.03  1195.5  1050.3  1245.3 1085.38  1255.3 1093.99  1265.2 1105.99
    1315 1139.63  1354.9 1160.27  1384.8 1159.76  1454.5 1141.96  1494.4 1135.48
#Mann= 3 , 0 , 0
       0     .06       0   734.1    .045       0   804.1     .06       0
Bank Sta=734.1,804.1
XS Rating Curve= 0 ,0
Exp/Cntr=0.3,0.1

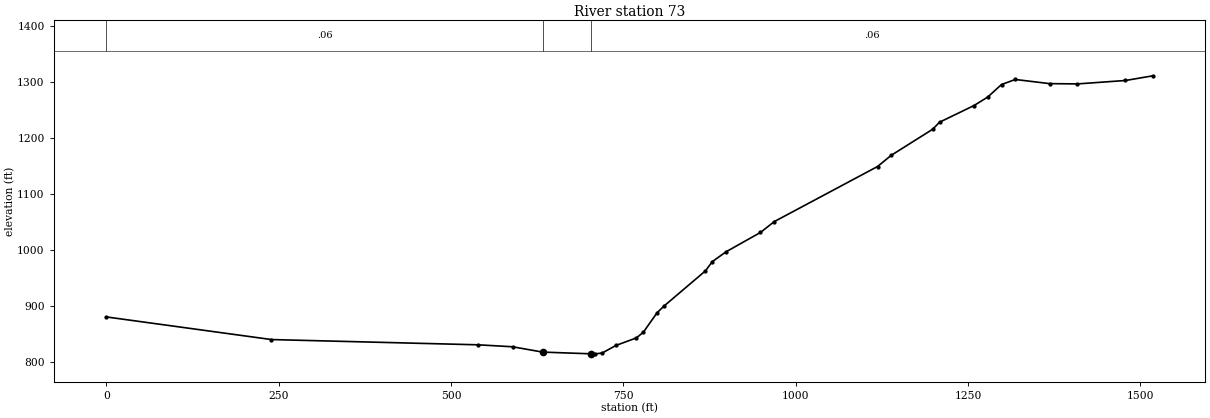
Type RM Length L Ch R = 1 ,73      ,72,73,74
XS GIS Cut Line= 2
     1816014.825      354937.523     1817446.224      355443.683
#Sta/Elev= 30
       0  880.34   239.7  839.84   539.4  830.45   589.3  826.95   633.1  817.41
   703.1  814.36   709.2  814.31   719.2  815.69   739.2  829.28   769.1  842.87
   779.1  853.12   799.1  887.96   809.1  899.87     869  962.55     879  979.13
     899   996.8   948.9 1031.34   968.9 1050.75  1118.7 1149.26  1138.7 1169.41
  1198.6 1215.83  1208.6 1228.47  1258.6 1258.26  1278.5 1273.45  1298.5 1295.85
  1318.5 1304.87  1368.4 1297.44  1408.4 1296.94  1478.3 1303.07  1518.3 1311.49
#Mann= 3 , 0 , 0
       0     .06       0   633.1    .045       0   703.1     .06       0
Bank Sta=633.1,703.1
XS Rating Curve= 0 ,0
Exp/Cntr=0.3,0.1

Chan Stop Cuts=-1
Use User Specified Reach Order=0
Composite Channel Slope=5